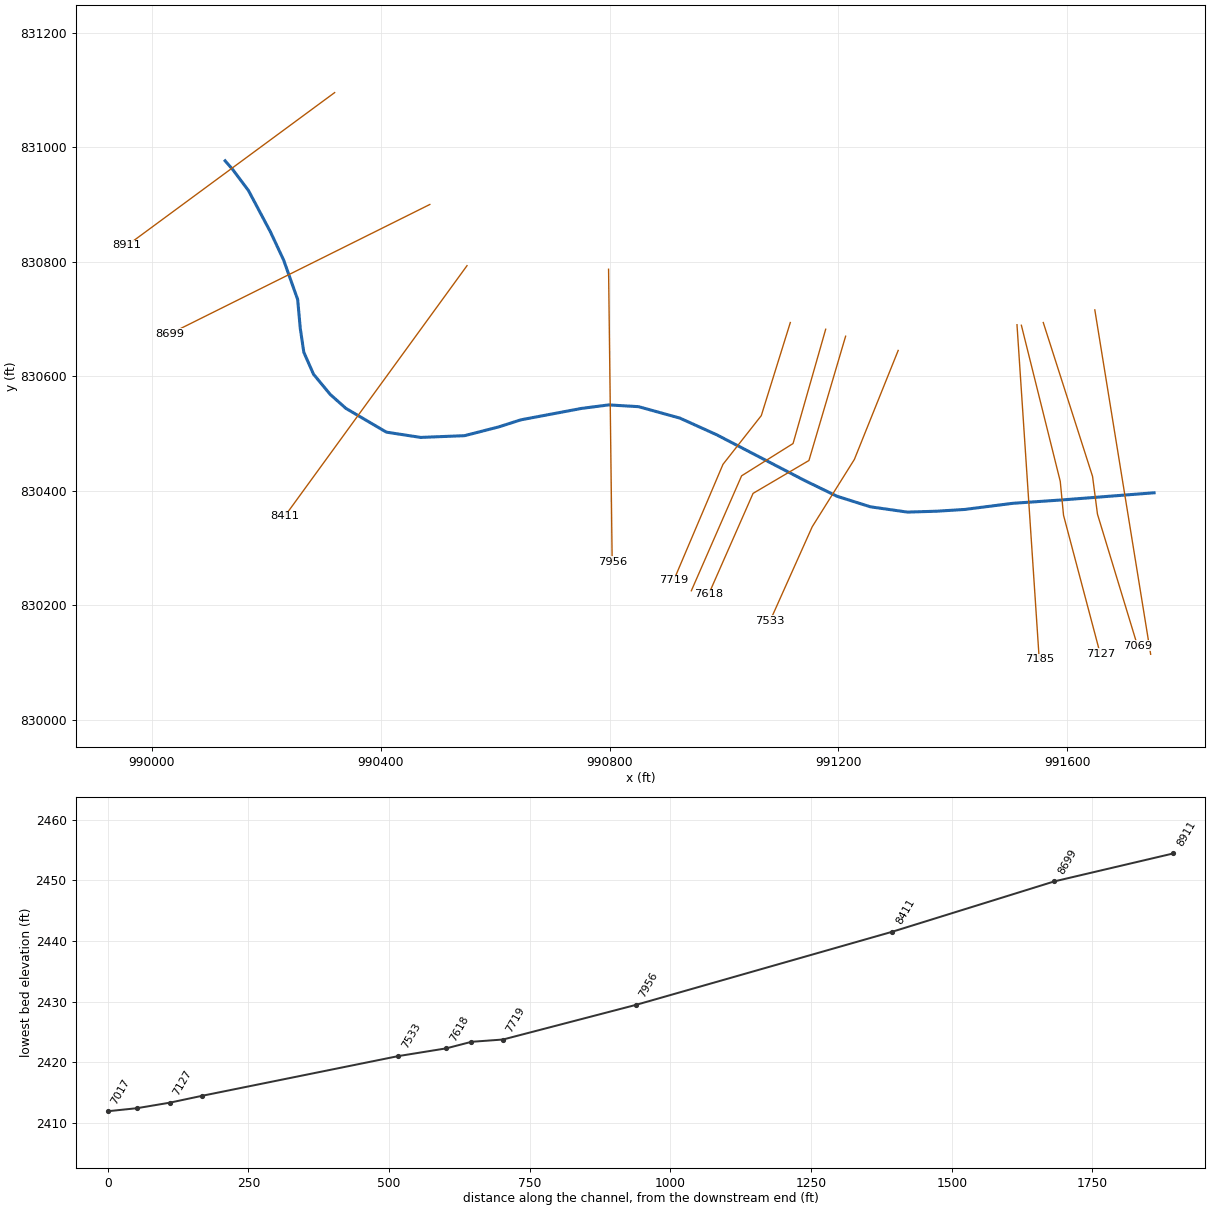
--- lds_bald_mountain_crk.prj (project) ---

Proj Title=Bald Mountain Creek - LDS
Current Plan=p01
Default Exp/Contr=0.3,0.1
English Units
Geom File=g01
Flow File=f02
Plan File=p01
Plan File=p02
Y Axis Title=Elevation
X Axis Title(PF)=Main Channel Distance
X Axis Title(XS)=Station
BEGIN DESCRIPTION:
END DESCRIPTION:
DSS Export Rating Curves= 0
DSS Export Rating Curve Sorted= 0
DSS Export Volume Flow Curves= 0
DXF OffsetX= 0
DXF OffsetY= 0
DXF ScaleX= 1
DXF ScaleY= 10

--- lds_bald_mountain_crk.p01 (plan) ---

Plan Title=floodway
Program Version=3.13
Short Identifier=floodway
Geom File=g01
Flow File=f02
Subcritical Flow
K Sum by GR= 0
Std Step Tol= 0.01
Critical Tol= 0.01
Num of Std Step Trials= 20
Max Error Tol= 0.3
Flow Tol Ratio= 0.001
Split Flow NTrial= 30
Split Flow Tol= 0.02
Split Flow Ratio= 0.02
Log Output Level= 0
Friction Slope Method= 0
Unsteady Friction Slope Method= 2
Unsteady Bridges Friction Slope Method= 1
Secant Critical Depth
Global Vel Dist= 0 , 0 , 0
Global Log Level= 0
CheckData=True
Encroach Param=-1 ,10,10, 2
Encroach River=Bald Mountain Cr
Encroach Reach=Main
Encroach Node=8911
       1  197.82  293.49
Encroach Node=8699
       1 4973.33 5085.36
Encroach Node=8411
       1 4888.77    5025
Encroach Node=7956
       1    4975    5100
Encroach Node=7719
       1 4945.76    5050
Encroach Node=7663
       1    4945 5047.92
Encroach Node=7618
       1 4950.34 5048.46
Encroach Node=7533
       1 4914.15 5048.14
Encroach Node=7185
       1    4895    5060
Encroach Node=7127
       1    4910    5100
Encroach Node=7069
       1 4920.81 5106.77
Encroach Node=7017
       1   227.6   327.6
Computation Interval=1HOUR
Output Interval=1HOUR
Run HTab= 0
Run UNet= 0
Run PostProcess= 0
UNET Theta= 1
UNET Theta Warmup= 1
UNET ZTol= 0.02
UNET ZSATol= 0.05
UNET MxIter= 20
UNET MaxInSteps= 0
UNET DtIC= 0
UNET DtMin= 0
UNET MaxCRTS= 20
UNET WFStab= 2
UNET SFStab= 1
UNET WFX= 1
UNET SFX= 1
UNET DSS MLevel= 4
UNET DZMax Abort= 100
UNET Convert EG Bridges=-1
UNET Use Existing IB Tables=-1
UNET Froude Reduction=False
UNET Froude Limit= 1
UNET Froude Power= 10
Instantaneous Interval=1HOUR
Write IC File= 0
Echo Input=False
Echo Output=False
Write Detailed= 0
Detailed Automatic Start=False, 10

--- lds_bald_mountain_crk.p02 (plan) ---

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Plan Title=Bald Mountain Creek - LDS - FW
Short Identifier=FW
Geom File=g01
Flow File=f02
Encroach Param=-1 ,1,1, 2
Encroach Node=8910.77
       1  5017.8 5072.77
Encroach Node=8699.07
       1    4979 5061.67
Encroach Node=8411.15
       1 4974.19 5019.34
Encroach Node=7955.74
       1 4980.11 5084.02
Encroach Node=7719.38
       1 4939.73 5106.04
Encroach Node=7663.30
       1 4935.87 5051.05
Encroach Node=7618.49
       1 4926.35 5085.92
Encroach Node=7533.09
       1 4913.53 5048.79
Encroach Node=7185.19
Encroach Node=7126.95
Encroach Node=7068.71
       1 4916.04 5075.39
Encroach Node=7016.90
       1    4900    5075

--- lds_bald_mountain_crk.f02 (steady flow) ---

Flow Title=Bald Mountain Creek - LDS - FW
Program Version=3.13
Number of Profiles= 2
Profile Names=100yr,FW
River Rch & RM=Bald Mountain Cr,Main            ,8911
    5600    5600
River Rch & RM=Bald Mountain Cr,Main            ,7956
    5690    5690
Boundary for River Rch & Prof#=Bald Mountain Cr,Main            , 1
Up Type= 0
Dn Type= 1
Dn Known WS=2420.94
Boundary for River Rch & Prof#=Bald Mountain Cr,Main            , 2
Up Type= 0
Dn Type= 1
Dn Known WS=2421.64
DSS Import GetInterval= 0
DSS Import GetPeak= 0
DSS Import FillOption= 0

--- lds_bald_mountain_crk.g01 (geometry) ---

Geom Title=Bald Mountain Creek - LDS - Geometry
Program Version=3.13

River Reach=Bald Mountain Cr,Main
Reach XY= 30
       990128.39      830976.363      990141.518      830961.261
      990169.154      830924.425      990207.521      830852.278
      990230.548      830803.159      990255.108      830734.089
      990259.711      830683.432      990265.851      830641.989
      990282.736      830603.615      990311.896      830568.315
      990339.531      830543.752      990410.137      830502.304
      990469.999      830493.101      990546.751      830496.168
      990606.613       830511.52      990644.984      830523.799
      990750.897      830543.752      990798.477      830549.892
      990850.666      830546.824      990922.816      830526.869
      990987.284      830497.704      991140.782      830417.885
      991197.572      830390.259      991255.908      830371.838
      991320.367      830362.631      991371.025      830364.161
      991420.148       830367.23      991504.567      830377.979
      991593.595      830384.118      991751.347       830396.37

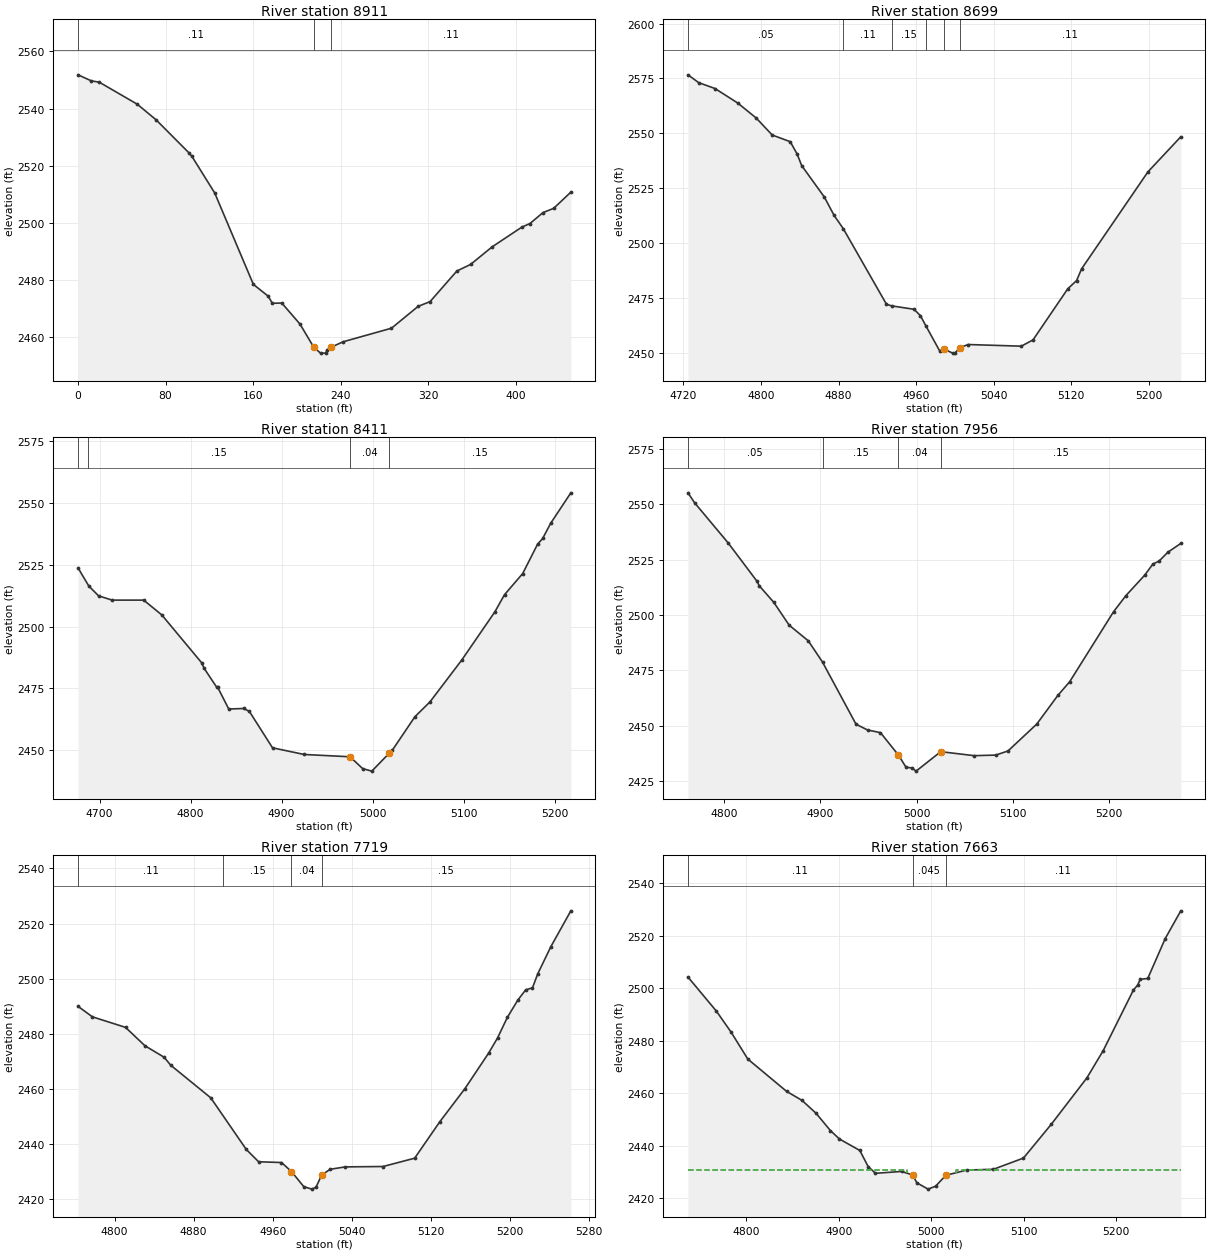
Type RM Length L Ch R = 1 ,8911    ,229.9,211.71,199.37
XS GIS Cut Line= 2
  990319.7240482  831095.5366104  989957.2032147  830828.4949436
#Sta/Elev= 30
       0 2551.83   12.02 2549.74    19.5 2549.23   54.18 2541.53   71.26  2536.1
  101.29 2524.55  104.06 2523.28  124.85 2510.51   160.2  2478.5  173.64 2474.42
  177.57  2471.9  186.14 2471.99  202.84  2464.6  215.27 2456.58  221.56 2454.46
  226.46 2454.46  227.21 2455.46  231.34 2456.56  242.35 2458.45  286.39 2463.18
  310.72 2470.82  321.63 2472.48   346.1 2483.18  358.68  2485.5  378.38 2491.65
  405.53 2498.56  412.91  2499.8  424.81 2503.63  434.59 2505.12  450.26 2510.78
#Mann= 3 ,-1 , 0
       0     .11       0  215.27     .04       0  231.34     .11       0
Bank Sta=215.27,231.34
Exp/Cntr=0.3,0.1

Type RM Length L Ch R = 1 ,8699    ,273.45,287.92,302.39
XS GIS Cut Line= 2
      990486.038      830900.081      990031.253      830673.737
#Sta/Elev= 30
 4724.82 2576.66 4735.92 2573.08 4752.74 2570.41 4776.19 2563.78 4795.17 2556.96
 4811.65 2549.23 4830.25 2546.18 4837.38 2540.51 4842.01 2535.31 4865.45 2520.92
 4875.44 2512.61 4884.98  2506.5 4929.41 2472.13 4934.67 2471.38 4957.82 2469.82
 4964.41 2466.91 4969.88 2462.41 4984.23 2450.88 4988.78 2451.68 4997.64 2449.84
    5000 2449.84 5005.04 2452.33 5013.61 2453.76 5068.43 2453.01 5080.51 2455.87
 5116.29 2479.13  5125.4  2482.9 5130.64  2488.3 5198.97 2532.45 5232.82 2548.42
#Mann= 6 ,-1 , 0
 4724.82     .05       0 4884.98     .11       0 4934.67     .15       0
 4969.88     .11       0 4988.78     .04       0 5005.04     .11       0
Bank Sta=4988.78,5005.04
Exp/Cntr=0.3,0.1

Type RM Length L Ch R = 1 ,8411    ,436.01,455.41,474.82
XS GIS Cut Line= 2
      990551.007      830793.196      990232.448      830355.178
#Sta/Elev= 30
 4676.28 2523.77 4688.06 2516.47 4698.81 2512.48 4713.66 2510.75 4748.43 2510.74
 4768.31 2504.76 4811.96 2485.46 4814.88 2483.12 4828.69 2475.47 4829.56 2475.59
  4841.9 2466.67 4858.49 2466.88 4864.61 2465.68 4889.99 2450.97 4924.79 2448.27
 4975.19 2447.34 4989.15 2442.53 4999.15 2441.53 5018.34  2448.8 5021.53  2449.9
 5046.47 2463.53 5063.12 2469.58 5098.13 2486.56 5134.39    2506    5145 2512.95
 5164.97  2521.5 5181.28 2533.35 5186.91 2535.69 5195.68 2541.82 5217.89 2554.17
#Mann= 4 ,-1 , 0
 4676.28     .05       04687.135     .15       0 4975.19     .04       0
 5018.34     .15       0
Bank Sta=4975.19,5018.34
Exp/Cntr=0.3,0.1

Type RM Length L Ch R = 1 ,7956    ,256.83,236.36,215.9
XS GIS Cut Line= 2
      990798.309      830786.909      990804.597      830275.538
#Sta/Elev= 30
  4762.8 2555.21 4769.73 2550.68 4804.48 2532.58 4834.35 2515.29  4836.7 2513.25
 4851.88 2505.71 4867.84 2495.39 4887.63 2488.35 4902.43 2478.71  4937.2 2450.65
 4949.13 2448.05 4962.58 2446.85 4981.11 2436.77 4989.14 2431.18 4995.24 2430.92
 4999.52 2429.46 5025.09 2438.25 5059.75 2436.45 5082.19  2436.7 5094.89 2438.57
 5124.73 2450.71 5146.66 2463.68 5158.93 2469.86 5204.45 2501.48 5217.22 2508.74
 5236.61 2517.92 5245.35 2523.07 5251.53 2524.31 5260.76 2528.35 5274.21 2532.34
#Mann= 4 ,-1 , 0
  4762.8     .05       0 4902.43     .15       0 4981.11     .04       0
 5025.09     .15       0
Bank Sta=4981.11,5025.09
Exp/Cntr=0.3,0.1

Type RM Length L Ch R = 1 ,7719    ,67.99,56.08,44.13
XS GIS Cut Line= 4
      991115.839      830693.816      991065.141        830531.2
      990998.182      830446.065      990912.091      830243.274
#Sta/Elev= 30
 4762.94 2489.98 4777.47 2486.18 4810.98 2482.37 4830.61 2475.72 4850.11 2471.53
 4856.75 2468.65 4897.28 2456.84 4933.28 2438.12 4945.76 2433.66 4968.93 2433.38
 4979.05 2430.12 4991.45 2424.65 4999.64 2423.74 5003.78 2424.38 5009.48 2428.74
    5018 2430.92 5033.47  2431.8 5071.78 2431.94 5103.74 2434.95 5129.28 2448.19
 5154.57 2460.12 5178.65 2473.03 5187.69 2478.53 5197.59 2485.96 5208.08 2492.18
 5216.17 2495.96 5223.06  2496.7 5228.46 2501.83 5241.66 2511.61  5261.9  2524.6
#Mann= 4 ,-1 , 0
 4762.94     .11       04910.165     .15       0 4979.05     .04       0
 5009.48     .15       0
Bank Sta=4979.05,5009.48
Exp/Cntr=0.5,0.3

Type RM Length L Ch R = 1 ,7663    ,45.99,44.81,43.67
XS GIS Cut Line= 4
      991177.646       830682.12      991120.622      830482.415
      991030.705      830425.978      990942.918       830225.24
#Sta/Elev= 30
  4736.9 2504.29 4767.62 2491.29 4783.49 2483.29 4801.61 2472.99 4843.54 2460.67
 4860.24 2457.22 4875.42 2452.31 4890.89 2445.72 4900.71 2442.49 4922.71 2438.12
 4931.74 2431.98 4939.66  2429.4 4967.84  2430.1 4980.03 2428.74  4984.4 2425.77
 4996.59 2423.36 5004.64 2424.46 5015.78 2428.64 5038.32 2430.63 5067.18 2430.93
 5099.71 2435.21 5129.82 2448.12 5168.32 2465.82 5185.97 2476.24 5218.66 2499.37
 5223.12 2501.17 5226.01 2503.44 5234.13 2503.76 5253.03 2518.99 5269.84 2529.57
#Mann= 3 ,-1 , 0
  4736.9     .11       0 4980.03    .045       0 5015.78     .11       0
#XS Ineff= 2 , 0
       0 4973.57 2430.67 5026.71       0 2430.67
Permanent Ineff=
       F       F
Bank Sta=4980.03,5015.78
Exp/Cntr=0.5,0.3

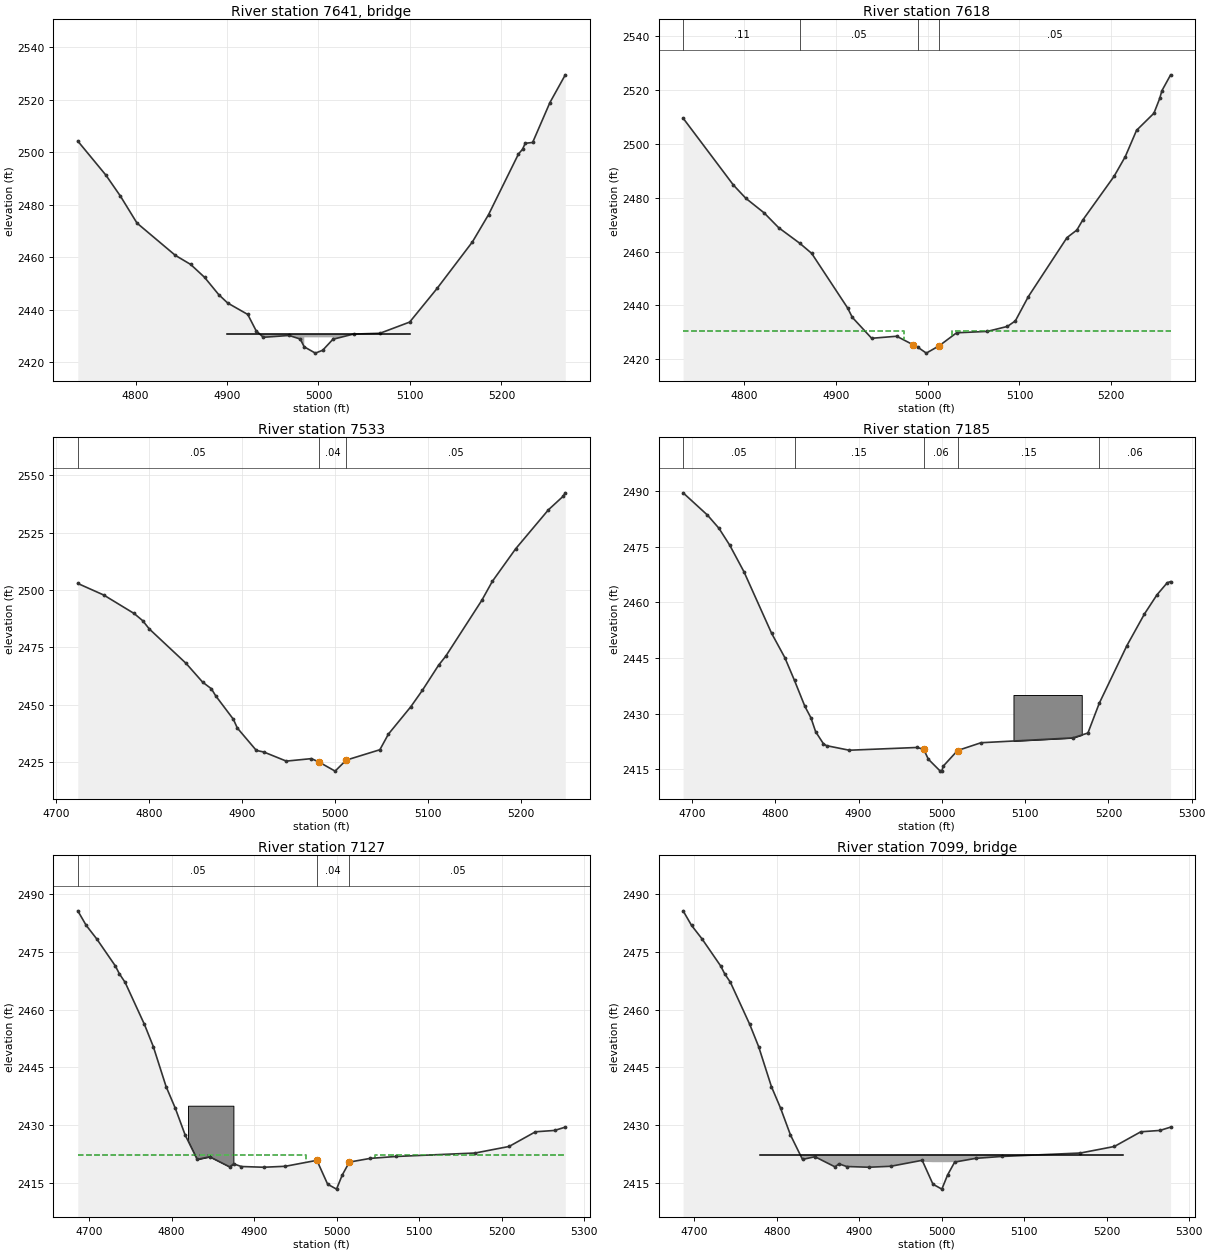
Type RM Length L Ch R = 3 ,7641    ,,,
BEGIN DESCRIPTION:
FBSTR 1860
END DESCRIPTION:
Bridge Culvert--1,0,-1,-1, 0
Deck Dist Width WeirC Skew NumUp NumDn MinLoCord MaxHiCord MaxSubmerge Is_Ogee
14,14,2.6,0, 7, 7, , , 0.95, 0, 0,0,,
    4900  4984.5  4984.5    5000  5015.5  5015.5    5100
 2430.68 2430.68 2430.68 2430.68 2430.68 2430.68 2430.68
       0       0 2429.38 2429.38 2429.38       0       0
    4900  4984.5  4984.5    5000  5015.5  5015.5    5100
 2430.68 2430.68 2430.68 2430.68 2430.68 2430.68 2430.68
       0       0 2429.38 2429.38 2429.38       0       0
BR Coef=-1 , 0 , 0 ,, 0 ,,,0.8,0,,0,
WSPro=,,,, 1 ,,,, 0 ,,,, 0 ,,,,-1 ,-1 ,-1 , 0 , 0 , 0 , 0 , 0
BC Design=,, 0 ,, 0 ,,,,,,

Type RM Length L Ch R = 1 ,7618    ,69.04,85.4,101.76
XS GIS Cut Line= 4
      991212.452      830669.902      991148.363      830452.761
      991050.793      830395.367      990973.311       830219.36
#Sta/Elev= 30
 4733.04 2509.54 4787.94 2484.69 4801.44 2479.79 4821.41 2474.37 4837.38 2468.84
 4860.36 2463.07 4873.33 2459.32 4912.55 2439.04 4917.61 2435.58 4938.76 2427.79
 4966.09 2428.55  4984.3 2425.33 4989.47  2424.4 4998.38 2422.28 5012.58 2425.04
 5031.43 2429.83 5064.99 2430.35 5086.92  2432.2 5095.55 2434.26 5109.68 2443.25
 5151.88 2465.18 5162.69    2468 5168.88  2471.6 5203.24 2487.93 5215.51 2495.28
 5227.78 2505.02 5246.74 2511.37 5253.03 2516.85 5255.41 2519.71 5264.95 2525.63
#Mann= 4 ,-1 , 0
 4733.04     .11       0 4860.36     .05       0 4989.47    .045       0
 5012.58     .05       0
#XS Ineff= 2 , 0
       0 4973.57 2430.67 5026.71       0 2430.67
Permanent Ineff=
       F       F
Bank Sta=4984.3,5012.58
Exp/Cntr=0.5,0.3

Type RM Length L Ch R = 1 ,7533    ,329.09,347.9,366.72
XS GIS Cut Line= 4
      991304.283      830645.031      991227.757      830454.675
      991154.102      830337.017      991080.446      830172.488
#Sta/Elev= 30
 4723.31 2502.85  4751.2 2497.81 4783.88 2489.75 4793.01 2486.65 4800.21 2483.01
 4839.65 2468.04 4857.59  2459.8 4866.94 2456.93 4871.51  2453.9 4890.57 2443.64
 4894.88 2439.79  4915.3 2430.03 4923.27 2429.35 4947.52 2425.37 4974.49 2426.45
 4982.33 2425.05 5000.01    2421 5011.89 2425.79 5048.14 2430.33  5057.3 2437.13
 5081.34 2449.05 5093.93 2456.29 5111.22 2467.16 5119.13 2471.21 5157.67 2495.44
 5169.07 2503.75 5194.13 2517.95 5229.38 2534.97 5245.02  2540.8 5247.55 2542.38
#Mann= 3 ,-1 , 0
 4723.31     .05       0 4982.33     .04       0 5011.89     .05       0
Bank Sta=4982.33,5011.89
Exp/Cntr=0.3,0.1

Type RM Length L Ch R = 1 ,7185    ,57.33,58.24,59.65
XS GIS Cut Line= 2
      991511.857      830689.989      991550.695       830105.78
#Sta/Elev= 30
 4689.23 2489.53 4718.46 2483.53 4732.18 2479.99 4745.09 2475.46 4762.36 2468.22
 4795.51 2451.64 4811.37 2445.09 4823.02 2438.91 4835.48 2431.94 4842.84  2428.8
 4848.39  2425.1  4857.7 2421.86 4861.45 2421.33 4888.72  2420.1 4970.15 2420.84
 4978.15 2420.36 4983.71 2417.69 4998.08 2414.46    5000 2414.46 5001.46 2415.76
 5018.88 2420.02 5047.04 2422.12 5157.39 2423.43  5175.4 2424.74 5189.01 2432.76
 5222.25 2448.33 5243.32 2456.86 5258.37 2462.03 5270.69 2465.28 5274.73 2465.59
#Mann= 5 ,-1 , 0
 4689.23     .05       0 4823.02     .15       0 4978.15     .06       0
 5018.88     .15       0 5189.01     .06       0
#Block Obstruct= 1 ,-1
    5086    5168    2435
Bank Sta=4978.15,5018.88
Exp/Cntr=0.5,0.3

Type RM Length L Ch R = 1 ,7127    ,57.24,58.24,58.8
XS GIS Cut Line= 4
       991519.51      830689.033      991587.426      830416.412
      991593.165      830357.105      991657.255      830115.094
#Sta/Elev= 30
  4686.4 2485.67 4696.59 2481.89 4709.32 2478.38 4732.01 2471.31 4736.78 2469.31
 4743.78 2467.06 4767.21 2456.12  4777.9 2450.39 4793.43 2439.97 4804.55 2434.36
 4816.51  2427.4 4831.11 2421.03 4846.24 2421.73 4870.56 2419.09 4875.24 2419.88
 4884.63 2419.19 4911.77    2419 4938.05 2419.25 4976.19  2420.8 4989.23 2414.59
 5000.01 2413.31 5006.96 2416.99 5015.56 2420.34 5041.05 2421.31 5072.31  2421.8
 5168.02  2422.7 5209.13  2424.4 5241.14 2428.22 5264.33 2428.57 5277.29 2429.43
#Mann= 3 ,-1 , 0
  4686.4     .05       0 4976.19     .04       0 5015.56     .05       0
#XS Ineff= 2 , 0
       0 4963.07  2422.3  5046.5       0  2422.3
Permanent Ineff=
       F       F
#Block Obstruct= 1 ,-1
    4820    4875    2435
Bank Sta=4976.19,5015.56
Exp/Cntr=0.5,0.3

Type RM Length L Ch R = 3 ,7099    ,,,
BEGIN DESCRIPTION:
FBSTR 1338
END DESCRIPTION:
Bridge Culvert--1,0,-1,-1, 0
Deck Dist Width WeirC Skew NumUp NumDn MinLoCord MaxHiCord MaxSubmerge Is_Ogee
16,30,2.6,0, 7, 7, , , 0.95, 0, 0,0,,
    4780    4977    4977    4997    5017    5017    5220
 2422.31 2422.31 2422.31 2422.31 2422.31 2422.31 2422.31
       0       0 2420.31 2420.31 2420.31       0       0
    4780    4977    4977    4997    5017    5017    5220
 2422.31 2422.31 2422.31 2422.31 2422.31 2422.31 2422.31
       0       0 2420.31 2420.31 2420.31       0       0
BR Coef=-1 , 0 , 0 ,, 0 ,,,0.8,0,,0,
WSPro=,,,, 1 ,,,, 0 ,,,, 0 ,,,,-1 ,-1 ,-1 , 0 , 0 , 0 , 0 , 0
BC Design=,, 0 ,, 0 ,,,,,,

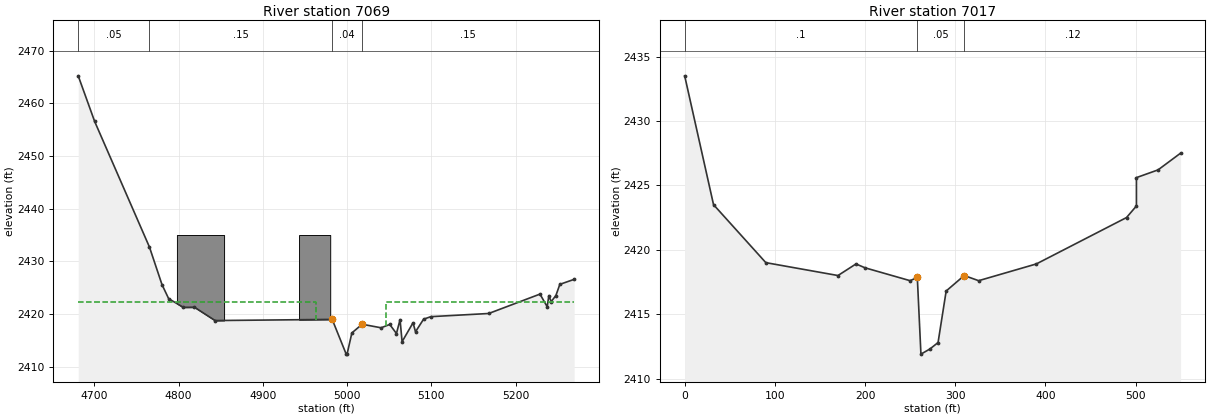
Type RM Length L Ch R = 1 ,7069    ,50.87,51.81,52.67
XS GIS Cut Line= 4
      991557.772      830693.816      991643.863      830425.021
      991652.472      830359.018      991722.301      830129.442
#Sta/Elev= 30
 4680.82 2465.21 4700.34 2456.55 4765.39 2432.72 4780.33 2425.57 4788.18 2422.93
  4805.5 2421.28 4818.85  2421.3 4843.31 2418.77 4982.34 2418.99 4998.96  2412.4
    5000  2412.4  5005.7 2416.42 5017.85 2418.07 5040.39  2417.4 5050.67 2418.03
 5058.63 2416.31 5062.91 2418.95 5065.31 2414.76 5078.32 2418.35 5081.24 2416.64
 5090.85 2419.03 5099.45 2419.51 5168.14 2420.11 5229.01 2423.79 5237.59 2421.39
 5239.56  2423.5 5242.31 2422.36 5247.91 2423.52  5252.6 2425.64 5269.59 2426.59
#Mann= 4 ,-1 , 0
 4680.82     .05       0 4765.39     .15       0 4982.34     .04       0
 5017.85     .15       0
#XS Ineff= 2 , 0
       0 4963.07  2422.3  5046.5       0  2422.3
Permanent Ineff=
       F       F
#Block Obstruct= 2 ,-1
    4798    4854    2435    4943    4980    2435
Bank Sta=4982.34,5017.85
Exp/Cntr=0.5,0.3

Type RM Length L Ch R = 1 ,7017    ,53.71,51.21,48.7
BEGIN DESCRIPTION:
cross section from hec-2 model, lidar topo formed a v shape but the hec-2 model represented a more trapezoidal bottom
END DESCRIPTION:
XS GIS Cut Line= 2
       991647.83      830715.926        991745.4      830114.247
#Sta/Elev= 20
       0  2433.5      32  2423.5      90    2419     170    2418     190  2418.9
     200  2418.6     250  2417.6     258 2417.85     262  2411.9     272  2412.3
     281  2412.8     290  2416.8     310    2418     326  2417.6     390  2418.9
     490  2422.5     501  2423.4     501  2425.6     525  2426.2     550  2427.5
#Mann= 3 ,-1 , 0
       0      .1       0     258     .05       0     310     .12       0
Bank Sta=258,310
Exp/Cntr=0.3,0.1
Stream Node=Bald Mountain Cr,Main            , 0 , 0 ,Upstream end
Stream Node=Bald Mountain Cr,Main            , 0 , 1 ,Downstream end

Chan Stop Cuts=-1
Use User Specified Reach Order=0
User Specified Reach Order=Bald Mountain Cr,Main