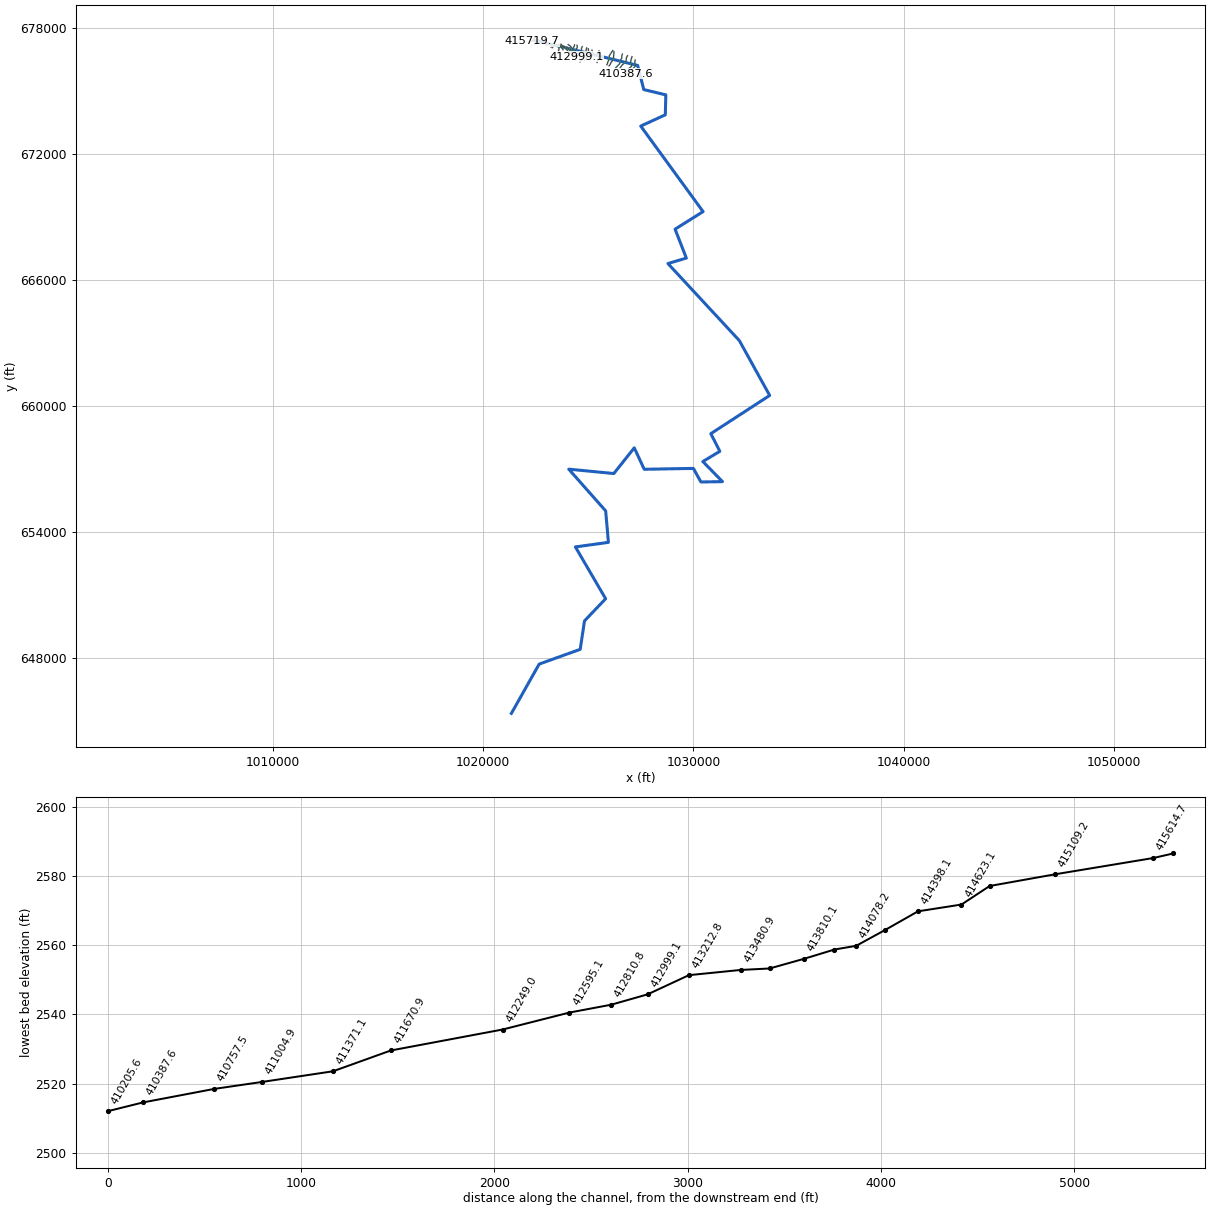
--- lds_broad_rvr.prj (project) ---

Proj Title=Upper_Broad 3-06-07
Current Plan=p01
Default Exp/Contr=0.3,0.1
English Units
Geom File=g05
Flow File=f02
Plan File=p01
Plan File=p03
Y Axis Title=Elevation
X Axis Title(PF)=Main Channel Distance
X Axis Title(XS)=Station
BEGIN DESCRIPTION:
& RNCFPM - Upper Broad River 03-01-07
END DESCRIPTION:
DSS File=dss
DSS Export Rating Curves= 0
DSS Export Rating Curve Sorted= 0
DSS Export Volume Flow Curves= 0
DXF OffsetX= 0
DXF OffsetY= 0
DXF ScaleX= 1
DXF ScaleY= 10

--- lds_broad_rvr.p01 (plan) ---

Plan Title=Upper_Broad 3-06-07
Program Version=3.13
Short Identifier=Upper_Broad
Geom File=g05
Flow File=f02
Subcritical Flow
K Sum by GR= 0
Std Step Tol= 0.01
Critical Tol= 0.01
Num of Std Step Trials= 20
Max Error Tol= 0.3
Flow Tol Ratio= 0.001
Split Flow NTrial= 30
Split Flow Tol= 0.02
Split Flow Ratio= 0.02
Log Output Level= 0
Friction Slope Method= 0
Unsteady Friction Slope Method= 2
Unsteady Bridges Friction Slope Method= 1
Parabolic Critical Depth
Global Vel Dist= 0 , 0 , 0
Global Log Level= 0
CheckData=True
Encroach Param=-1 ,10,10, 2
Encroach River=Broad_Creek
Encroach Reach=Main_Branch
Encroach Node=415719.7
       4      .7
Encroach Node=415614.7
       4      .7
Encroach Node=415109.2
       1  251.58  298.52
Encroach Node=414768.8
       1  146.28  207.91
Encroach Node=414623.1
       1      35   92.83
Encroach Node=414398.1
       1  173.18   231.6
Encroach Node=414226.6
       1  246.01  300.61
Encroach Node=414078.2
       1     183   257.9
Encroach Node=413965.7
       1   328.8     390
Encroach Node=413810.1
       1     130  179.52
Encroach Node=413630.2
       1   69.26  110.46
Encroach Node=413480.9
       4      .7
Encroach Node=413212.8
       4      .7
Encroach Node=412999.1
       1  114.29     320
Encroach Node=412810.8
       1  191.94  255.28
Encroach Node=412595.1
       4      .7
Encroach Node=412249.0
       4      .7
Encroach Node=411670.9
       4      .7
Encroach Node=411371.1
       4      .7
Encroach Node=411004.9
       4      .7
Encroach Node=410757.5
       4      .7
Encroach Node=410387.6
       1     360     525
Encroach Node=410205.6
       1     185     400
Encroach Node=410149.3
       1     200     390
Encroach Node=410120.8
       4      .7
Encroach Node=409912.1
       4      .7
Encroach Node=409605.7
       1   32.05   92.83
Encroach Node=409375.
       4      .7
Encroach Node=408974.0
       1   75.97     122
Encroach Node=408548.5
       1    63.3     116
Encroach Node=408231.8
       1   98.25  154.12
Encroach Node=407970.8
       4      .7
Encroach Node=407813.7
       1      61     100
Encroach Node=407676.7
       1    59.6     120
Encroach Node=407311.4
       1   69.47  109.41
Encroach Node=407017.7
       4      .7
Encroach Node=406644.3
       4      .7
Encroach Node=406535.2
       1      36     100
Encroach Node=406375.9
       1      44      75
Encroach Node=405949.3
       1      41     150
Encroach Node=405771.1
       1      45     100
Encroach Node=405690.0
       1      30      94
Encroach Node=405661.3
       1   147.5     187
Encroach Node=405576.6
       1     220  317.98
Encroach Node=405196.3
       1     425  581.32
Encroach Node=404656.3
       1  435.54     482
Encroach Node=404178.5
       1     375     460
Encroach Node=404113.8
       1     330     450
Encroach Node=404099.4
       1     365     440
Encroach Node=403667.4
       4      .7
Encroach Node=403258.9
       4      .7
Encroach Node=402888.4
       4      .7
Encroach Node=402455.3
       4      .7
Encroach Node=402032.0
       4      .7
Encroach Node=401546.5
       1     180     275
Encroach Node=401285.1
       1     100     430
Encroach Node=401217.2
       1      80     475
Encroach Node=401199.0
       1     100     400
Encroach Node=401115.1
       4      .7
Encroach Node=400950.5
       4      .7
Encroach Node=400096.6
       1  218.73  497.98
Encroach Node=400024.5
       1  247.23  607.57
Encroach Node=399896.7
       1   257.6  648.05
Encroach Node=399861.8
       1   288.5  658.71
Encroach Node=399788.7
       1  251.37  497.81
Encroach Node=399557.0
       4      .7
Encroach Node=399166.3
       4      .7
Encroach Node=398833.2
       1     100  174.76
Encroach Node=398436.3
       1   47.19      96
Encroach Node=398234.6
       1    53.7  101.97
Encroach Node=398047.8
       1   53.11   99.16
Encroach Node=397615.9
       1     192     240
Encroach Node=397368.3
       4      .7
Encroach Node=397003.9
       1      55      95
Encroach Node=396622.9
       1   36.26     126
Encroach Node=396484.8
       1     105   164.2
Encroach Node=396256.3
       1     101     155
Encroach Node=396046.8
       1      55     105
Encroach Node=395583.4
       1     198     228
Encroach Node=395400.0
       4      .7
Encroach Node=395068.7
       4      .7
Encroach Node=394625.4
       4      .7
Encroach Node=394162.2
       1  205.64  261.04
Encroach Node=393760.0
       4      .7
Encroach Node=393541.2
       4      .7
Encroach Node=393300.6
       4      .7
Encroach Node=392906.5
       4      .7
Encroach Node=392435.7
       1  123.05  193.95
Encroach Node=392201.0
       4      .7
Encroach Node=392124.1
       1      60     195
Encroach Node=392105.6
       4      .7
Encroach Node=392018.7
       4      .7
Encroach Node=391614.2
       4      .7
Encroach Node=391162.9
       1      70     180
Encroach Node=391138.8
       1     122     210
Encroach Node=391126.
       4      .7
Encroach Node=391081.9
       1     175     290
Encroach Node=390763.2
       1      65     135
Encroach Node=390700.5
       1      60     140
Encroach Node=390671.1
       1   60.52     125
Encroach Node=390658.8
       4      .7
Encroach Node=390644.6
       1      45     150
Encroach Node=390570.2
       1   46.02      95
Encroach Node=390187.4
       4      .7
Encroach Node=389970.4
       4      .7
Encroach Node=389680.2
       4      .7
Encroach Node=389299.4
       1   532.3  683.49
Encroach Node=388771.8
       1     295     375
Encroach Node=388654.5
       1  265.92   338.2
Encroach Node=388626.5
       1  268.97   333.8
Encroach Node=388443.6
       4      .7
Encroach Node=388308.2
       4      .7
Encroach Node=387899.9
       1      80     205
Encroach Node=387744.3
       1      50     158
Encroach Node=387695.6
       1   76.44  133.53
Encroach Node=387667.4
       1      75     125
Encroach Node=387569.9
       1      60     165
Encroach Node=387355.3
       1      70     140
Encroach Node=387323.0
       1      89     155
Encroach Node=387307.5
       1  115.66  148.12
Encroach Node=387269.9
       4      .7
Encroach Node=387178.3
       1  107.71  169.48
Encroach Node=387088.8
       1     135     210
Encroach Node=387071.2
       1   92.18  153.66
Encroach Node=386949.0
       4      .7
Encroach Node=386634.8
       1   25.31   71.05
Encroach Node=386421.3
       4      .7
Encroach Node=386233.9
       1      92     144
Encroach Node=386047.3
       1     157     229
Encroach Node=386002.1
       1     155  236.77
Encroach Node=385990.7
       4      .7
Encroach Node=385894.5
       4      .7
Encroach Node=385556.4
       1      98  141.75
Encroach Node=385154.4
       1      60     109
Encroach Node=384454.3
       1   67.84     140
Encroach Node=384381.1
       1   80.18   167.4
Encroach Node=384360.3
       1   82.48     175
Encroach Node=384255.9
       1   85.46     200
Encroach Node=383996.0
       4      .7
Encroach Node=383789.0
       4      .7
Encroach Node=383502.5
       4      .7
Encroach Node=383101.9
       4      .7
Encroach Node=382723.4
       4      .7
Encroach Node=382328.0
       4      .7
Encroach Node=382140.3
       4      .7
Encroach Node=381643.4
       1      60     130
Encroach Node=381397.3
       1      55     120
Encroach Node=381173.0
       1      88   122.5
Encroach Node=380869.4
       1  261.25     315
Encroach Node=380552.4
       4      .7
Encroach Node=380219.
       1     240     310
Encroach Node=379752.4
       1  123.61     370
Encroach Node=379589.0
       1   190.5   320.5
Encroach Node=379458.8
       1  187.87  330.17
Encroach Node=379318.0
       1      74   229.5
Encroach Node=378708.8
       4      .7
Encroach Node=378365.5
       4      .7
Encroach Node=377905.9
       1   32.45  101.76
Encroach Node=377604.4
       4      .7
Encroach Node=377416.1
       1   46.35  119.34
Encroach Node=377293.6
       1      60     106
Encroach Node=377160.3
       1    60.5   105.5
Encroach Node=377053.4
       1   76.08  131.64
Encroach Node=376726.0
       4      .7
Encroach Node=376262.9
       4      .7
Encroach Node=375865.2
       4      .7
Encroach Node=375504.9
       4      .7
Encroach Node=375113.6
       4      .7
Encroach Node=374717.9
       1   114.7     240
Encroach Node=374334.8
       1     120     400
Encroach Node=374146.6
       1  208.75  374.75
Encroach Node=373986.0
       1    88.7   274.7
Encroach Node=373868.8
       1     170     410
Encroach Node=373557.9
       1     320     520
Encroach Node=373146.9
       4      .7
Encroach Node=372673.9
       4      .7
Encroach Node=372309.3
       1   57.47  120.83
Encroach Node=372060.8
       1      76     157
Encroach Node=371853.8
       1     108     230
Encroach Node=371669.0
       1      65     135
Encroach Node=371450.2
       4      .7
Encroach Node=371344.3
       4      .7
Encroach Node=371322.7
       4      .7
Encroach Node=371153.0
       1  140.95   207.9
Encroach Node=370544.0
       4      .7
Encroach Node=370070.4
       4      .7
Encroach Node=369570.8
       1     410     683
Encroach Node=369075.6
       4      .7
Encroach Node=368900.3
       4      .7
Encroach Node=368466.5
       4      .7
Encroach Node=368113.3
       1  587.83  662.17
Encroach Node=367883.4
       1     550     675
Encroach Node=367852.9
       1     450   582.2
Encroach Node=367654.6
       4      .7
Encroach Node=367209.0
       1   223.7     323
Encroach Node=366699.7
       4      .7
Encroach Node=366155.3
       4      .7
Encroach Node=365635.9
       4      .7
Encroach Node=365236.2
       1   34.17  190.64
Encroach Node=364698.7
       4      .7
Encroach Node=364268.3
       4      .7
Encroach Node=363858.4
       4      .7
Encroach Node=363684.7
       1   61.17     270
Encroach Node=363408.7
       1   117.4  193.78
Encroach Node=363020.8
       1  114.84  164.13
Encroach Node=362773.1
       4      .7
Encroach Node=362427.5
       4      .7
Encroach Node=362077.2
       1      35     175
Encroach Node=361826.0
       1   81.58     152
Encroach Node=361588.4
       1      85     140
Encroach Node=361371.5
       1     160     275
Encroach Node=360929.8
       4      .7
Encroach Node=360679.6
       1     270     530
Encroach Node=360566.3
       1  207.98  301.11
Encroach Node=360540.6
       1     189     268
Encroach Node=360331.9
       1  470.35  595.26
Encroach Node=359828.0
       4      .7
Encroach Node=359252.5
       4      .7
Encroach Node=358682.9
       4      .7
Encroach Node=358318.7
       4      .7
Encroach Node=358039.9
       4      .7
Encroach Node=357537.1
       4      .7
Encroach Node=357244.3
       1   49.35     118
Encroach Node=356815.6
       1      42     113
Encroach Node=356517.3
       1      52     114
Encroach Node=356231.8
       4      .7
Encroach Node=355905.2
       1   44.66  122.66
Encroach Node=355625.8
       1      76     126
Encroach Node=355407.8
       4      .7
Encroach Node=355095.1
       1     175  246.44
Encroach Node=354570.6
       4      .7
Encroach Node=354332.6
       1      83     132
Encroach Node=354075.7
       4      .7
Encroach Node=353583.8
       4      .7
Encroach Node=353377.1
       1      59     124
Encroach Node=353057.8
       4      .7
Encroach Node=352777.5
       4      .7
Encroach Node=352552.3
       4      .7
Encroach Node=352152.
       1      92   274.1
BEGIN DESCRIPTION:
Q100 + Encroachment
END DESCRIPTION:
Computation Interval=1HOUR
Output Interval=1HOUR
Run HTab= 0
Run UNet= 0
Run PostProcess= 0
UNET Theta= 1
UNET Theta Warmup= 1
UNET ZTol= 0.02
UNET ZSATol= 0.05
UNET MxIter= 20
UNET MaxInSteps= 0
UNET DtIC= 0
UNET DtMin= 0
UNET MaxCRTS= 20
UNET WFStab= 2
UNET SFStab= 1
UNET WFX= 1
UNET SFX= 1
UNET DSS MLevel= 4
UNET DZMax Abort= 100
UNET Convert EG Bridges=-1
UNET Use Existing IB Tables=-1
UNET Froude Reduction=False
UNET Froude Limit= 1
UNET Froude Power= 10
Instantaneous Interval=1HOUR
DSS File=dss
Write IC File= 0
Echo Input=False
Echo Output=False
Write Detailed= 0
Detailed Automatic Start=False, 10

--- lds_broad_rvr.p03 (plan) ---

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Plan Title=Upper_Broad 3-01-07
Short Identifier=Plan 3-01-07
Geom File=g05
Flow File=f02
       1  336.26     378
       1      30      90
       1     155     175
       1     270  317.98
       1  246.18  607.57
       1  252.03  648.05
       1  287.47  658.71
       1      80     200
       1   86.44  123.53
       1   79.53  116.52
       1  103.46   134.2
       1  158.02  225.05
       1     170  236.77
       1      58     109
       1   77.22     175
       1     195     370
       1   188.5   290.5
       1  207.87  309.87
       1  149.55     300
       1  227.74  355.14
       1     340     500
       1     120     610
       1      35  232.78

--- lds_broad_rvr.f02 (steady flow) ---

Flow Title=Upper_Broad 3-01-07
Program Version=3.13
Number of Profiles= 2
Profile Names=100 YR,100 FW
River Rch & RM=Broad_Creek,Main_Branch     ,415719.7
    1530    1530
River Rch & RM=Broad_Creek,Main_Branch     ,412595.1
    1860    1860
River Rch & RM=Broad_Creek,Main_Branch     ,411004.9
    2230    2230
River Rch & RM=Broad_Creek,Main_Branch     ,409375.
    2450    2450
River Rch & RM=Broad_Creek,Main_Branch     ,403667.4
    2670    2670
River Rch & RM=Broad_Creek,Main_Branch     ,400096.6
    2890    2890
River Rch & RM=Broad_Creek,Main_Branch     ,397368.3
    3070    3070
River Rch & RM=Broad_Creek,Main_Branch     ,389299.4
    3200    3200
River Rch & RM=Broad_Creek,Main_Branch     ,387744.3
    3650    3650
River Rch & RM=Broad_Creek,Main_Branch     ,385556.4
    3810    3810
River Rch & RM=Broad_Creek,Main_Branch     ,378708.8
    4400    4400
River Rch & RM=Broad_Creek,Main_Branch     ,377293.6
    4900    4900
River Rch & RM=Broad_Creek,Main_Branch     ,372673.9
    5130    5130
River Rch & RM=Broad_Creek,Main_Branch     ,368900.3
    5240    5240
River Rch & RM=Broad_Creek,Main_Branch     ,360929.8
    6640    6640
River Rch & RM=Broad_Creek,Main_Branch     ,360331.9
    6760    6760
River Rch & RM=Broad_Creek,Main_Branch     ,359252.5
    6890    6890
River Rch & RM=Broad_Creek,Main_Branch     ,355095.1
    7030    7030
River Rch & RM=Broad_Creek,Main_Branch     ,352152.
    7060    7060
Boundary for River Rch & Prof#=Broad_Creek,Main_Branch     , 1
Up Type= 3
Up Slope=0.0098
Dn Type= 1
Dn Known WS=1721.46
Boundary for River Rch & Prof#=Broad_Creek,Main_Branch     , 2
Up Type= 3
Up Slope=0.0098
Dn Type= 1
Dn Known WS=1722.41
DSS Import GetInterval= 0
DSS Import GetPeak= 0
DSS Import FillOption= 0

--- lds_broad_rvr.g05 (geometry) ---

Geom Title=Upper_Broad 3-06-07
Program Version=3.13

River Reach=Broad_Creek     ,Main_Branch
Reach XY= 30
 1022445.0625621  677410.9376068 1027348.6875762  676207.1875507
 1027637.7501529  675059.6250918 1028689.6225494  674806.2977673
 1028664.3125573  673857.6876034 1027495.4375981  673321.5000951
  1030461.625071  669251.6875531 1029129.0626441  668414.5625233
  1029665.437602  667039.4375689 1028789.3751192  666779.2500678
 1032185.8126023  663114.6876091 1033631.2500991  660503.0000527
 1030831.4375876  658683.6876529 1031258.5000771  657843.3751023
 1030450.3750388  657358.1250894 1031386.1251563  656400.6876329
 1030359.1876408  656384.1875897 1030000.0000924  657030.3751035
 1027661.8750629  656988.8750728  1027186.812555  658009.1875636
 1026214.1251229  656786.6875548 1024070.5001202  656993.4375467
 1025826.2501603  655007.7500645 1025956.8125954  653511.1876228
 1024386.5000771  653293.1875987 1025824.3125557  650827.8751045
 1024818.9376146  649774.6251517 1024614.9376501  648420.5000597
 1022660.9375623  647717.3750899 1021339.9701318  645372.3610385

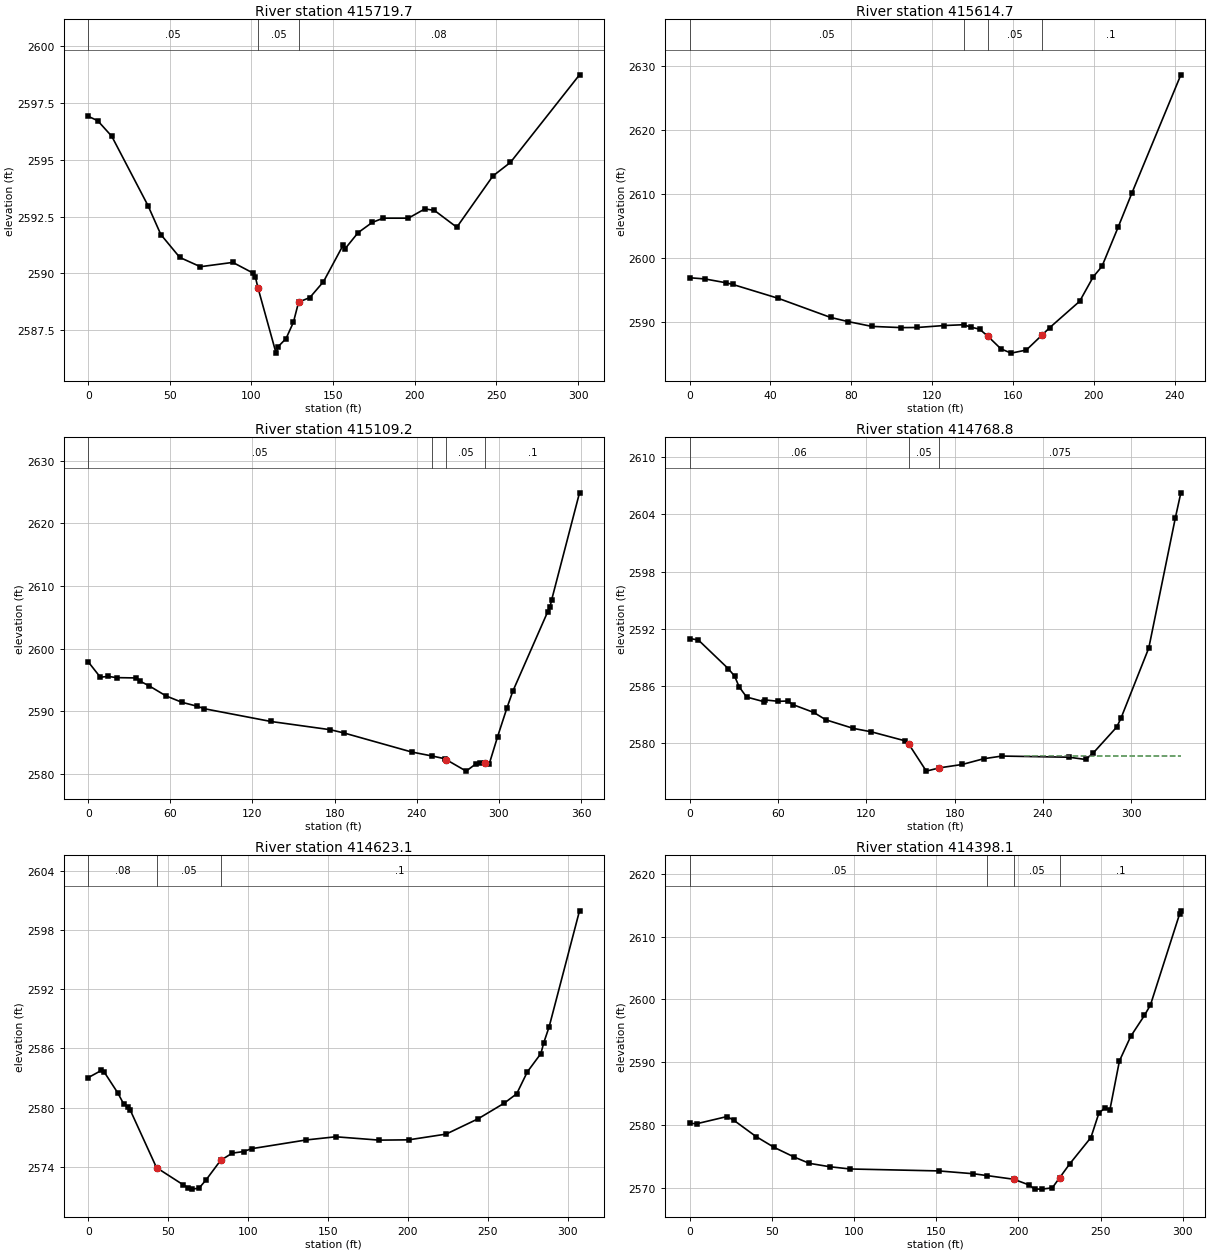
Type RM Length L Ch R = 1 ,415719.7,45.71,105.02,211.98
XS GIS Cut Line= 6
 1022559.4922559  677455.3312561 1022519.9957232  677415.8347537
 1022461.3151646  677378.5951527 1022367.6519671  677396.6507278
 1022331.5408774  677384.2375275  1022301.072102  677358.2826459
#Sta/Elev= 30
       0 2596.92    5.77 2596.73   14.42 2596.04   36.63 2592.98   44.46 2591.71
   56.06  2590.7    68.7 2590.29   88.56 2590.48  100.95 2590.01  102.32 2589.85
     104 2589.35  115.04 2586.48  116.38 2586.77  121.15 2587.12  125.67 2587.84
  128.86 2588.73  135.74 2588.93  144.09 2589.63  156.05 2591.23  157.18 2591.07
  165.28 2591.79   173.9 2592.24  180.62 2592.43  196.09 2592.43  206.21 2592.84
  212.09 2592.77  225.74 2592.03  247.86 2594.29  258.62 2594.89  300.91 2598.75
#Mann= 3 , 0 , 0
       0     .05       0     104     .05       0  128.86     .08       0
#XS Ineff= 2 , 0
       0                  206.21       0 2592.84
Permanent Ineff=
       F       F
Bank Sta=104,128.86
Exp/Cntr=0.3,0.1

Type RM Length L Ch R = 1 ,415614.7,393.61,505.51,513.68
XS GIS Cut Line= 6
 1022583.4716677  677454.6121192 1022576.1375551  677414.4902198
 1022553.7038078  677373.5054712 1022529.1129526  677319.5781656
 1022523.0730987  677302.7528324 1022507.5420546  677225.9603701
#Sta/Elev= 26
       0  2596.9    7.62 2596.71   17.93 2596.12   21.41 2595.85   43.86 2593.69
   69.77 2590.71   78.43 2590.06   90.21 2589.31  104.81 2589.12  112.72 2589.14
  125.75 2589.44  135.56 2589.57  139.38 2589.18   143.5 2588.88  147.67 2587.76
  154.09  2585.8  159.12 2585.14  166.65 2585.62  174.22  2587.9  178.21 2589.11
  193.05 2593.23   199.8 2597.06  204.08 2598.67  212.22 2604.89  218.87 2610.09
  243.12 2628.55
#Mann= 4 ,-1 , 0
       0     .05       0  135.56     .08       0  147.67     .05       0
  174.22      .1       0
Bank Sta=147.67,174.22
Exp/Cntr=0.3,0.1

Type RM Length L Ch R = 1 ,415109.2,447.55,340.4,240.57
XS GIS Cut Line= 6
 1022938.6589094  677497.0847509 1022926.2457394  677451.9458434
 1022927.3741901  677433.8902985 1023001.8533617   677289.445849
 1023019.9089066  677213.8382266 1023012.0096303  677161.9284936
#Sta/Elev= 30
       0 2597.91    8.86 2595.45   14.41 2595.59   20.66 2595.39   35.13 2595.34
   38.01 2594.81   44.65 2594.06   56.75 2592.48   68.49 2591.45   79.19 2590.85
   84.75 2590.43  133.54 2588.39  176.77 2587.08  186.48 2586.58   236.3 2583.52
  251.08 2582.89  260.27 2582.46  261.58  2582.3  276.08 2580.47  283.08 2581.61
  286.12 2581.78  290.16 2581.69  292.89 2581.58  299.04 2585.96   305.9 2590.57
  310.13  2593.2  335.57 2605.86  337.33 2606.66  338.54  2607.8  358.89 2624.88
#Mann= 4 ,-1 , 0
       0     .05       0  251.08     .08       0  261.58     .05       0
  290.16      .1       0
Bank Sta=261.58,290.16
Exp/Cntr=0.3,0.1

Type RM Length L Ch R = 1 ,414768.8,224.17,145.66,74.74
XS GIS Cut Line= 6
 1023382.1484963  677345.8694758 1023357.3221259  677214.9666773
 1023342.6519636  677182.2410004 1023305.4123929  677157.4145998
 1023263.6589284  677148.3868122 1023220.7769829  677086.3208409
#Sta/Elev= 30
       0 2590.97    5.89 2590.83    26.3 2587.81   30.64 2587.02   33.61 2585.92
   38.71 2584.84   50.73 2584.34   51.55 2584.53   60.35 2584.39   66.58 2584.42
   70.42 2584.03   84.38 2583.22   92.55 2582.45  111.22 2581.55  123.48 2581.19
  146.02 2580.26  148.88  2579.9  160.78 2577.07  169.57 2577.41  185.21 2577.77
  199.79 2578.37  212.09 2578.65   257.7 2578.53  269.03 2578.29  274.07 2578.96
  290.14  2581.7  293.08 2582.66  311.86 2589.98  329.91 2603.63  333.64 2606.25
#Mann= 3 , 0 , 0
       0     .06       0  148.88     .05       0  169.57    .075       0
#XS Ineff= 2 , 0
       0                  226.84       0 2578.68
Permanent Ineff=
       F       F
Bank Sta=148.88,169.57
Exp/Cntr=0.3,0.1

Type RM Length L Ch R = 1 ,414623.1,86.33,224.99,393.23
XS GIS Cut Line= 6
 1023549.1623844  677173.2132129 1023456.6276679  677132.5882294
 1023401.3325221  677132.5882294  1023359.678942   677123.738357
 1023317.1910553   677093.015149 1023280.2673915  677052.8473633
#Sta/Elev= 30
       0 2583.03    8.22 2583.76    9.85 2583.63   18.52 2581.47   22.19 2580.35
   25.08 2580.07   26.21 2579.76   42.71  2573.9   59.29 2572.17   62.58 2571.85
   65.04 2571.72   69.33 2571.82   73.76 2572.67   82.83 2574.64   90.07 2575.37
   97.12 2575.53  102.12 2575.82   136.4 2576.71  154.83 2577.03  182.04 2576.69
  200.43 2576.72  223.82  2577.3  243.92 2578.86  260.09 2580.43  267.99 2581.39
  274.67 2583.62  283.12 2585.47   284.9 2586.56  288.31  2588.2  307.28 2599.95
#Mann= 3 ,-1 , 0
       0     .08       0   42.71     .05       0   82.83      .1       0
Bank Sta=42.71,82.83
Exp/Cntr=0.3,0.1

Type RM Length L Ch R = 1 ,414398.1,53.14,171.51,198.63
XS GIS Cut Line= 6
 1023580.7596106  677182.2410004 1023605.5860112  677079.5500154
 1023605.5860112  677009.5847375 1023599.9436364  676954.2895917
 1023580.7596106  676913.6646082 1023586.4019854  676892.2236204
#Sta/Elev= 30
       0 2580.22    4.56 2580.19   22.75 2581.32   27.01 2580.71    40.4 2578.14
    51.5  2576.4    63.8 2574.85   72.83 2573.87   85.17 2573.33    97.6 2572.97
  151.57 2572.66  172.67 2572.21  181.12 2571.91  197.23 2571.33  206.26 2570.45
  209.94 2569.77  214.18 2569.76  220.61 2569.96  225.17  2571.6  231.26 2573.79
  244.13 2577.98  248.93 2581.83  252.62 2582.71  255.68 2582.41  261.46 2590.17
   268.3 2594.08  276.66 2597.42  280.33 2599.09  298.06 2613.58  298.83 2614.09
#Mann= 4 ,-1 , 0
       0     .05       0  181.12     .08       0  197.23     .05       0
  225.17      .1       0
Bank Sta=197.23,225.17
Exp/Cntr=0.3,0.1

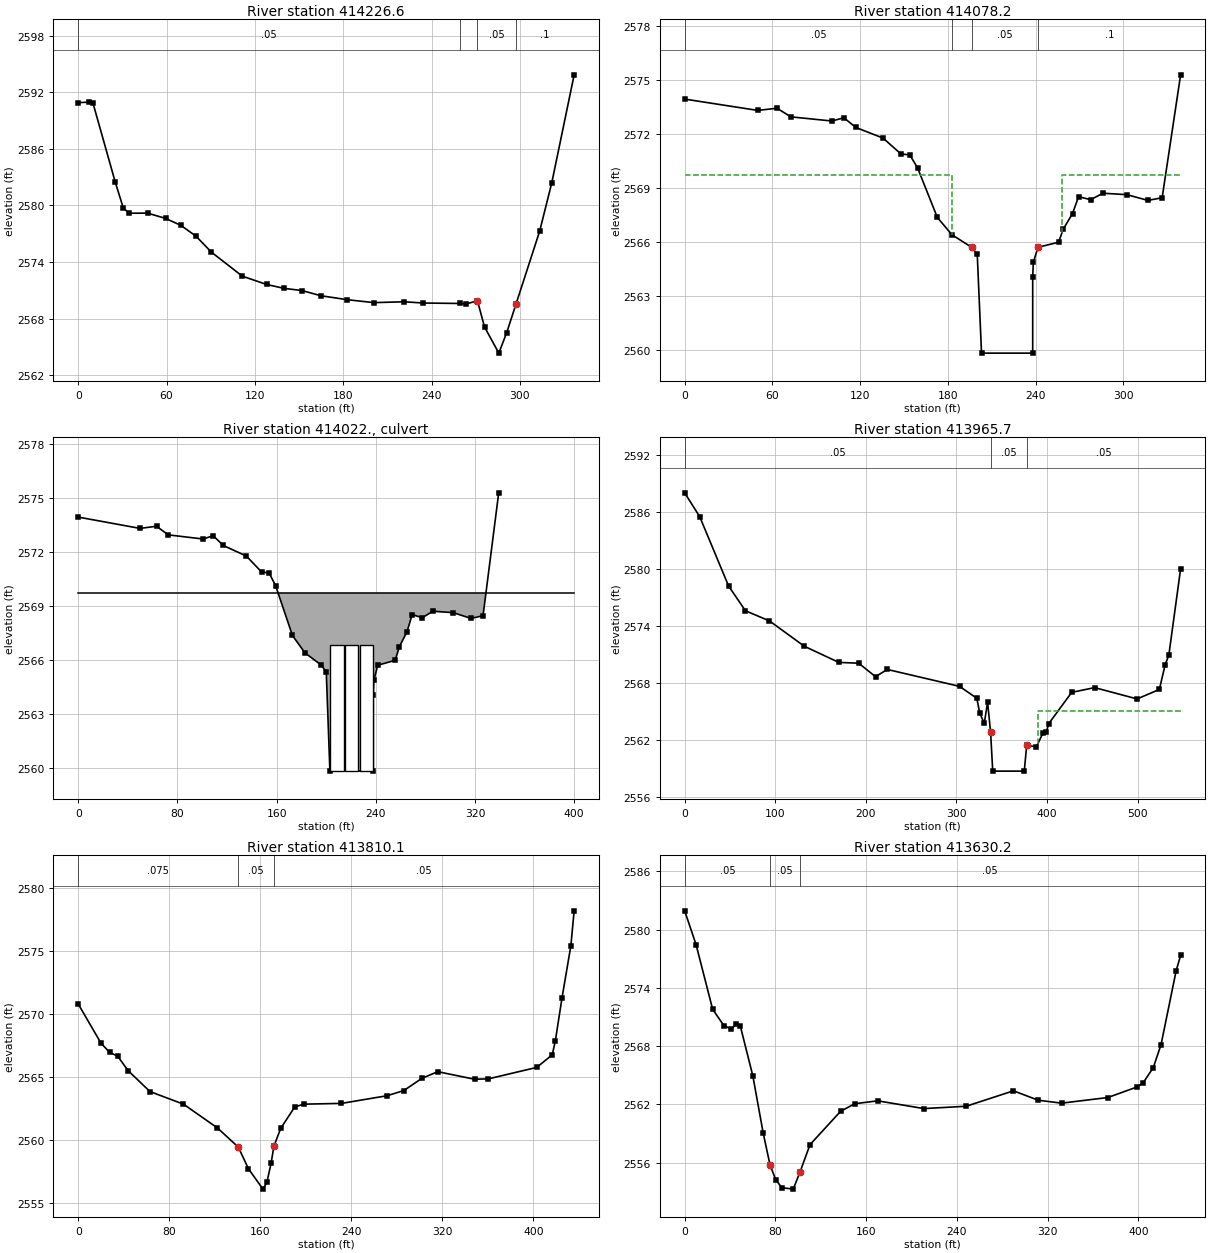
Type RM Length L Ch R = 1 ,414226.6,86.56,148.46,199.41
XS GIS Cut Line= 6
 1023643.9540629  677218.3520901 1023630.4123816  677179.9840384
 1023630.4123816  677167.5708684 1023654.1103012   677103.247935
 1023729.3429639  677058.3535928 1023797.8651857  676951.2642165
#Sta/Elev= 30
       0 2590.92    7.36 2590.97    10.1 2590.83   25.16 2582.48   30.58 2579.76
   34.47 2579.18   47.14 2579.19   59.31 2578.63   69.64  2577.9   79.99 2576.75
   90.45 2575.05  111.47  2572.5  127.94 2571.62  139.61 2571.21  152.09 2570.97
  164.88 2570.42  182.86    2570  200.78 2569.69  221.44 2569.78  234.31 2569.65
  259.24  2569.6  263.49 2569.55   271.2 2569.89     276 2567.11  285.72 2564.33
  291.06  2566.5  297.34 2569.51  313.47 2577.28  321.73 2582.44  336.89 2593.87
#Mann= 4 ,-1 , 0
       0     .05       0  259.24     .08       0   271.2     .05       0
  297.34      .1       0
Bank Sta=271.2,297.34
Exp/Cntr=0.5,0.3

Type RM Length L Ch R = 1 ,414078.2,269.59,112.44,83.71
XS GIS Cut Line= 6
 1023696.3923959  677120.1359229 1023777.6455107  677089.4319955
 1023810.5960787  677078.1988226  1023976.076924  677005.6941825
  1023966.736892  676980.4704238 1023960.3714455  676972.9816418
#Sta/Elev= 30
       0 2573.94  49.869 2573.31   63.15 2573.43   72.63 2572.95  100.63 2572.72
   108.9  2572.9 117.021 2572.36  135.63 2571.77 147.831 2570.89  153.95 2570.83
 159.221 2570.12  172.79 2567.35  182.77 2566.39  196.22 2565.69  200.07 2565.31
     203  2559.8 237.999  2559.8 237.999 2564.01 238.429 2564.85  241.58 2565.69
  255.68 2565.97  258.89  2566.7  265.23 2567.57 269.379 2568.51  277.62 2568.34
 286.011  2568.7  302.43 2568.62 316.809  2568.3 326.519 2568.45  339.15 2575.29
#Mann= 4 ,-1 , 0
       0     .05       0  182.77     .08       0  196.22     .05       0
  241.58      .1       0
#XS Ineff= 2 , 0
       0     183 2569.73     258       0 2569.73
Permanent Ineff=
       F       F
Bank Sta=196.22,241.58
Exp/Cntr=0.5,0.3

Type RM Length L Ch R = 2 ,414022. ,,,
BEGIN DESCRIPTION:
NC9
END DESCRIPTION:
Bridge Culvert--1,0,-1,-1, 0
Deck Dist Width WeirC Skew NumUp NumDn MinLoCord MaxHiCord MaxSubmerge Is_Ogee
35,36,2.6,0, 2, 2, , , 0.95, 0, 1,1,,
       0     400
 2569.73 2569.73
                
       0     600
 2569.73 2569.73
                
BR Coef= 1 , 0 , 0 ,, 0 ,,,0.8,-1,,1,
WSPro=,,,, 1 ,,,, 0 ,,,, 0 ,,,,-1 ,-1 ,-1 , 0 , 0 , 0 , 0 , 0
Culvert=2,7,11,106.5,0.011,0.5,1,11,1,2559.8,208.5,2558.73,345.49,Culvert #1  , 0 ,2.75
Culvert Bottom n=0.011
Culvert=2,7,11,106.5,0.013,0.5,1,11,1,2559.8,220.5,2558.73,357.49,Culvert #2  , 0 ,2.75
Culvert Bottom n=0.05
Culvert Bottom Depth=2
Culvert=2,7,11,106.5,0.013,0.5,1,11,1,2559.8,232.5,2558.73,369.49,Culvert #3  , 0 ,2.75
Culvert Bottom n=0.05
Culvert Bottom Depth=2
BC Design=,, 0 ,, 0 ,,,,,,

Type RM Length L Ch R = 1 ,413965.7,152.84,155.58,95.07
XS GIS Cut Line= 6
 1023709.1232889  677211.1244603 1023742.0738569  677158.3286322
 1024070.0818773  677028.7729706 1024062.5931256  676999.5667936
 1024021.4048853  676934.0400725  1024003.431851  676917.1903434
#Sta/Elev= 30
       0 2587.99   16.61 2585.48   48.51 2578.19    67.1 2575.59  93.651 2574.52
  132.08 2571.86  170.21 2570.16   192.1 2570.08 210.709 2568.66  223.73 2569.42
  303.53 2567.64  322.55 2566.39 325.831 2564.82  330.81 2563.76  334.46 2565.98
 337.759 2562.82 340.149 2558.73  374.99 2558.73  377.66 2561.49  388.19 2561.26
  395.42  2562.7 399.259 2562.82  401.87 2563.71  427.35 2567.01  452.69 2567.51
  499.53 2566.32  524.15 2567.32 530.539 2569.94  534.56 2570.91 547.591 2580.01
#Mann= 3 , 0 , 0
       0     .05       0 337.759     .05       0  377.66     .05       0
#XS Ineff= 2 , 0
       0     325    2565     390       0    2565
Permanent Ineff=
       F       F
Bank Sta=337.759,377.66
Exp/Cntr=0.5,0.3

Type RM Length L Ch R = 1 ,413810.1,293.46,179.9,87.22
XS GIS Cut Line= 6
 1024040.7522977   677203.437302 1024053.3900259  677188.5693989
 1024146.3144123  677125.3808186 1024190.9181517   677072.599731
 1024192.4049148  677051.0412731 1024094.8584265  676863.2119757
#Sta/Elev= 30
       0 2570.79   19.98 2567.68   27.55 2566.95   34.66 2566.64    43.9 2565.49
   63.04 2563.83   92.51 2562.83  122.34 2560.94  140.66 2559.42  149.57  2557.7
  162.33 2556.08  165.76 2556.61  169.45 2558.12     1722559.504  177.97 2560.91
  190.29 2562.61  198.08 2562.83  231.27 2562.89  271.36  2563.5  286.12 2563.91
  301.96 2564.88  315.91 2565.41  348.34 2564.81  360.41 2564.84   402.9 2565.75
  416.55 2566.75  419.28 2567.87  425.12 2571.27  432.89 2575.41  435.79 2578.19
#Mann= 3 , 0 , 0
       0    .075       0  140.66     .05       0     172     .05       0
Bank Sta=140.66,172
Exp/Cntr=0.3,0.1

Type RM Length L Ch R = 1 ,413630.2,151.96,149.37,150.05
XS GIS Cut Line= 6
 1024342.4783606  677185.6264132 1024332.3221223  677108.8903098
 1024309.7526837  677087.4493219 1024259.4065339  677007.6486463
 1024184.4457382  676829.3882068 1024152.4502762  676808.3626166
#Sta/Elev= 30
       0 2581.94   10.03 2578.46   24.67 2571.79   34.49 2570.12    41.1 2569.75
   45.28 2570.25   49.11 2570.04   60.07 2564.94   69.26 2559.01   75.28 2555.73
   80.36 2554.21   85.62 2553.41   95.68 2553.26  101.61    2555  110.46 2557.84
  137.45 2561.28  149.91 2562.06  170.19 2562.36  210.88 2561.56  248.15  2561.8
  289.83 2563.39  311.73 2562.42  332.29 2562.12  373.08  2562.7  398.33 2563.77
  403.98 2564.18  413.13 2565.79  419.97 2568.16   433.3 2575.78  437.21 2577.34
#Mann= 3 , 0 , 0
       0     .05       0   75.28     .05       0  101.61     .05       0
Bank Sta=75.28,101.61
Exp/Cntr=0.3,0.1

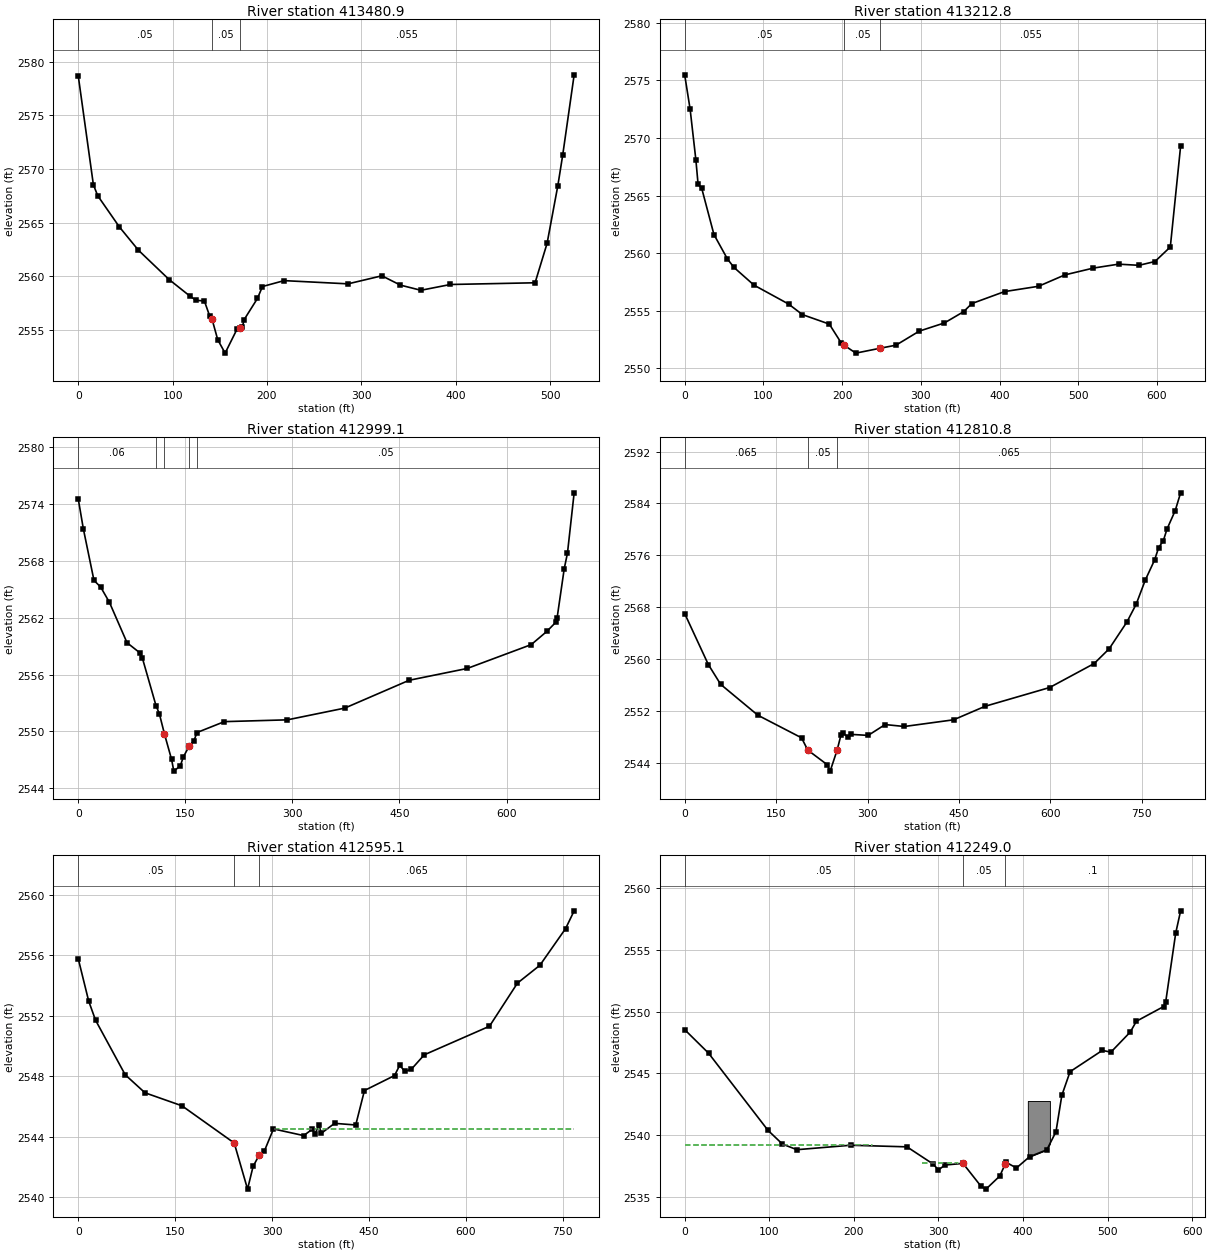
Type RM Length L Ch R = 1 ,413480.9,205.57,268.06,182.09
XS GIS Cut Line= 6
 1024463.2633611   677164.883526 1024474.5096098  677082.9354281
 1024469.9957161  677045.6958575 1024418.0860133  676979.1159923
 1024381.9034609  676912.5764139 1024285.9170751    676688.60815
#Sta/Elev= 30
       0 2578.72   16.06 2568.55   20.64 2567.52   43.68  2564.6   63.77 2562.44
   96.34  2559.7  118.48 2558.15  124.92 2557.76  133.66 2557.71  139.31  2556.3
  141.76 2556.02  147.84 2554.09  155.66 2552.84  168.14 2555.05  171.16 2555.16
  173.92 2555.26   175.8 2555.96  189.93 2557.94  195.22 2559.05   218.2  2559.6
  285.91  2559.3  321.76 2560.05  341.48 2559.18  363.11  2558.7  394.41 2559.24
  484.12  2559.4  496.82 2563.07  508.22 2568.45  513.38  2571.3  525.52 2578.79
#Mann= 3 , 0 , 0
       0     .05       0  141.76     .05       0  171.16    .055       0
Bank Sta=141.76,171.16
Exp/Cntr=0.3,0.1

Type RM Length L Ch R = 1 ,413212.8,237.3,213.69,106.26
XS GIS Cut Line= 6
 1024712.7137512  677101.4639404 1024675.0047847  677037.0159095
 1024675.3233552  676877.3418546 1024657.8964157  676850.6889026
 1024367.8483136  676706.5484646 1024350.0222909  676675.6956794
#Sta/Elev= 30
       0 2575.48    6.95 2572.48   14.28 2568.06   17.04 2565.97   21.57 2565.65
   37.18 2561.62   54.31  2559.5   62.55 2558.77   88.04 2557.23  131.96 2555.59
  149.62 2554.67  183.69 2553.85   198.8 2552.22  202.63 2552.01  217.36 2551.33
  248.67 2551.76  268.41 2552.02     298 2553.24  329.93 2553.95  354.39 2554.93
  364.72 2555.63  406.26 2556.67  449.43 2557.13  482.97 2558.12  519.15 2558.71
  551.06 2559.05  577.05 2558.95  597.34 2559.28  616.85 2560.54  629.95 2569.29
#Mann= 3 , 0 , 0
       0     .05       0  202.63     .05       0  248.67    .055       0
Bank Sta=202.63,248.67
Exp/Cntr=0.3,0.1

Type RM Length L Ch R = 1 ,412999.1,112.53,188.35,204.88
XS GIS Cut Line= 6
 1024919.0844853  677039.0727699 1024886.4969515  676888.6181291
 1024877.2709389  676879.3920863 1024620.9922747  676725.6249181
 1024458.3497787  676656.4984264 1024426.1257633  676618.7894599
#Sta/Elev= 30
       0 2574.58    7.15 2571.41   22.06 2565.95   31.47 2565.24   43.71 2563.63
   68.39 2559.36   86.68 2558.27    89.9 2557.73  108.94 2552.72  113.67 2551.85
  120.79 2549.72   130.8 2547.02  133.93 2545.79  143.05 2546.35  147.14 2547.27
  155.82 2548.49  161.92 2548.97   166.4 2549.87  204.73 2551.02  293.01 2551.21
  373.34 2552.45   463.5 2555.39  544.91 2556.64  634.56 2559.16  656.33 2560.55
  669.23 2561.54  670.68 2561.92   680.8 2567.19   685.3 2568.82  694.68  2575.2
#Mann= 5 ,-1 , 0
       0     .06       0  108.94     .08       0  120.79     .05       0
  155.82     .08       0   166.4     .05       0
Bank Sta=120.79,155.82
Exp/Cntr=0.3,0.1

Type RM Length L Ch R = 1 ,412810.8,237.15,215.69,106.25
XS GIS Cut Line= 6
 1024996.1842282  676999.3305218 1025024.8874422   676832.236817
 1025016.6865153  676775.8555351 1024812.8138276  676641.4148338
 1024720.2555324  676546.7996781 1024603.7006028  676374.7097896
#Sta/Elev= 30
       0 2567.06    38.8 2559.21   59.02 2556.16  120.01 2551.41  191.71 2547.93
  201.94 2546.04  233.47 2543.82  238.71  2542.8  250.15 2546.04  256.43 2548.36
  260.41 2548.64  267.42 2548.04  272.37 2548.46  301.08  2548.3  328.91 2549.97
  360.38 2549.67  441.24  2550.7  492.88 2552.78  598.87 2555.67  671.88 2559.36
  696.49 2561.63  725.72 2565.77  740.79 2568.49  755.96 2572.25  770.94 2575.28
  777.65 2577.19  785.45  2578.3  791.49 2580.08   804.9 2582.91  813.74 2585.64
#Mann= 3 , 0 , 0
       0    .065       0  201.94     .05       0  250.15    .065       0
Bank Sta=201.94,250.15
Exp/Cntr=0.3,0.1

Type RM Length L Ch R = 1 ,412595.1,309.52,346.1,594.16
XS GIS Cut Line= 6
 1025171.4504988  676936.0962973 1025230.4852533  676766.0464705
 1025218.1615554  676701.6893646 1025016.1153888   676594.626836
 1024908.6997238   676588.037467 1024814.2180196  676448.3688504
#Sta/Elev= 30
       0 2555.78   16.23 2552.97   26.82 2551.71   72.77  2548.1  103.35 2546.91
  160.58 2546.05  241.51 2543.59  262.16 2540.54  270.73 2542.04  280.42 2542.81
  287.92 2543.03  302.27 2544.52  349.02 2544.08  362.03 2544.49  366.62 2544.19
   372.8 2544.78  376.32 2544.23  396.87 2544.89  429.62 2544.78  443.14 2547.06
  489.75 2548.05  497.73 2548.73  505.76 2548.32  515.83 2548.47  535.72 2549.42
   636.7 2551.31  679.99 2554.16  714.74 2555.34  754.59 2557.77  767.78 2558.94
#Mann= 3 , 0 , 0
       0     .05       0  241.51     .05       0  280.42    .065       0
#XS Ineff= 2 , 0
                          302.47         2544.52
Permanent Ineff=
       F       F
Bank Sta=241.51,280.42
Exp/Cntr=0.3,0.1

Type RM Length L Ch R = 1 ,412249.0,575.8,578.09,497.15
XS GIS Cut Line= 6
 1025508.4531633  676897.4992986 1025511.1917494  676819.4491715
 1025534.4698522  676724.9674673 1025534.4698522  676607.2076604
 1025463.2662508  676519.5724517 1025415.3407522  676348.4099438
#Sta/Elev= 30
       0 2548.54   28.18 2546.64   98.55 2540.39  115.62 2539.28  132.72 2538.83
  196.21 2539.19  262.82 2539.06  293.69 2537.67  300.03 2537.19  307.71 2537.59
  329.05 2537.72  350.49 2535.86  356.23 2535.64  372.56  2536.7  378.75 2537.64
  380.23  2537.8  392.24 2537.35   407.7 2538.26  428.17 2538.82  438.95 2540.28
  445.91 2543.23  455.64 2545.14  493.76 2546.86  503.92 2546.72  526.86 2548.35
  534.06 2549.22  566.31 2550.41  568.62 2550.75  580.53 2556.35  586.33 2558.15
#Mann= 3 , 0 , 0
       0     .05       0  329.05     .05       0  378.75      .1       0
#XS Ineff= 3 ,-1
       0  221.43 2539.23     280   323.7 2537.77  380.23     420  2537.8
Permanent Ineff=
       F       F       F
#Block Obstruct= 1 ,-1
   405.7   431.8 2542.77
Bank Sta=329.05,378.75
Exp/Cntr=0.3,0.1

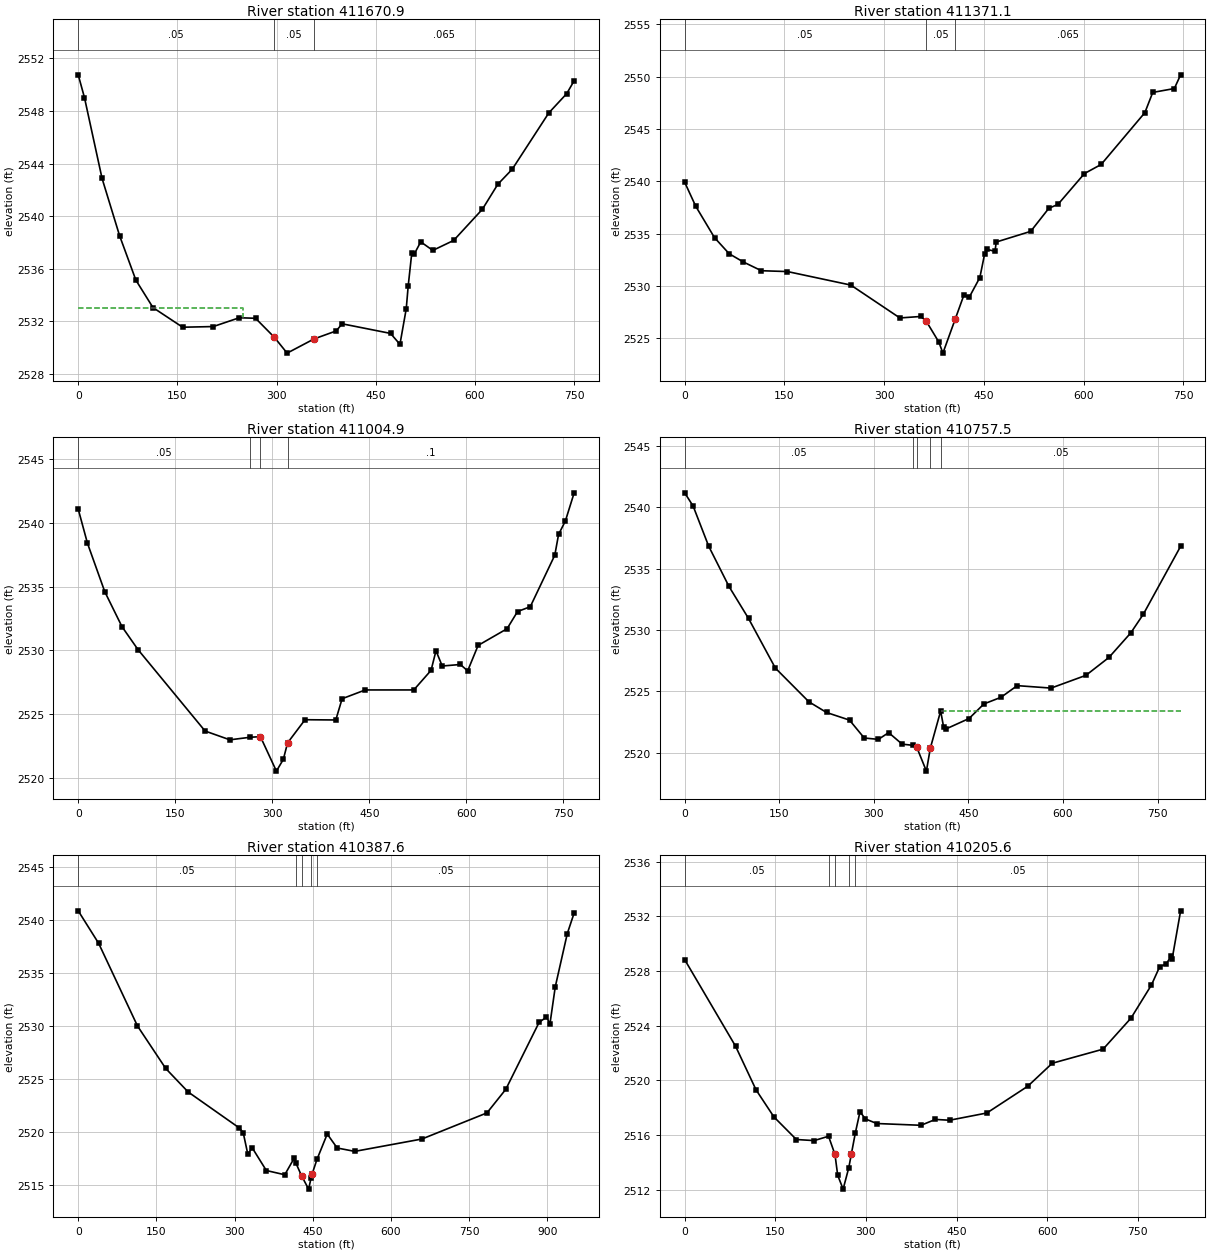
Type RM Length L Ch R = 1 ,411670.9,130.31,299.83,147.38
XS GIS Cut Line= 6
 1026162.3815005  676917.3489476 1026003.0291034  676672.2943759
 1025975.3844816  676459.3232552 1025931.5668924  676379.9038653
 1025908.2887897  676293.6379497 1025883.6413938  676238.8659556
#Sta/Elev= 30
       0 2550.75    9.44 2549.02   36.03 2542.88   62.55 2538.52   87.19 2535.14
   113.1 2533.05  157.89 2531.56  204.26 2531.61  243.56 2532.28  268.14 2532.24
  296.67 2530.79  315.89 2529.59  356.64 2530.67  390.18 2531.28  399.04 2531.82
  472.23 2531.09   486.5 2530.26  496.02 2532.96  498.97 2534.69  504.35 2537.19
  507.87  2537.1  517.95 2538.05  536.22  2537.4  567.75 2538.16  611.18 2540.53
  634.51 2542.43  656.25 2543.57  711.68 2547.86  738.68 2549.32  749.93  2550.3
#Mann= 3 , 0 , 0
       0     .05       0  296.67     .05       0  356.64    .065       0
#XS Ineff= 2 , 0
       0  248.75    2533  399.04       0 2531.82
Permanent Ineff=
       T       F
Bank Sta=296.67,356.64
Exp/Cntr=0.3,0.1

Type RM Length L Ch R = 1 ,411371.1,403.76,366.17,353.67
XS GIS Cut Line= 6
 1026221.3017512  676861.1069286 1026197.1979985  676543.7411898
 1026172.5637087  676455.2153458 1026095.8829049  676374.4266629
 1026027.4178896  676233.3887532 1025987.7081796  676189.5711337
#Sta/Elev= 30
       0  2539.9   16.69  2537.6   44.86 2534.61   66.95 2533.07   88.39 2532.28
  115.38 2531.45  154.62 2531.37  249.85 2530.08  323.62 2526.94  354.82 2527.08
   362.8 2526.68   382.2 2524.64  388.33 2523.58  407.08 2526.87   420.1 2529.16
  427.85 2528.91  443.89  2530.8  450.94 2533.01  455.22 2533.48  466.69  2533.3
   468.5 2534.19  520.37 2535.21  547.72 2537.42  561.28 2537.78  601.17 2540.73
  626.32  2541.6  692.06 2546.55  703.89 2548.48  736.35 2548.85  745.81 2550.16
#Mann= 3 , 0 , 0
       0     .05       0   362.8     .05       0  407.08    .065       0
Bank Sta=362.8,407.08
Exp/Cntr=0.3,0.1

Type RM Length L Ch R = 1 ,411004.9,251.79,247.42,162.36
XS GIS Cut Line= 6
 1026621.6914329  676749.9619461 1026593.5704234  676658.9034291
 1026593.5704234  676561.1494236  1026517.627341  676437.4144455
 1026499.8264407  676300.4844452 1026301.2779205  676092.3508435
#Sta/Elev= 30
       0  2541.1   14.28 2538.42   41.06 2534.61   67.71 2531.86   92.43 2530.06
  196.19 2523.66  234.53 2522.97  265.55 2523.17  281.73 2523.22  306.43 2520.51
   317.1 2521.43  323.71 2522.73  350.69 2524.55  398.26 2524.53  408.03  2526.2
  443.85 2526.89  518.82 2526.89  545.55 2528.43  553.17 2529.97  562.81 2528.77
  590.83 2528.89  602.15 2528.39   618.3 2530.39  663.08  2531.7  679.24 2533.05
  698.95 2533.43  736.86 2537.48   742.7 2539.11  753.25 2540.17  766.79 2542.38
#Mann= 4 ,-1 , 0
       0     .05       0  265.55     .08       0  281.73     .05       0
  323.71      .1       0
Bank Sta=281.73,323.71
Exp/Cntr=0.3,0.1

Type RM Length L Ch R = 1 ,410757.5,226.52,369.88,341.77
XS GIS Cut Line= 6
 1026865.4295594  676672.9340594 1026814.7654444  676583.9295576
 1026798.3338371  676420.9828382 1026746.3004594  676337.4555389
 1026618.9555406  676238.8659556 1026471.0711355  676030.7323237
#Sta/Elev= 30
       0 2541.19   13.41 2540.11   38.06 2536.84   70.21 2533.56  101.22 2530.95
  143.82  2526.9  197.05 2524.15  225.06 2523.28  261.38 2522.66  284.77  2521.2
  307.22 2521.09  323.47 2521.64  344.85  2520.7  362.57  2520.6  367.69 2520.49
  383.33  2518.5  389.54 2520.37  405.94  2523.4   410.5 2522.13  414.48 2521.94
  450.99 2522.79  474.59 2523.98  501.65 2524.52  527.33 2525.47  581.03 2525.27
  636.34 2526.31  672.84 2527.77  707.42 2529.77  727.32 2531.29  786.48 2536.83
#Mann= 5 ,-1 , 0
       0     .05       0  362.57     .08       0  367.69     .05       0
  389.54     .08       0  405.94     .05       0
#XS Ineff= 2 , 0
       0                  405.76       0 2523.37
Permanent Ineff=
       F       F
Bank Sta=367.69,389.54
Exp/Cntr=0.3,0.1

Type RM Length L Ch R = 1 ,410387.6,194.01,181.98,137.8
XS GIS Cut Line= 6
 1027079.0403635  676625.0085608 1027021.5297531    676430.56795
   1027020.16046  676307.3309407 1027069.4552819  676177.2474358
 1026858.5830639  676003.3463115 1026777.7943507  675818.4908126
#Sta/Elev= 30
       0  2540.9   39.16 2537.83  113.69 2530.01  167.87 2525.99  210.83 2523.77
  308.63 2520.38  316.45 2519.93  325.44 2517.86  333.49 2518.51  360.86 2516.34
   396.2 2515.94  414.29 2517.51  417.71 2517.03  428.32 2515.85  441.99 2514.58
  446.82 2515.67  448.76 2516.02  457.97 2517.39  477.69 2519.79  496.77 2518.47
  530.47 2518.15   659.3 2519.32  784.07 2521.79  820.19 2524.02   884.3 2530.37
  898.22 2530.84  904.97 2530.23  915.08 2533.71  938.17 2538.75  951.32  2540.7
#Mann= 5 ,-1 , 0
       0     .05       0  417.71     .08       0  428.32     .05       0
  446.82     .08       0  457.97     .05       0
Bank Sta=428.32,448.76
Exp/Cntr=0.3,0.1

Type RM Length L Ch R = 1 ,410205.6,85.07,56.31,46.84
XS GIS Cut Line= 6
 1027229.9736318  676465.0284361 1027211.7860883  676357.6352299
 1027247.2951176  676178.3578468 1027016.0533073  675939.3213664
 1026935.5084027  675887.3569088 1026876.6153327  675814.6066743
#Sta/Elev= 30
       0 2528.84   84.27  2522.5  118.16 2519.31  147.74 2517.33  184.87 2515.68
  214.33  2515.6  238.09 2515.92  248.72 2514.59  253.26 2513.06  262.25 2512.05
  271.62 2513.62  275.87 2514.62  282.57 2516.19  290.18 2517.72  298.87 2517.19
  317.81 2516.85  391.16 2516.72  414.88 2517.15  438.37 2517.09   500.1 2517.62
  567.89 2519.58  608.37 2521.26  692.48 2522.29  738.67 2524.56  772.46 2526.98
  786.23 2528.33  797.07 2528.52  804.51 2529.07   806.8  2528.9   820.8 2532.41
#Mann= 5 ,-1 , 0
       0     .05       0  238.09     .08       0  248.72     .05       0
  271.62     .08       0  282.57     .05       0
Bank Sta=248.72,275.87
Exp/Cntr=0.5,0.3