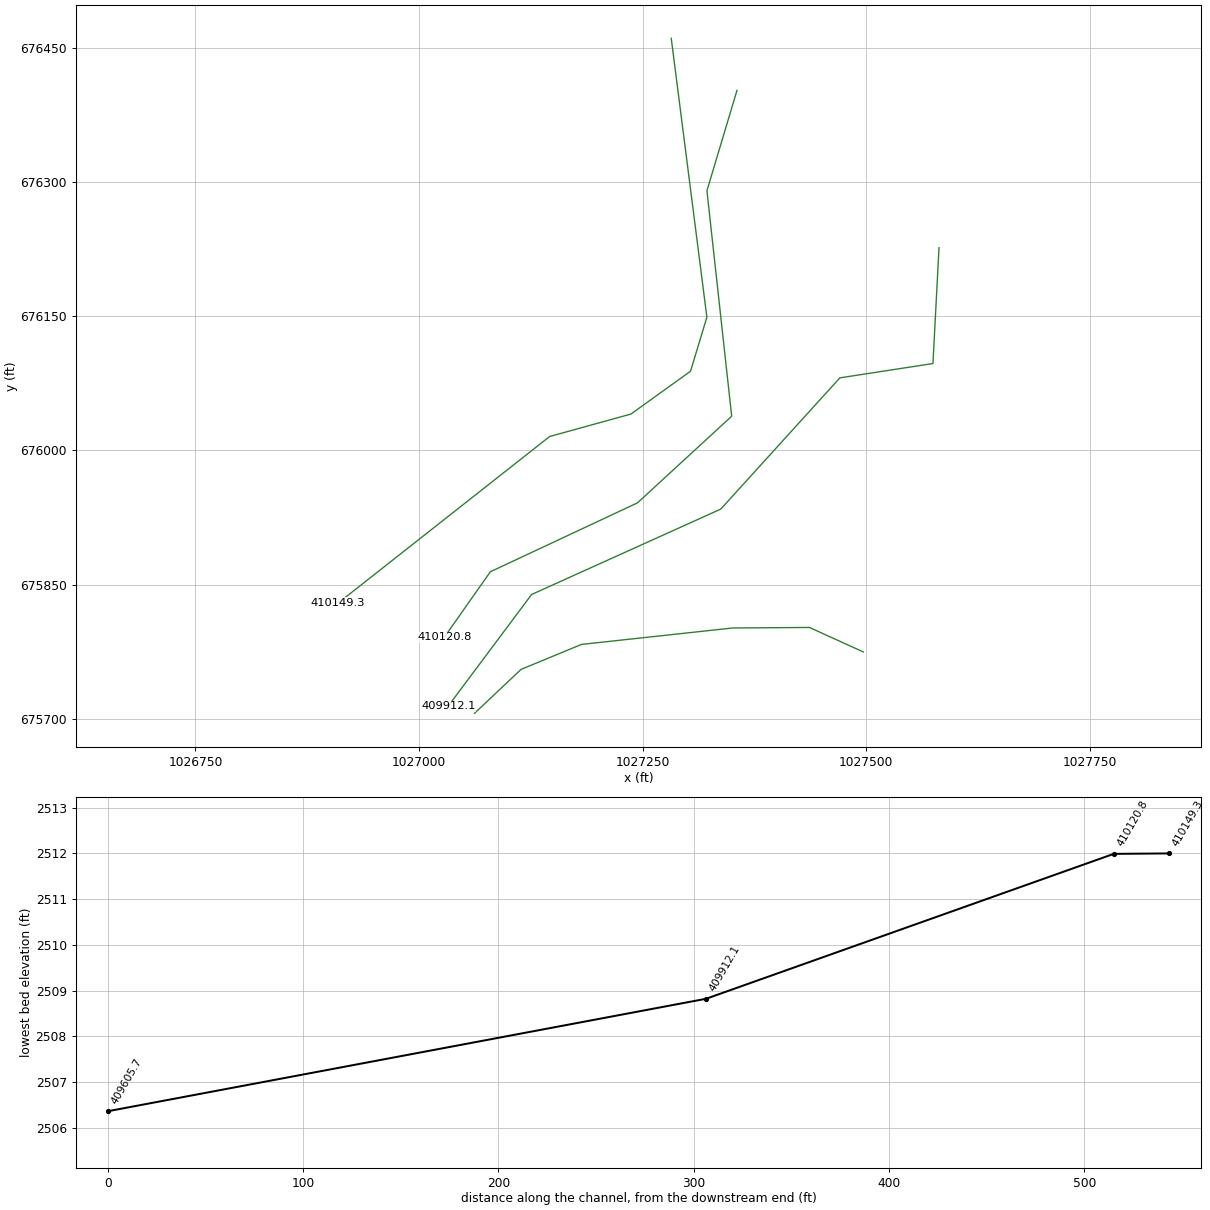
HEC-RAS study lds_broad_rvr.prj: Upper_Broad 3-06-07

--- lds_broad_rvr.g05 (geometry) --- (continued)

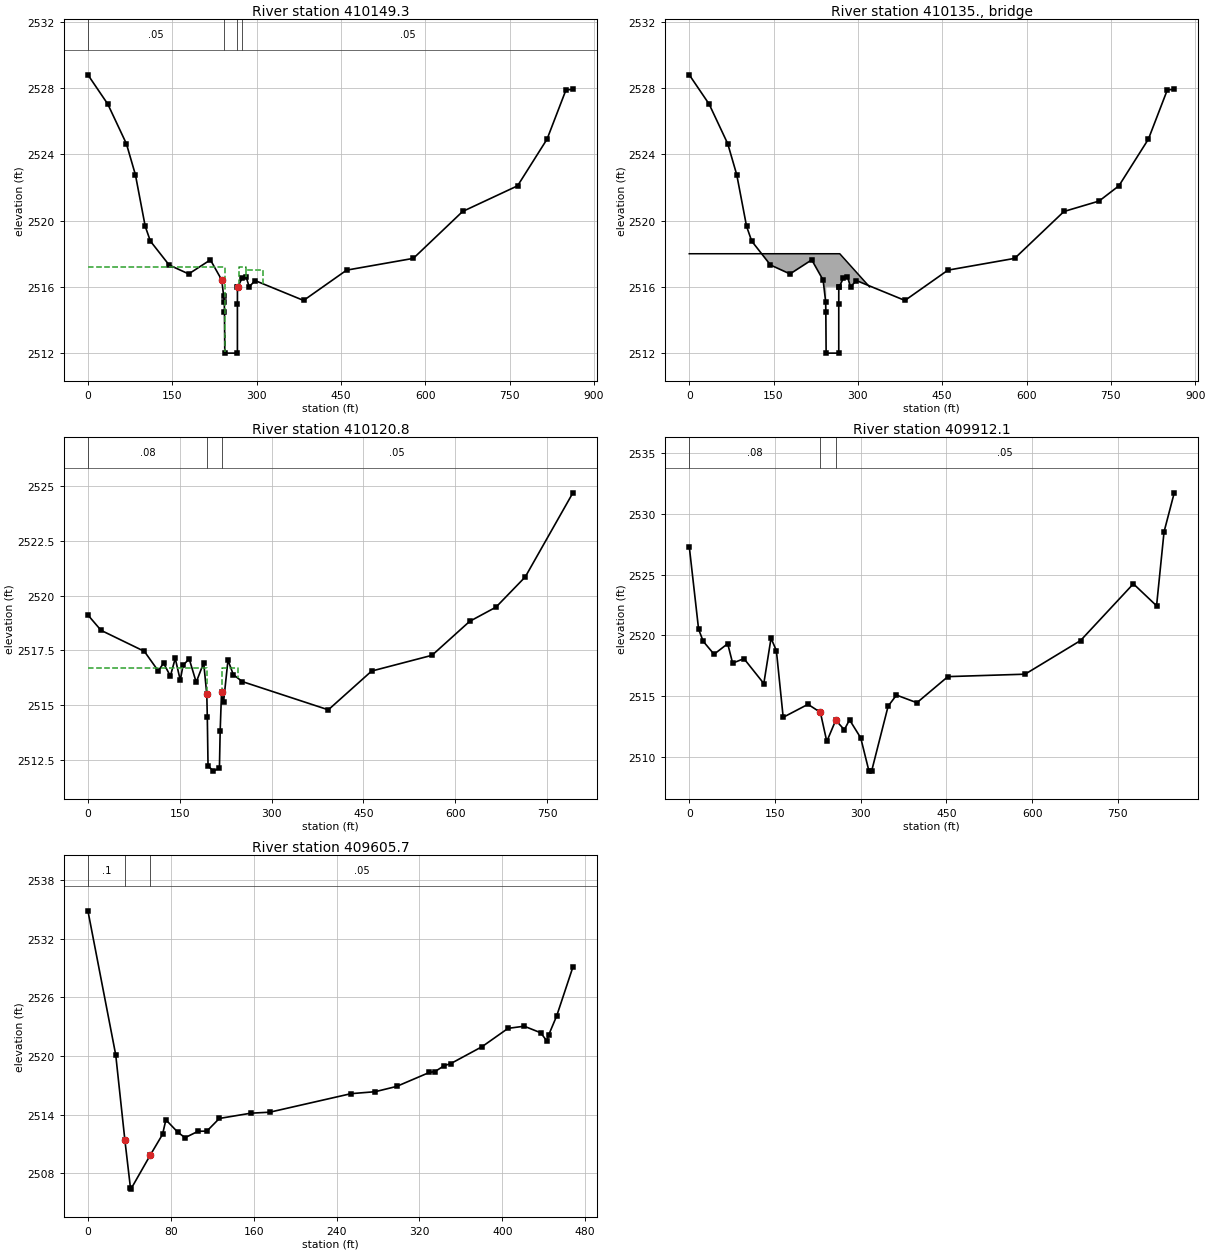
Type RM Length L Ch R = 1 ,410149.3,48.43,28.48,82.73
XS GIS Cut Line= 6
 1027281.9380893   676460.698057 1027321.7774977  676148.9113421
 1027303.4821699  676088.5182213 1027236.9022443   676040.652048
  1027145.964436   676015.535892 1026909.5261588  675829.3299267
#Sta/Elev= 30
       0  2528.8   35.39 2527.03   68.46 2524.64   84.47 2522.77  101.98 2519.65
  111.16 2518.76  144.46 2517.32  179.26 2516.78   217.9 2517.63  238.12 2516.41
  241.41 2515.46  242.62 2515.11  242.94 2514.51  243.49    2512  265.96    2512
  265.96 2514.96     266 2515.97  266.61 2515.99  274.36 2516.53   281.5  2516.6
  286.86    2516   297.4 2516.38  383.69 2515.18  460.25 2517.01  578.94 2517.72
  666.55 2520.55  764.36  2522.1  816.83 2524.92  850.48 2527.89  862.79 2527.92
#Mann= 4 ,-1 , 0
       0     .05       0  241.41     .05       0  265.96     .08       0
  274.36     .05       0
#XS Ineff= 3 ,-1
       0  243.47  2517.2  268.75   281.5  2517.2   281.5   311.5    2517
Permanent Ineff=
       F       F       F
Bank Sta=238.12,266.61
Exp/Cntr=0.5,0.3

Type RM Length L Ch R = 3 ,410135. ,,,
BEGIN DESCRIPTION:
STR_163
END DESCRIPTION:
Bridge Culvert--1,0,-1,-1, 0
Deck Dist Width WeirC Skew NumUp NumDn MinLoCord MaxHiCord MaxSubmerge Is_Ogee
3,24,2.6,0, 4, 4, , , 0.95, 0, ,,,
       0  243.74  267.74  320.75
    2518    2518    2518    2516
            2516    2516
       0     194     218  260.25
    2518    2518    2518    2516
            2516    2516
BR Coef= 1 , 1 , 0 ,, 0 ,,,0.8,0,2,0,
WSPro=,,,, 1 ,,,, 0 ,,,, 0 ,,,,-1 ,-1 ,-1 , 0 , 0 , 0 , 0 , 0
BR U #Sta/Elev= 30
       0  2528.8   35.39 2527.03   68.46 2524.64   84.47 2522.77  101.98 2519.65
  111.16 2518.76  144.46 2517.32  179.26 2516.78   217.9 2517.63  238.12 2516.41
  242.62 2515.11  242.94 2514.51  243.49    2512  265.96    2512  265.96 2514.96
     266 2515.97  266.61 2515.99  274.36 2516.53   281.5  2516.6  286.86    2516
   297.4 2516.38  383.69 2515.18  460.25 2517.01  578.94 2517.72  666.55 2520.55
  729.06 2521.18  764.36  2522.1  816.83 2524.92  850.48 2527.89  862.79 2527.92
BR U #Mann= 4
       0     .05  238.12     .04  266.61     .05  274.36     .05
BR D #Sta/Elev= 30
       0 2519.12   21.42 2518.42   92.17 2517.46   114.8 2516.57  123.59 2516.92
  134.63 2516.33   142.6 2517.14  150.83 2516.14  155.33 2516.82  165.37 2517.12
  176.83 2516.05  189.04 2516.94  194.13 2515.49  194.97 2514.45  196.16 2512.23
  204.96 2511.99  214.77 2512.13  215.95 2513.81   218.2  2515.6  221.47 2515.14
  228.71 2517.06  237.38  2516.4  252.05 2516.08  392.57 2514.79  463.28 2516.56
   561.9 2517.28  623.38 2518.83  666.42 2519.48  714.18 2520.86  791.98  2524.7
BR D #Mann= 3
       0     .05  194.13     .04   218.2     .05
BC Design=,, 0 ,, 0 ,,,,,,

Type RM Length L Ch R = 1 ,410120.8,320.23,208.77,45.87
XS GIS Cut Line= 6
 1027355.4367299  676402.4953088 1027321.8292862   676290.305748
 1027349.5060223  676038.2498905 1027244.2356305  675941.3813747
 1027079.6579816  675864.2819345 1027028.2583548  675791.1363094
#Sta/Elev= 30
       0 2519.12   21.42 2518.42   92.17 2517.46   114.8 2516.57  123.59 2516.92
  134.63 2516.33   142.6 2517.14  150.83 2516.14  155.33 2516.82  165.37 2517.12
  176.83 2516.05  189.04 2516.94  194.13 2515.49  194.97 2514.45  196.16 2512.23
  204.96 2511.99  214.77 2512.13  215.95 2513.81   218.2  2515.6  221.47 2515.14
  228.71 2517.06  237.38  2516.4  252.05 2516.08  392.57 2514.79  463.28 2516.56
   561.9 2517.28  623.38 2518.83  666.42 2519.48  714.18 2520.86  791.98  2524.7
#Mann= 3 , 0 , 0
       0     .08       0  194.13     .05       0   218.2     .05       0
#XS Ineff= 2 ,-1
       0     194  2516.7  218.17     245  2516.7
Permanent Ineff=
       T       T
Bank Sta=194.13,218.2
Exp/Cntr=0.5,0.3

Type RM Length L Ch R = 1 ,409912.1,409.91,306.34,72.3
XS GIS Cut Line= 6
 1027581.2999811  676226.6082419 1027574.5275513  676097.1230442
 1027470.4424535  676081.1077426 1027337.3061204  675934.3790597
  1027125.814559  675838.9141002 1027032.5526241  675714.0753095
#Sta/Elev= 30
       0 2527.31   16.34  2520.5   24.39 2519.51   43.36 2518.44   67.27 2519.31
    75.9 2517.71   95.74 2518.08  130.47 2516.03  143.12 2519.76  152.47 2518.74
  164.38 2513.25   207.8 2514.32  229.45 2513.66   240.7 2511.26  256.33 2513.01
  271.37 2512.23  280.54 2513.04  300.05 2511.56  314.51 2508.82  319.29 2508.85
  348.05 2514.17  362.69 2515.08   398.4 2514.45  452.64  2516.6   587.7  2516.8
  684.81 2519.57  777.24 2524.24  817.83 2522.43  830.93 2528.52  848.77 2531.73
#Mann= 3 , 0 , 0
       0     .08       0  229.45     .05       0  256.33     .05       0
Bank Sta=229.45,256.33
Exp/Cntr=0.3,0.1

Type RM Length L Ch R = 1 ,409605.7,221.71,230.78,294.61
XS GIS Cut Line= 6
 1027496.6768902  675774.6732234 1027436.4276937  675802.0592053
 1027350.5243581  675801.4624721 1027181.6248355  675783.1038237
 1027114.0650144  675755.1986855 1027061.9264554  675705.9975127
#Sta/Elev= 30
       0 2534.87   26.85 2520.11   35.66  2511.4   41.03 2506.51   41.49 2506.36
   60.16 2509.84   72.04 2511.97   75.26 2513.46   86.88 2512.18   93.74 2511.63
  106.45 2512.29  114.81  2512.3  126.86  2513.6  157.29 2514.14  175.48 2514.24
  254.01 2516.14  277.25 2516.34  297.95 2516.88  329.52 2518.31  335.12 2518.41
  343.94 2519.01  350.06 2519.21  380.42 2520.95  405.55 2522.83  421.18 2523.05
  436.98 2522.38  442.94 2521.55  444.67 2522.13  452.48  2524.1  468.15 2529.11
#Mann= 3 , 0 , 0
       0      .1       0   35.66     .05       0   60.16     .05       0
#XS Ineff= 2 , 0
       0                   75.26       0 2513.46
Permanent Ineff=
       F       F
Bank Sta=35.66,60.16
Exp/Cntr=0.3,0.1