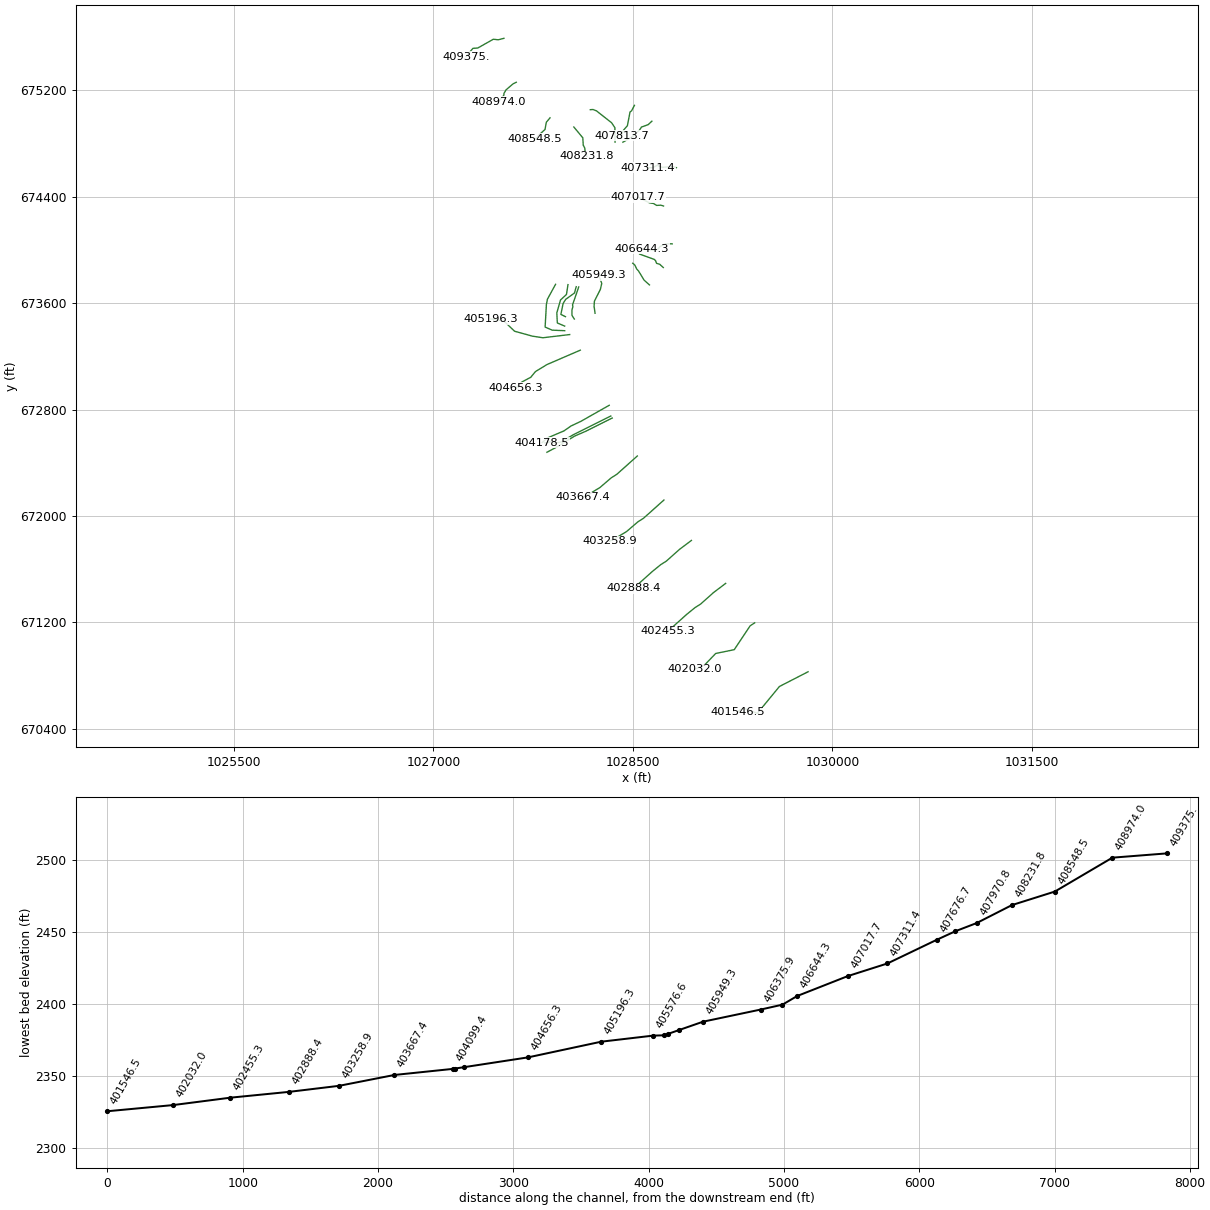
HEC-RAS study lds_broad_rvr.prj: Upper_Broad 3-06-07

--- lds_broad_rvr.g05 (geometry) --- (continued)

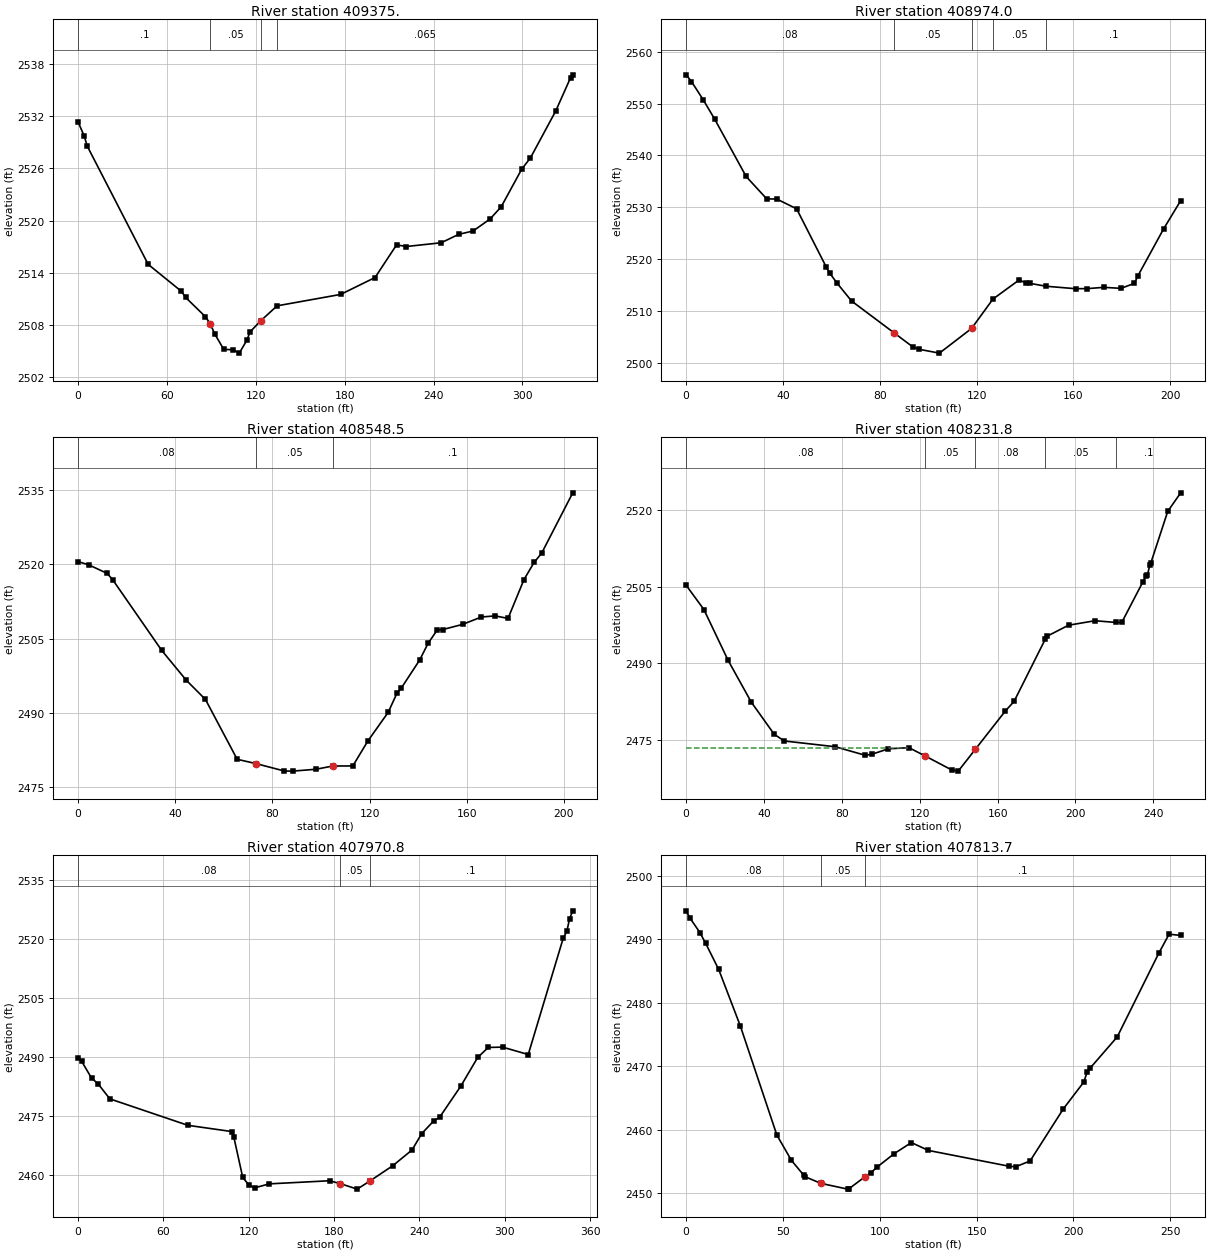
Type RM Length L Ch R = 1 ,409375. ,375.71,400.91,424.46
XS GIS Cut Line= 6
 1027529.5401048  675591.1869872 1027487.0918086  675580.2325824
 1027450.1206846  675584.3404918  1027333.730201  675518.6140928
  1027296.759077  675515.8754765  1027244.725669  675454.2569869
#Sta/Elev= 30
       0 2531.31    4.08 2529.72    6.16 2528.55   47.28 2514.98   69.76 2511.88
   72.58 2511.18   85.88 2508.98   89.27 2508.15   92.12 2507.02   98.28 2505.23
  104.64 2505.17  108.79 2504.79  113.91 2506.27  116.04 2507.22  123.26  2508.5
  134.34 2510.22  177.24 2511.53  200.47 2513.47  215.01 2517.22   221.6 2517.03
   245.1 2517.46  257.02 2518.43  266.63 2518.81  278.07 2520.18  285.64 2521.59
   299.5 2525.91  305.41 2527.21  322.46 2532.59  332.47 2536.41  333.95 2536.74
#Mann= 4 ,-1 , 0
       0      .1       0   89.27     .05       0  123.26     .08       0
  134.34    .065       0
Bank Sta=89.27,123.26
Exp/Cntr=0.3,0.1

Type RM Length L Ch R = 1 ,408974.0,397.41,425.58,415.31
XS GIS Cut Line= 6
 1027623.0284442  675260.9743685 1027599.2097553  675249.4492003
 1027546.1939699  675204.1168805 1027530.0587466  675177.2248114
  1027529.290394  675162.6262631 1027488.5681292   675115.757238
#Sta/Elev= 30
       0 2555.56    2.22 2554.27    7.04 2550.77   11.84 2546.98   24.81 2535.93
   33.29 2531.62   37.53 2531.56   45.66 2529.69   57.96  2518.4   59.39 2517.23
   62.46 2515.29   68.35 2511.89   85.97 2505.72   93.67 2503.02   96.25 2502.56
  104.67 2501.82  117.96 2506.59  126.78 2512.26  137.72 2515.99  140.26 2515.33
  142.23 2515.28  148.65 2514.74   160.9 2514.26  165.82 2514.28  172.55 2514.52
   179.7 2514.33   185.2 2515.29  186.67 2516.75  197.28 2525.81  204.34 2531.26
#Mann= 5 ,-1 , 0
       0     .08       0   85.97     .05       0  117.96     .08       0
  126.78     .05       0  148.65      .1       0
Bank Sta=85.97,117.96
Exp/Cntr=0.3,0.1

Type RM Length L Ch R = 1 ,408548.5,268.29,316.66,345.05
XS GIS Cut Line= 6
 1027876.5822034  674993.5904135  1027848.921812  674960.5515841
 1027838.9333189  674905.9991237 1027788.9909136  674860.6667735
 1027779.0024204  674843.7631977 1027765.1722247  674835.3113795
#Sta/Elev= 30
       0 2520.55    4.27 2519.93   11.93 2518.18   14.18 2516.93   34.38 2502.63
   44.48 2496.61   52.41  2492.7   65.47 2480.61    73.3 2479.73   84.93 2478.24
   88.28 2478.22   97.92  2478.6   104.8 2479.25  113.08 2479.27   119.3 2484.33
  127.66 2490.12  131.37  2494.1  133.03    2495  140.62 2500.69  144.05 2504.03
  147.84 2506.75  150.12 2506.83  158.24 2507.87  166.04 2509.37  171.71 2509.59
  176.97 2509.08  183.54 2516.93  187.71 2520.39  190.82 2522.27  203.62 2534.46
#Mann= 3 , 0 , 0
       0     .08       0    73.3     .05       0   104.8      .1       0
Bank Sta=73.3,104.8
Exp/Cntr=0.3,0.1

Type RM Length L Ch R = 1 ,408231.8,233.35,261.01,278.98
XS GIS Cut Line= 6
 1028055.6065462  674924.4393745   1028123.22088  674842.9948451
 1028126.2942601   674787.674032 1028137.8194283  674766.1603707
 1028142.4294834  674720.8280206 1028153.1863292  674704.6927973
#Sta/Elev= 30
       0 2505.27    9.14  2500.5   21.59 2490.53   33.51 2482.33   45.25 2476.05
   50.43 2474.73   76.62  2473.6   91.99 2471.93   95.46 2472.13  103.92  2473.2
   114.5 2473.41  122.86 2471.78  136.38 2469.06  139.78 2468.82  148.62 2473.12
  163.93 2480.58  168.46 2482.48  184.53 2494.71  185.56 2495.29  196.45 2497.42
  210.03  2498.3  220.89 2497.96  223.79 2497.96  234.65 2505.93  236.27 2507.07
  236.99 2507.35   238.2 2509.19   238.7  2509.6  247.39 2519.73  254.05 2523.37
#Mann= 5 ,-1 , 0
       0     .08       0  122.86     .05       0  148.62     .08       0
  184.53     .05       0  220.89      .1       0
#XS Ineff= 2 , 0
       0   113.9 2473.41               0
Permanent Ineff=
       F       F
Bank Sta=122.86,148.62
Exp/Cntr=0.3,0.1

Type RM Length L Ch R = 1 ,407970.8,225.25,157.13,69.18
XS GIS Cut Line= 6
 1028179.4615671  675054.7404153 1028199.4696084  675056.0312538
 1028225.9318721   675045.704516 1028339.1257546  674956.7098513
 1028364.4811185  674919.0609668 1028365.3428478  674810.7712534
#Sta/Elev= 30
       0 2489.62    2.38 2488.89    9.44 2484.55   13.91 2483.14    22.3 2479.27
   77.15 2472.54  108.28 2470.94  109.39 2469.69  115.73 2459.28  120.21 2457.27
  124.23 2456.64   134.4 2457.64  176.86 2458.43  184.34  2457.7  196.19  2456.3
  204.89  2458.3  221.32 2462.28   234.8 2466.27  241.58 2470.42  250.01 2473.65
  254.17 2474.58  269.07 2482.51  280.96 2489.81  288.38 2492.36  298.48 2492.44
   316.5 2490.56  341.07 2520.13   343.7 2521.99  345.53 2525.07   347.8 2527.13
#Mann= 3 , 0 , 0
       0     .08       0  184.34     .05       0  204.89      .1       0
Bank Sta=184.34,204.89
Exp/Cntr=0.3,0.1

Type RM Length L Ch R = 1 ,407813.7,154.39,136.97,82.82
XS GIS Cut Line= 6
 1028511.2349541  675087.3284637 1028489.7213231  675045.8378464
  1028478.196155  675038.1544111 1028458.2834579  674934.0466728
 1028428.5941131  674899.8393481 1028413.1039913  674860.4686696
#Sta/Elev= 30
       0 2494.48    1.94 2493.37    7.19 2491.03   10.15 2489.33   16.84 2485.24
   27.99 2476.35   46.89 2459.12   54.42 2455.13   60.84 2452.77   61.64 2452.54
   69.58 2451.52   83.46 2450.61   83.92 2450.63    92.3 2452.54   95.38 2453.17
   98.36 2454.02   107.5 2456.21  116.33 2457.95   125.1 2456.71  166.92 2454.21
  170.23 2454.14  177.63 2455.05  194.79 2463.26  205.31 2467.47   207.1 2469.05
  208.62 2469.68  222.63 2474.61   244.1 2487.81  249.41  2490.8  255.39  2490.6
#Mann= 3 , 0 , 0
       0     .08       0   69.58     .05       0    92.3      .1       0
#XS Ineff= 2 , 0
       0                  116.33       0 2457.95
Permanent Ineff=
       F       F
Bank Sta=69.58,92.3
Exp/Cntr=0.3,0.1

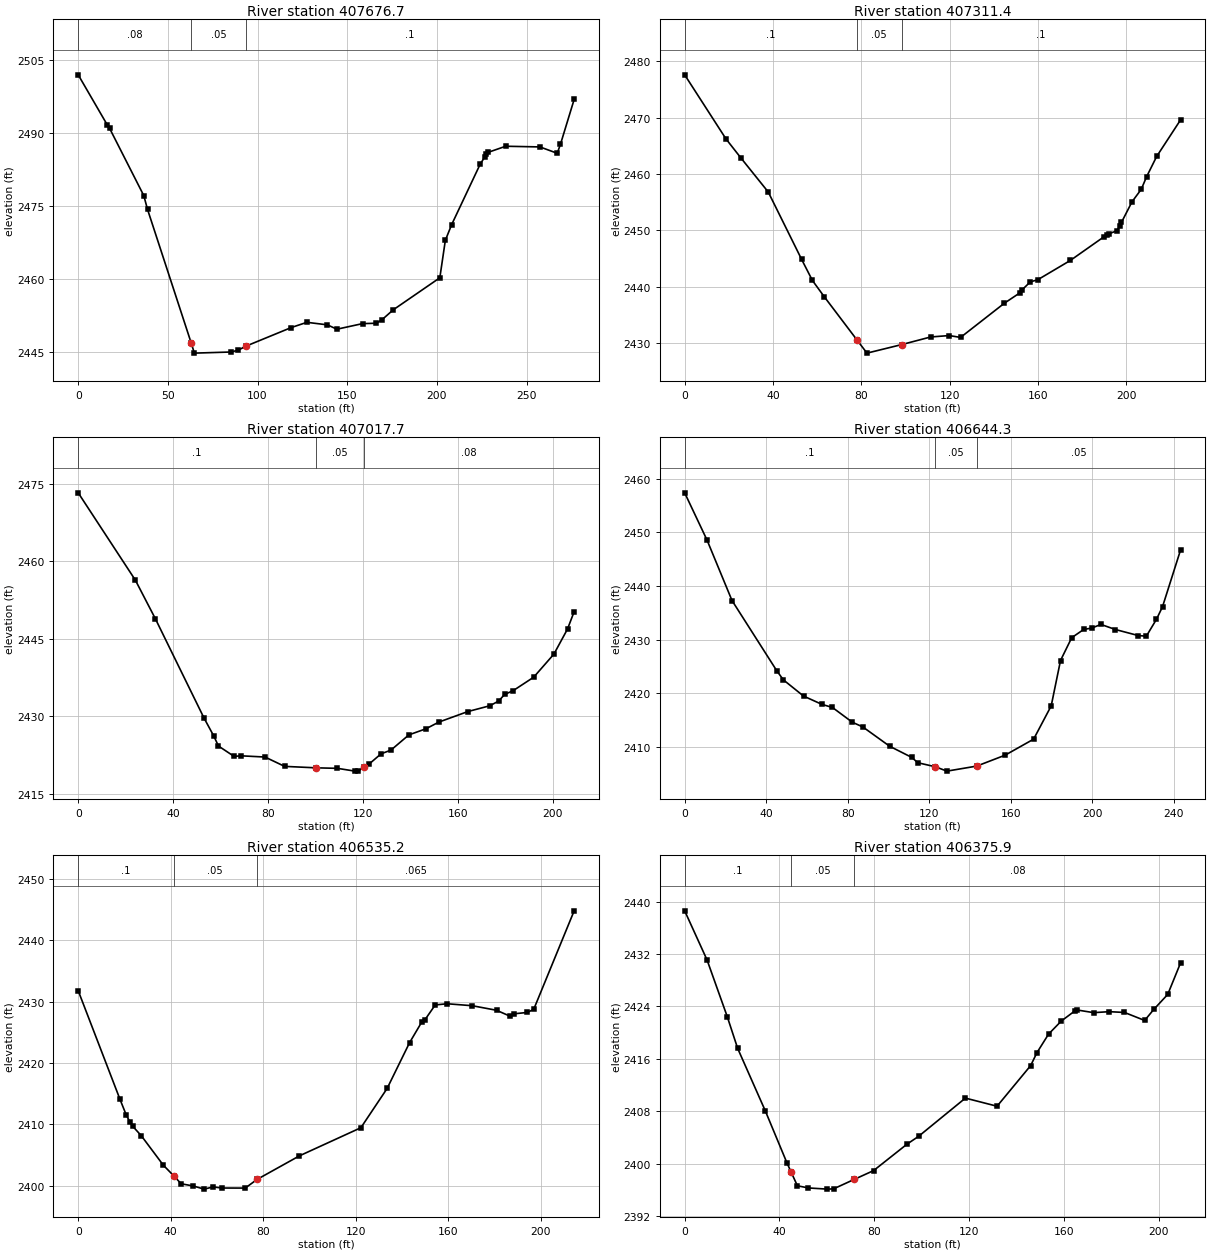
Type RM Length L Ch R = 1 ,407676.7,404.26,365.33,281.34
XS GIS Cut Line= 6
 1028642.6219192  674968.2350195 1028614.1931752   674942.111303
 1028563.4824173  674923.6710522 1028550.4205439  674902.1573909
 1028492.4907825  674850.1419318 1028424.7215675   674810.125819
#Sta/Elev= 30
       0 2502.04   16.23  2491.7   17.54 2490.98   36.54 2477.16   38.66 2474.29
   63.07 2446.68   64.76 2444.68      85 2444.91   89.08 2445.27    93.6 2446.13
  118.76 2449.95   127.5 2451.03  138.91 2450.51  144.22 2449.61   158.5 2450.76
  166.21 2450.84  169.41 2451.58  175.62  2453.6  201.61 2460.21  204.68 2467.92
  208.16 2471.13  224.06 2483.59  226.64  2485.1  227.29 2485.75  228.37 2486.04
  238.33 2487.32  257.43 2487.18  267.06 2485.87  268.87 2487.73   276.5 2496.97
#Mann= 3 , 0 , 0
       0     .08       0   63.07     .05       0    93.6      .1       0
#XS Ineff= 2 , 0
       0                   127.5       0 2451.03
Permanent Ineff=
       F       F
Bank Sta=63.07,93.6
Exp/Cntr=0.3,0.1

Type RM Length L Ch R = 1 ,407311.4,308.57,293.66,277.43
XS GIS Cut Line= 6
 1028827.0246697  674618.6381824  1028799.364248  674627.0899704
 1028718.6880409    674620.94321 1028682.5758313  674636.3101109
  1028646.463652  674617.8698298 1028613.4248226  674618.6381824
#Sta/Elev= 30
       0 2477.61   18.69 2466.24   25.44 2462.86   37.87 2456.79   52.96 2444.84
   57.87 2441.08   63.24 2438.19   77.95 2430.57   82.59 2428.17   98.35 2429.69
  111.45 2431.04  119.88 2431.29     125 2430.96  144.86 2437.04  151.95  2438.9
  153.02 2439.47   156.6 2440.83  159.94  2441.2  174.72 2444.63  190.05 2448.86
  191.57 2449.14  192.25 2449.38  195.74 2449.89  197.34 2450.82   197.9  2451.4
   202.7 2455.07  206.86 2457.27  209.29 2459.51  213.85 2463.11   224.7 2469.62
#Mann= 3 , 0 , 0
       0      .1       0   77.95     .05       0   98.35      .1       0
Bank Sta=77.95,98.35
Exp/Cntr=0.3,0.1

Type RM Length L Ch R = 1 ,407017.7,312.64,373.36,397.15
XS GIS Cut Line= 6
 1028730.1311525  674330.5584978 1028709.2978246  674336.6348851
 1028678.0478326  674334.8987744 1028653.7422834  674349.6557151
 1028624.2283718  674353.9959917  1028538.290894  674397.3987886
#Sta/Elev= 30
       0 2473.27    24.1 2456.35   32.55 2448.86      53 2429.68   57.12 2426.19
   59.15 2424.21   65.75  2422.2   68.52 2422.32   78.77 2422.08   87.05 2420.27
  100.24 2419.99  109.31 2419.89  116.68 2419.35  118.05 2419.37  120.65 2420.14
  122.76 2420.76   127.7  2422.7   131.9 2423.43  139.43 2426.37  146.66 2427.56
  152.07 2428.85  164.29 2430.89  173.61 2432.02  177.28 2432.93   179.8  2434.2
  183.48 2434.96  192.07 2437.55  200.59 2442.02  206.33 2446.88  209.13 2450.25
#Mann= 3 , 0 , 0
       0      .1       0  100.24     .05       0  120.65     .08       0
Bank Sta=100.24,120.65
Exp/Cntr=0.3,0.1

Type RM Length L Ch R = 1 ,406644.3,155.9,109.16,67.72
XS GIS Cut Line= 6
 1028795.0759415   674045.944436 1028745.5967573   674045.944436
 1028704.3641139  674026.1527805 1028687.0464116  674004.7118229
 1028663.9561519  673998.1145842 1028568.9076193   674008.981787
#Sta/Elev= 30
       0 2457.37      11 2448.54   23.23  2437.3   45.28 2424.17   48.44 2422.52
   58.33  2419.5   67.38 2417.95   72.54 2417.37   82.26 2414.63    87.5 2413.73
  100.61 2410.15  111.55 2408.05  114.38 2407.08  123.06 2406.32  128.72 2405.51
  143.39 2406.45  157.33 2408.49  171.29 2411.47  179.91 2417.67  184.48 2426.12
  189.99 2430.38  195.87 2431.91  199.94 2432.18   204.3 2432.85  211.42  2431.9
   222.6 2430.78  226.61 2430.65  231.59 2433.81  234.55 2436.14  243.44 2446.76
#Mann= 3 , 0 , 0
       0      .1       0  123.06     .05       0  143.39     .05       0
Bank Sta=123.06,143.39
Exp/Cntr=0.3,0.1

Type RM Length L Ch R = 1 ,406535.2,174.36,159.32,140.74
XS GIS Cut Line= 6
  1028728.279055  673867.8194457 1028701.0655097  673892.5590378
 1028677.9752198  673899.1562462 1028669.7287093   673919.772583
 1028660.6575174  673928.8437446 1028550.2056413   673968.790695
#Sta/Elev= 30
       0 2431.76   18.08 2414.07   20.77 2411.54   22.33 2410.42   23.65 2409.67
   27.25 2408.18   36.81 2403.37   41.21 2401.68   44.52 2400.35   49.77 2399.99
   54.46 2399.48    58.3 2399.84    62.2 2399.66   72.21 2399.65   77.33 2401.06
   95.67  2404.9  122.21 2409.47  133.57 2415.87  143.25  2423.3  148.52 2426.66
   149.9 2427.03  154.36 2429.45  159.55 2429.64  170.37 2429.32  180.87 2428.58
  186.62 2427.63  188.29    2428  194.24 2428.23  196.96 2428.75  214.42 2444.76
#Mann= 3 , 0 , 0
       0      .1       0   41.21     .05       0   77.33    .065       0
Bank Sta=41.21,77.33
Exp/Cntr=0.3,0.1

Type RM Length L Ch R = 1 ,406375.9,454.92,426.58,312.04
XS GIS Cut Line= 6
 1028624.1338449  673736.9386218 1028583.7258526  673773.2233588
 1028541.6685582  673842.4941682 1028528.4741111  673856.5132664
 1028514.5743293  673885.8282568 1028498.6200178  673900.1871432
#Sta/Elev= 30
       0 2438.61    9.45  2431.1   17.95 2422.47   22.35 2417.61      34 2408.08
   43.19 2400.09      452398.653   47.56 2396.62   52.24 2396.29    60.2 2396.11
   62.82 2396.15   71.57  2397.6   79.72 2398.94   93.83 2402.98    98.7 2404.17
  118.46 2410.01  131.82 2408.77  146.01 2414.98  148.65 2416.95  153.57 2419.79
  158.93 2421.78  164.74 2423.35   165.4 2423.48  172.58 2423.06  179.15 2423.21
  185.59 2423.09   194.1 2421.87  197.95 2423.55  203.85 2425.85  209.28 2430.68
#Mann= 3 , 0 , 0
       0      .1       0      45     .05       0   71.57     .08       0
Bank Sta=45,71.57
Exp/Cntr=0.3,0.1

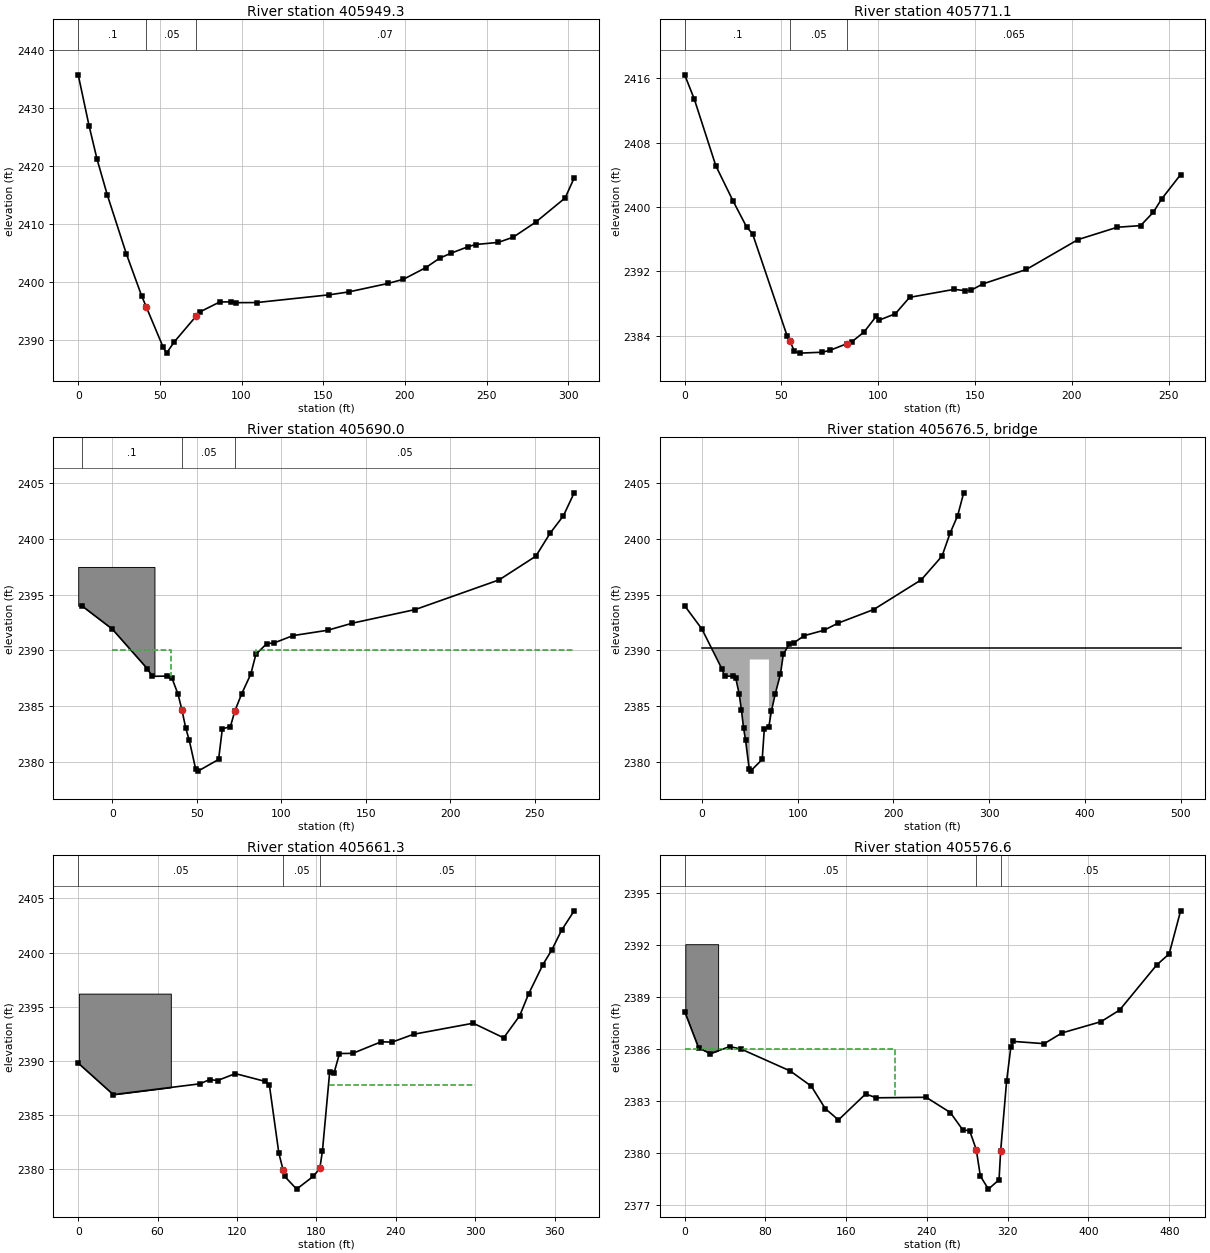
Type RM Length L Ch R = 1 ,405949.3,183.11,178.19,191.83
XS GIS Cut Line= 6
 1028215.3450113  673523.9392308 1028207.9231519  673575.0677171
  1028210.397105  673614.6510583 1028254.9283526  673702.8889024
 1028265.6488465  673748.2448011 1028242.8024862  673809.0979648
#Sta/Elev= 30
       0 2435.69    6.63 2426.91    11.5 2421.16   17.81 2414.95    29.5 2404.77
   38.77 2397.58   41.75 2395.57   51.99 2388.68   54.07 2387.65    58.8 2389.59
    72.42394.106   74.28 2394.73   86.63 2396.48   93.52  2396.5   96.36 2396.36
  109.24 2396.38   153.8 2397.72  165.52 2398.21  189.53 2399.67  199.13  2400.4
   212.8 2402.41   221.3 2404.04  228.32 2404.91  238.51    2406   243.3  2406.4
  257.11 2406.76  266.29 2407.66   280.1 2410.26  298.13 2414.44  303.63 2417.89
#Mann= 3 , 0 , 0
       0      .1       0   41.75     .05       0    72.4     .07       0
Bank Sta=41.75,72.4
Exp/Cntr=0.3,0.1

Type RM Length L Ch R = 1 ,405771.1,83.79,81.07,30.85
XS GIS Cut Line= 6
 1028059.2252645  673480.4514415 1028041.4266343   673508.217347
 1028041.4266343  673548.7982603 1028048.5460864  673573.7163729
 1028045.6982934  673586.5313806 1028092.3672472  673721.6845901
#Sta/Elev= 30
       0 2416.45    4.95 2413.44   16.09 2405.13   24.93 2400.78   32.04 2397.49
   35.04 2396.68   53.02 2383.89   54.39  2383.3   56.66 2382.05   59.36 2381.81
   70.98 2381.92   74.98 2382.15   83.88 2382.99   86.39 2383.23   92.64 2384.43
   99.07 2386.43  100.29  2385.9  108.84 2386.71  116.18 2388.75  139.29 2389.75
  144.82 2389.58  147.92 2389.63     154 2390.42  176.47 2392.22  203.19 2395.94
   223.5 2397.48  235.53 2397.68  242.09 2399.34  246.35 2400.98  256.21 2404.03
#Mann= 3 , 0 , 0
       0      .1       0   54.39     .05       0   83.88    .065       0
Bank Sta=54.39,83.88
Exp/Cntr=0.5,0.3

Type RM Length L Ch R = 1 ,405690.0,29.35,28.7,45.34
XS GIS Cut Line= 6
 1027992.6695844  673498.2157323 1027958.0834248   673515.508812
  1027975.215645  673597.9225222 1027994.1834364  673628.4304946
 1028060.3239921    673676.08455 1028073.4699499  673723.7386356
#Sta/Elev= 30
     -18    2394       0 2391.91   20.67 2388.36   23.76 2387.66   32.35 2387.68
   35.42 2387.47   38.97 2386.05   41.25 2384.64   43.53    2383   45.57 2381.93
   49.42 2379.31   50.77 2379.14   62.96 2380.19   65.18 2382.94   69.96 2383.14
   72.58 2384.54   76.63 2386.09   82.03 2387.86   85.02 2389.63    91.4 2390.59
   96.01 2390.67  107.02 2391.32  127.54  2391.8  142.22 2392.44  179.37 2393.66
  229.05 2396.33  250.77 2398.46  259.24 2400.53  267.08 2402.09  273.43 2404.15
#Mann= 3 , 0 , 0
     -18      .1       0   41.25     .05       0   72.58     .05       0
#XS Ineff= 2 , 0
       0      35    2390      85       0    2390
Permanent Ineff=
       F       F
#Block Obstruct= 1 ,-1
  -20.13      25 2397.49
Bank Sta=41.25,72.58
Exp/Cntr=0.5,0.3

Type RM Length L Ch R = 3 ,405676.5,,,
BEGIN DESCRIPTION:
STR_162
END DESCRIPTION:
Bridge Culvert--1,0,-1,-1, 0
Deck Dist Width WeirC Skew NumUp NumDn MinLoCord MaxHiCord MaxSubmerge Is_Ogee
2,24,2.6,0, 6, 6, , , 0.95, 0, 0,0,,
       0      50      50      70      70     500
 2390.17 2390.17 2390.17 2390.17 2390.17 2390.17
                 2389.17 2389.17
       0     155     155     175     175     500
 2390.17 2390.17 2390.17 2390.17 2390.17 2390.17
                 2389.17 2389.17
BR Coef= 1 , 1 , 0 ,, 0 ,,,0.8,0,2,0,
WSPro=,,,, 1 ,,,, 0 ,,,, 0 ,,,,-1 ,-1 ,-1 , 0 , 0 , 0 , 0 , 0
BC Design=,, 0 ,, 0 ,,,,,,

Type RM Length L Ch R = 1 ,405661.3,86.45,84.67,106.34
XS GIS Cut Line= 6
 1027986.8401829   673427.441195  1027931.380682  673451.0628394
 1027927.7072997  673526.9362146 1027955.2811852  673623.5525679
 1028000.1915392  673665.4548297   1028011.48885  673739.1440677
#Sta/Elev= 30
       0  2389.8    26.5 2386.89   92.11 2387.89    99.3 2388.28  105.29 2388.19
  118.78 2388.83  141.01 2388.12  144.45 2387.81  151.66 2381.48  154.96 2379.89
  155.93 2379.36   165.1 2378.17  177.76 2379.36  182.62 2380.09  184.57 2381.66
  190.04 2388.94  193.45 2388.93  197.48 2390.68  207.51  2390.7  229.08 2391.77
  237.16 2391.73  253.49 2392.46  298.59 2393.48  321.59 2392.13   333.7 2394.17
  340.38 2396.17  351.25 2398.89  358.04 2400.26  365.35 2402.06  374.85 2403.85
#Mann= 3 , 0 , 0
       0     .05       0  154.96     .05       0  182.62     .05       0
#XS Ineff= 3 ,-1
       0  118.78 2387.81     125  144.45 2387.81  189.19     300 2387.81
Permanent Ineff=
       T       T       T
#Block Obstruct= 1 ,-1
     .51      70 2396.21
Bank Sta=154.96,182.62
Exp/Cntr=0.5,0.3

Type RM Length L Ch R = 1 ,405576.6,218.88,380.31,629.42
XS GIS Cut Line= 6
 1027987.1611143  673392.8231642 1027892.8832044  673396.8349727
 1027839.7265215  673419.9029855 1027849.2012157  673589.3791736
 1027857.0326312  673629.9600869  1027918.259998  673741.7356119
#Sta/Elev= 30
       0 2388.16   13.76 2386.07   25.29 2385.74   44.67 2386.14   55.82    2386
   104.6 2384.73  125.46 2383.85  139.18 2382.56  152.31  2381.9   179.2  2383.4
   189.9 2383.18  239.18 2383.21  263.09 2382.33  275.53 2381.32  282.27 2381.28
  288.85 2380.18  292.86 2378.66  300.84  2377.9  311.39 2378.44     313 2380.11
  318.91 2384.16  323.05 2386.09  325.64 2386.44  356.14 2386.31  373.74 2386.93
  412.33 2387.58  430.77 2388.25  467.55 2390.86  479.91  2391.5  491.25 2393.99
#Mann= 3 , 0 , 0
       0     .05       0  288.85     .05       0     313     .05       0
#XS Ineff= 2 , 0
       0  207.96    2386               0
Permanent Ineff=
       F       F
#Block Obstruct= 1 ,-1
     .64   33.12 2392.06
Bank Sta=288.85,313
Exp/Cntr=0.3,0.1

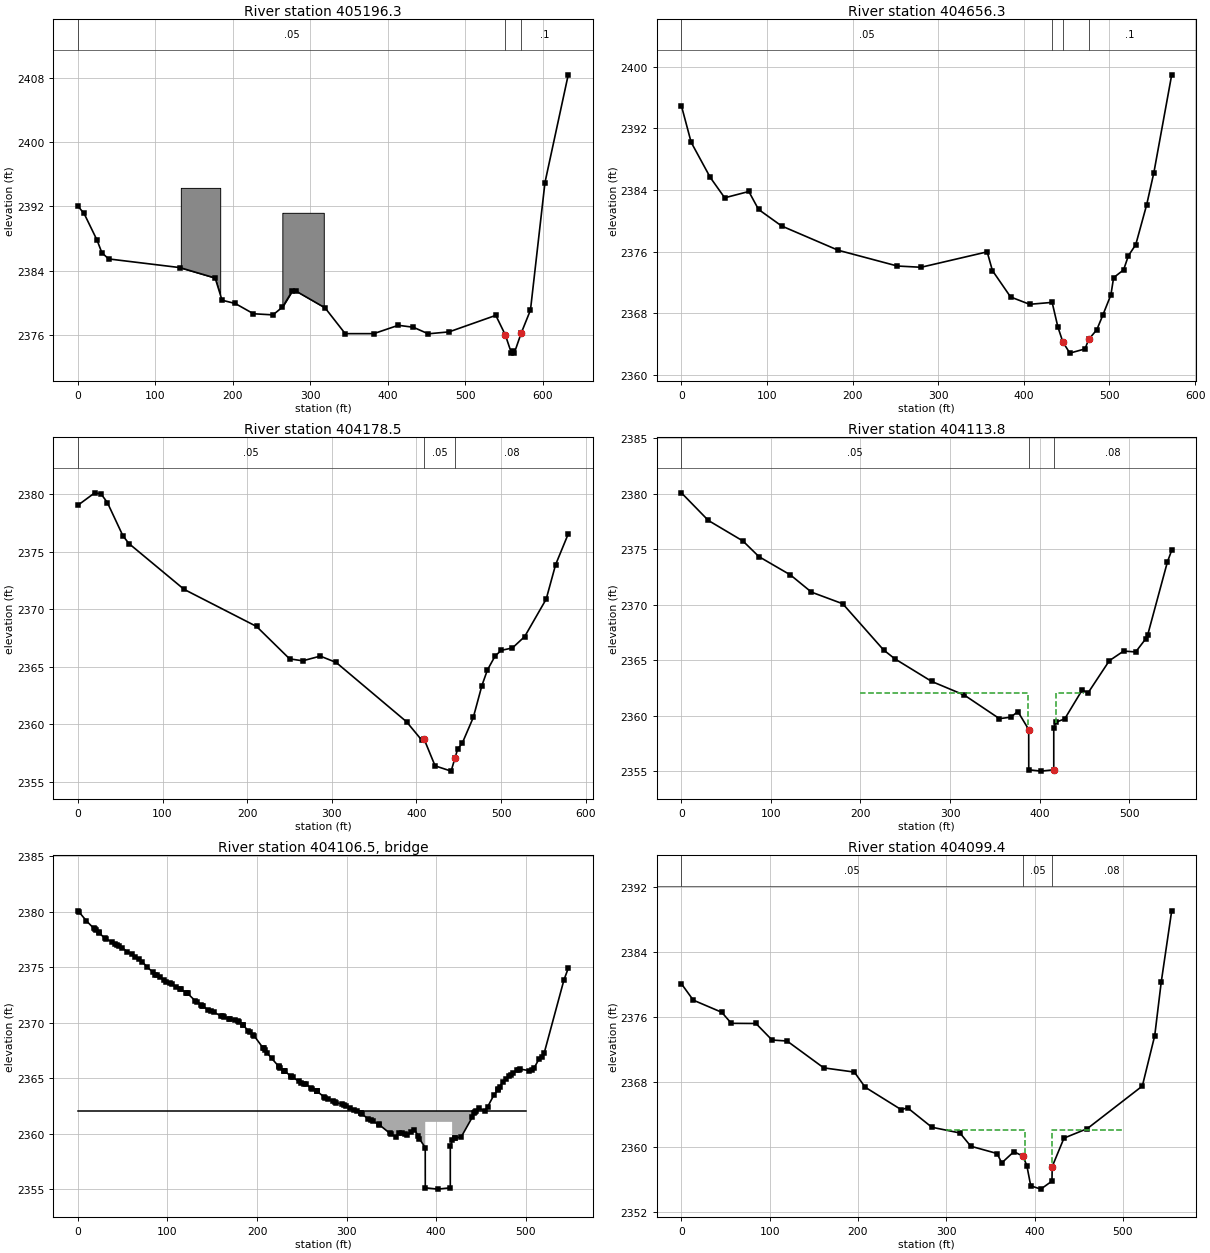
Type RM Length L Ch R = 1 ,405196.3,298.67,539.99,551.08
XS GIS Cut Line= 6
 1028024.2705327  673363.7374234  1027822.676267   673339.666451
 1027744.4456519  673351.7019372 1027610.0494748  673388.8113253
 1027528.8099806  673466.0389807 1027431.5231917  673481.0833158
#Sta/Elev= 30
       0 2392.03    7.87 2391.14   24.73 2387.79   30.88 2386.24   39.56 2385.46
  131.49 2384.38  177.17 2383.08  186.09 2380.31  203.15  2379.9  226.66 2378.62
  251.86 2378.48  264.11 2379.45  276.44  2381.4  282.21 2381.41  319.07 2379.36
  345.11 2376.14  381.98 2376.14  413.71 2377.18  432.98 2376.94  452.35 2376.12
  479.21 2376.36  539.58 2378.42  551.87 2375.98  559.75 2373.71  561.15 2374.01
  563.51 2373.73  572.19 2376.16  584.34 2379.08  603.07 2394.99   633.1 2408.42
#Mann= 3 , 0 , 0
       0     .05       0  551.87     .05       0  572.19      .1       0
#XS Ineff= 2 , 0
       0  539.58 2378.42               0
Permanent Ineff=
       F       F
#Block Obstruct= 2 ,-1
  132.87   183.7 2394.32  263.95  317.45 2391.21
Bank Sta=551.87,572.19
Exp/Cntr=0.3,0.1

Type RM Length L Ch R = 1 ,404656.3,495.55,477.88,457.17
XS GIS Cut Line= 6
 1028104.3503395  673246.3601432 1027853.6111996  673138.2288827
 1027766.9509224  673085.4192826 1027731.6210795  673042.4505286
 1027666.6905165  673008.0755193 1027620.8571708  672962.2422039
#Sta/Elev= 30
       0 2394.94   11.39 2390.19   33.68 2385.63   50.57 2382.98   78.74  2383.8
   90.09 2381.47  117.08 2379.32  183.11 2376.17  252.28 2374.12  279.92 2373.96
  357.14 2375.96  363.27 2373.53  384.52  2370.1  406.73 2369.15  433.02  2369.4
  439.72 2366.21  445.54 2364.26  453.69 2362.81  471.49 2363.36  475.63 2364.58
   485.2 2365.85   492.2 2367.74  501.67 2370.38  504.81 2372.61  516.47 2373.62
  522.09 2375.46  530.66 2376.89  543.37 2382.05  551.84 2386.25  572.66 2398.95
#Mann= 4 ,-1 , 0
       0     .05       0  433.02     .08       0  445.54     .05       0
  475.63      .1       0
Bank Sta=445.54,475.63
Exp/Cntr=0.3,0.1

Type RM Length L Ch R = 1 ,404178.5,67.81,64.71,36.98
XS GIS Cut Line= 6
 1028321.4208643  672831.8429738 1028109.1526872  672711.5321211
 1028034.1396186    672675.99352 1027980.9536969   672639.125973
 1027853.9710555  672585.0907923 1027817.9544322  672551.3730824
#Sta/Elev= 30
       0 2379.05   19.87 2380.13   27.36 2380.03   34.82 2379.28   53.09  2376.4
    60.2 2375.72  125.44 2371.73   211.1  2368.5  250.16 2365.68  265.68 2365.51
  286.42 2365.92  305.13 2365.37  388.31 2360.21  406.38  2358.6  408.98 2358.72
  422.08 2356.37  441.04 2355.91  445.44 2357.01  448.81 2357.84  454.05 2358.32
  467.24 2360.58  477.44 2363.36  483.97 2364.72  493.04 2365.93  500.27 2366.42
  513.48 2366.63  527.98 2367.62   553.4 2370.88  564.53 2373.88  579.44 2376.55
#Mann= 3 , 0 , 0
       0     .05       0  408.98     .05       0  445.44     .08       0
Bank Sta=408.98,445.44
Exp/Cntr=0.5,0.3

Type RM Length L Ch R = 1 ,404113.8,16.12,14.35,57.57
XS GIS Cut Line= 6
  1028333.681847  672751.3803072  1028050.913012   672610.379052
 1027961.0089459  672555.7207445 1027913.2624824  672548.4681133
  1027880.625642  672557.5339174 1027837.7142458  672548.4681133
#Sta/Elev= 30
       0 2380.08    30.1 2377.59    68.7 2375.74   86.59 2374.33  121.76 2372.68
  145.25 2371.13   180.2 2370.08  225.79 2365.92   238.4 2365.12  279.58 2363.08
     316 2361.85  355.14 2359.73  367.86 2359.86  375.72 2360.37  387.85 2358.75
  387.91 2355.12  401.77    2355  415.84 2355.12  415.84 2358.89  418.08  2359.4
  428.09 2359.71  447.71 2362.33  454.06 2362.04  477.88 2364.95  493.86 2365.82
   507.3 2365.74  518.42 2366.91  520.62 2367.24  542.79 2373.86  547.54  2374.9
#Mann= 3 , 0 , 0
       0     .05       0  387.85     .05       0  415.84     .08       0
#XS Ineff= 2 ,-1
     200  387.37    2362  417.91     450    2362
Permanent Ineff=
       F       F
Bank Sta=387.85,415.84
Exp/Cntr=0.5,0.3

Type RM Length L Ch R = 3 ,404106.5,,,
BEGIN DESCRIPTION:
STR_161
END DESCRIPTION:
Bridge Culvert--1,0,-1,-1, 0
Deck Dist Width WeirC Skew NumUp NumDn MinLoCord MaxHiCord MaxSubmerge Is_Ogee
1,12,2.6,0, 4, 4, , , 0.95, 0, 0,0,,
       0  387.85  417.85     500
 2362.06 2362.06 2362.06 2362.06
         2361.06 2361.06
       0  389.78  419.78     500
 2362.06 2362.06 2362.06 2362.06
         2361.06 2361.06
BR Coef= 1 , 1 , 0 ,, 0 ,,,0.8,0,2,0,
WSPro=,,,, 1 ,,,, 0 ,,,, 0 ,,,,-1 ,-1 ,-1 , 0 , 0 , 0 , 0 , 0
BR U #Sta/Elev= 147
       0 2380.08    1.16 2379.98    9.43 2379.18   17.77  2378.5   18.68 2378.42
    20.6 2378.31   23.29 2378.14   23.67 2378.11    30.1 2377.59   31.29 2377.57
   37.83 2377.27   41.45 2377.13   43.28 2376.99   46.09 2376.92   49.44 2376.75
   55.26 2376.39    60.6 2376.17   64.18 2375.93    68.7 2375.74    71.8 2375.49
   77.17 2375.03   83.88 2374.54   86.59 2374.33   87.83 2374.28   91.37 2374.16
   95.61 2373.86   98.42 2373.71  102.47 2373.59  104.74 2373.49  109.92 2373.21
  113.51 2373.05  114.87 2373.01  121.18  2372.7  121.76 2372.68  122.39 2372.64
  130.89 2371.98  133.29 2371.84  137.57 2371.63  138.55 2371.54  139.88 2371.49
  145.25 2371.13  148.99 2371.06   151.7 2370.96  160.12 2370.58   161.5 2370.59
  163.28 2370.54  168.68 2370.33  170.28 2370.33  175.78 2370.21  178.37 2370.18
   180.2 2370.08  183.95 2369.81  184.71 2369.78  190.34 2369.24  191.69 2369.15
  195.59 2368.92  196.65 2368.83  206.38 2367.76  207.32 2367.68  208.59 2367.53
  211.24 2367.27  216.38 2366.78  224.39 2366.06  224.48 2366.05  225.79 2365.92
   230.4 2365.65  230.57 2365.65  230.81 2365.64  237.77 2365.18   238.4 2365.12
  239.83 2365.08  246.36 2364.74  249.59 2364.55  252.82 2364.47  254.59 2364.45
  259.87 2364.14  261.82 2364.02  267.03 2363.81  267.18  2363.8  267.25  2363.8
  274.46 2363.33  276.09 2363.23  279.58 2363.08  285.04 2362.95  286.89 2362.89
  288.49  2362.8   294.7 2362.66  297.52 2362.55  299.58 2362.49  303.83 2362.33
  308.38  2362.1  311.46 2362.03     316 2361.85  316.11 2361.84  317.46 2361.75
  323.63 2361.36  327.41 2361.23  329.09 2361.14  335.78 2360.83  336.53  2360.8
  348.36 2360.03  350.15 2359.93  355.14 2359.73  358.03 2360.07  362.39 2360.09
  365.77 2359.94  367.86 2359.86   371.5 2360.15  375.72 2360.37  380.03  2359.8
  381.32 2359.53  387.85 2358.75  387.91 2355.12  401.77    2355  415.84 2355.12
  415.84 2358.89  418.08  2359.4  421.09 2359.58  421.22 2359.59  428.09 2359.71
  440.41 2361.48  442.46 2361.87  442.96 2361.93  444.57 2362.07  447.71 2362.33
  454.06 2362.04  457.53 2362.42  464.62 2363.49  468.64  2363.9  469.54 2364.03
  470.96 2364.23  474.75 2364.68  477.88 2364.95  481.68 2365.18   483.2 2365.26
  485.78 2365.44  490.65  2365.7  492.19 2365.73  493.86 2365.82  503.68 2365.68
   507.3 2365.74  509.23 2365.89  515.11 2366.75  518.42 2366.91  520.62 2367.24
  542.79 2373.86  547.54  2374.9
BR U #Mann= 3
       0     .05  387.85     .05  415.84     .08
BR D #Sta/Elev= 155
       0 2380.09     .67 2379.97       5 2379.52    5.45 2379.48    6.05 2379.34
    7.36 2379.09   13.44 2378.07   19.92 2377.57   22.97 2377.82   24.66 2377.52
   27.56 2377.34   34.37 2376.73   38.58 2376.94   40.17 2376.91   45.74 2376.57
   49.25 2375.71   50.35 2375.61   56.55 2375.21   57.21 2375.19   61.47 2375.34
   67.39 2375.49   68.47 2375.64   68.81 2375.61   72.95 2375.38   74.63 2374.93
    83.8  2375.2   84.45 2375.19   85.13 2375.16   94.05  2373.9   95.62  2373.8
   97.54 2373.69  102.69 2373.15   104.5 2373.09  113.31 2373.19  113.93 2373.23
  114.18 2373.23   114.3 2373.22  119.09 2373.06   119.7 2373.03  122.25 2372.61
  128.83 2371.84  132.61 2371.54  137.55 2371.41  139.94 2371.27   142.8 2371.49
  146.59 2370.81  152.96 2370.94  158.45  2370.3  161.21 2369.72  172.52  2369.9
  172.89 2369.92  173.03 2369.88  179.65 2369.06   184.4 2369.75  186.89 2369.64
  188.93 2369.58  192.66 2369.33  195.91  2369.2  199.02 2368.93  204.93 2367.81
  206.97 2367.45   208.1 2367.34  209.54 2367.26  223.16 2366.93  228.21 2366.58
  229.97 2366.45   230.7 2366.42  234.71 2366.08     241 2365.67  241.95  2365.6
  243.49 2365.23  249.09 2364.56  253.73 2364.86  256.11  2364.8  258.71 2364.58
   262.8 2364.31  265.95 2364.11  270.44 2363.79  271.27 2363.79  273.88 2363.52
  278.56 2363.21  279.63 2363.17  283.66  2362.4  289.66 2362.71  290.96 2362.68
  292.15 2362.62  296.73 2362.49  300.95 2362.33  303.99 2362.17  307.86 2361.94
   312.3 2361.85  315.53 2361.69  319.72 2361.21  322.67 2360.73  327.76 2360.06
  331.85 2360.43  333.18 2360.38  340.51 2359.53  340.64 2359.52  340.76 2359.52
   341.3  2359.5  357.57 2359.16  362.84    2358  366.51 2357.93  369.38 2358.56
  376.57 2359.39  379.85 2359.12  383.08 2359.22  385.45  2358.8  386.652358.826
  386.85 2358.83     3892358.364  392.52  2357.6  395.14 2357.03  397.78 2355.26
  405.87 2354.96  407.09 2354.77  415.08 2355.06  419.73 2355.76  420.01 2357.55
  421.09  2357.7   423.9 2358.41  428.57 2359.55  433.35 2361.06  438.28 2361.48
  438.66 2361.52  439.13 2361.55  444.94  2361.8  446.86 2361.88   448.7 2361.97
  451.98 2362.08  459.12 2362.21  459.78 2362.23  460.83 2362.33   470.1 2363.17
  472.35 2363.29  477.57 2363.64  477.84 2363.67  478.38 2363.71  485.22 2364.32
   488.6  2364.5   490.7 2364.57  498.46 2365.13  499.96 2365.24  503.98 2365.56
  510.64 2366.18  511.76 2366.28  517.18 2366.78  522.09 2367.48  526.79 2369.26
  531.51 2371.64  536.12 2373.69  541.75 2378.54  543.47 2380.28  555.34 2389.08
BR D #Mann= 3
       0     .05  386.85     .05  420.01     .08
BC Design=,, 0 ,, 0 ,,,,,,

Type RM Length L Ch R = 1 ,404099.4,404.4,432,436.06
XS GIS Cut Line= 6
 1028344.4102106  672736.0540865 1028146.7019295  672637.1999308
 1028061.6413756  672600.4170131 1027968.9177264  672543.7099872
 1027950.5262675  672530.6826799 1027853.2047611  672478.5735414
#Sta/Elev= 30
       0 2380.09   13.44 2378.07   45.74 2376.57   56.55 2375.21   84.45 2375.19
  102.69 2373.15   119.7 2373.03  161.21 2369.72  195.91  2369.2   208.1 2367.34
  249.09 2364.56  256.11  2364.8  283.66  2362.4  315.53 2361.69  327.76 2360.06
  357.57 2359.16  362.84    2358  376.57 2359.39  386.85 2358.83  391.27 2357.67
  395.69 2355.18  407.09 2354.77  419.73 2355.76  420.01 2357.55  433.35 2361.06
  459.78 2362.23  522.09 2367.48  536.12 2373.69  543.47 2380.28  555.34 2389.08
#Mann= 3 , 0 , 0
       0     .05       0  386.85     .05       0  420.01     .08       0
#XS Ineff= 2 ,-1
     300  389.32    2362  419.92     500    2362
Permanent Ineff=
       F       F
Bank Sta=386.85,420.01
Exp/Cntr=0.5,0.3

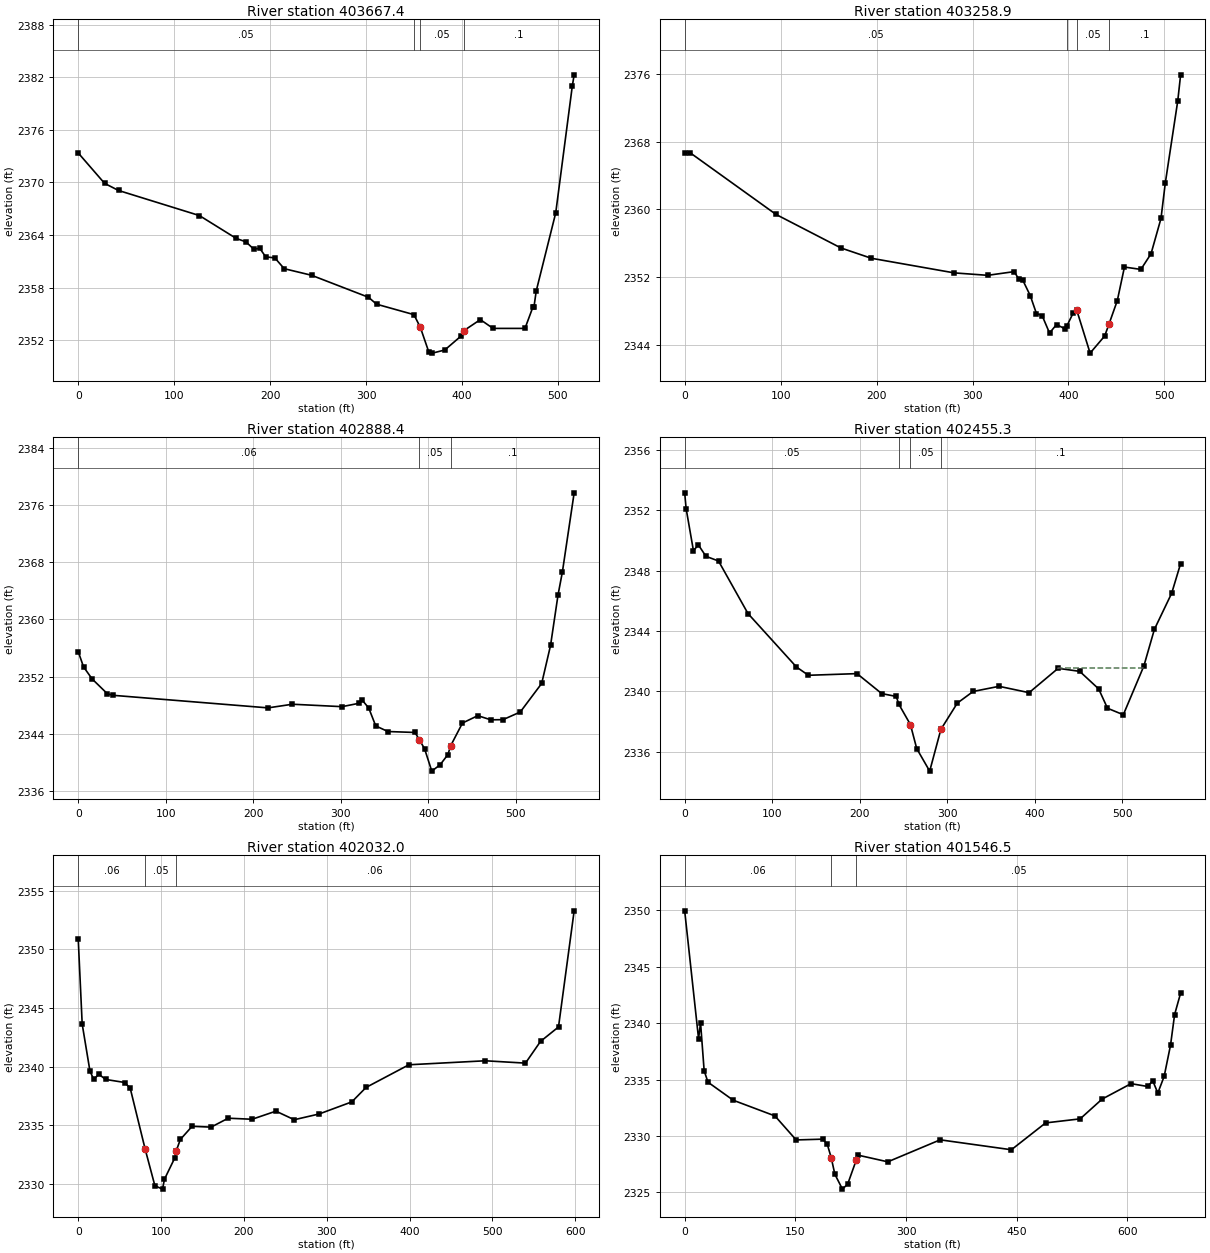
Type RM Length L Ch R = 1 ,403667.4,389.88,408.5,400.79
XS GIS Cut Line= 6
   1028532.74913  672450.5253264 1028378.5888715  672312.8287896
 1028336.9270887  672286.5480126 1028251.1042963  672212.8129489
 1028158.5737568  672157.1718401 1028122.6529316  672140.7081185
#Sta/Elev= 30
       0 2373.37    27.5  2369.9   42.04 2369.09  126.31 2366.23  164.72 2363.62
  174.84 2363.23  182.91  2362.4   189.2 2362.49  195.45 2361.52  204.94  2361.4
  214.71 2360.17   243.2 2359.42  302.55 2356.91  310.98 2356.12  349.89 2354.93
  356.58 2353.48  365.44 2350.66   369.2 2350.54  382.09  2350.9  399.14  2352.5
  401.88  2353.1  419.11 2354.36  432.41 2353.36  465.66 2353.36  473.83 2355.77
     475  2355.8  477.38 2357.63   497.7 2366.54  514.97    2381   516.9 2382.28
#Mann= 4 ,-1 , 0
       0     .05       0  349.89     .08       0  356.58     .05       0
  401.88      .1       0
Bank Sta=356.58,401.88
Exp/Cntr=0.3,0.1

Type RM Length L Ch R = 1 ,403258.9,358.16,370.54,398.6
XS GIS Cut Line= 6
 1028733.3071412  672119.7542937 1028579.1468827  671982.0577569
 1028537.4850999  671955.7769799 1028451.6623075  671882.0419162
  1028359.131768  671826.4008074 1028323.2109428  671809.9370858
#Sta/Elev= 30
       0 2366.68     5.6 2366.69   95.22 2359.39  162.79 2355.43  194.45 2354.21
  280.84 2352.48  315.79 2352.19  343.53 2352.63  347.99 2351.77  352.29 2351.64
  360.18 2349.79  366.63 2347.67  372.53 2347.43  380.26 2345.37  387.59 2346.37
  396.39 2345.86  398.21 2346.17  404.91 2347.74  408.47 2348.13  422.55 2342.99
  437.77 2345.02  442.26 2346.43   450.9  2349.2  458.34 2353.17  475.48 2352.89
  486.05 2354.74  496.44 2358.92   500.9 2363.09  513.91 2372.82  516.89  2375.9
#Mann= 4 ,-1 , 0
       0     .05       0  398.21     .08       0  408.47     .05       0
  442.26      .1       0
#XS Ineff= 2 , 0
       0  408.47 2348.13               0
Permanent Ineff=
       F       F
Bank Sta=408.47,442.26
Exp/Cntr=0.3,0.1

Type RM Length L Ch R = 1 ,402888.4,422.16,433.07,418.73
XS GIS Cut Line= 6
 1028939.8519464  671815.9239102 1028848.5531623  671747.0756418
 1028751.2675537  671660.2669305  1028709.605771  671633.9861535
 1028644.3320902  671580.8002317 1028504.3117899  671455.2188464
#Sta/Elev= 30
       0  2355.5    6.07 2353.36   15.88 2351.67   33.27  2349.6   39.64 2349.38
  216.92 2347.62  244.73 2348.13   301.4 2347.79   320.3 2348.25   324.2 2348.75
  331.97 2347.59   339.9  2345.1  353.86 2344.31  384.73 2344.18  389.87 2343.16
  395.79 2341.87  403.95 2338.77  413.48 2339.66  422.36 2341.08  425.62 2342.34
  439.03  2345.5  456.52 2346.53  471.41 2345.95   485.3 2345.97  505.04 2347.04
  529.53 2351.04  539.66 2356.37   548.2 2363.42  553.17 2366.63  566.62 2377.71
#Mann= 3 , 0 , 0
       0     .06       0  389.87     .05       0  425.62      .1       0
Bank Sta=389.87,425.62
Exp/Cntr=0.3,0.1

Type RM Length L Ch R = 1 ,402455.3,374.39,423.28,365.62
XS GIS Cut Line= 6
 1029197.2846075  671492.6363928 1029105.9858234  671423.7881244
 1029008.7002149  671336.9794131 1028967.0384321  671310.6986362
 1028901.7647513  671257.5127144  1028761.744451  671131.9313291
#Sta/Elev= 30
       0 2353.14    1.64  2352.1    9.99 2349.32    15.7 2349.69   24.32 2348.94
   38.66 2348.63   72.37 2345.15  127.68 2341.62  141.35 2341.07   196.9 2341.18
   225.1 2339.86  241.68 2339.67  244.82 2339.14   257.9 2337.81  265.11 2336.22
  279.92 2334.73  292.71 2337.49   311.5 2339.23  329.57    2340  359.19 2340.34
  393.47 2339.92  426.65 2341.53  451.34 2341.33  472.96 2340.17  483.07 2338.89
  501.14 2338.46  524.59 2341.68  536.65 2344.11  556.41  2346.5  566.61 2348.46
#Mann= 4 ,-1 , 0
       0     .05       0  244.82     .08       0   257.9     .05       0
  292.71      .1       0
#XS Ineff= 2 ,-1
  426.32     525 2341.52  359.19     415 2340.34
Permanent Ineff=
       F       F
Bank Sta=257.9,292.71
Exp/Cntr=0.3,0.1

Type RM Length L Ch R = 1 ,402032.0,541.57,485.51,580.43
XS GIS Cut Line= 6
  1029415.803001  671196.2894944 1029381.3788668  671173.8389786
 1029261.6427426  670994.2347922 1029122.4495147  670965.7974824
 1029041.6276278  670881.9821833 1028966.7925653  670847.5580491
#Sta/Elev= 30
       0 2350.91    4.79 2343.64    14.2 2339.62   18.75 2338.93   24.95 2339.36
   33.13 2338.92   56.29 2338.66   62.85 2338.15   80.82 2332.98   92.54 2329.87
  101.74 2329.58  104.14 2330.43  116.78 2332.27   118.4 2332.85  123.25 2333.81
  137.46 2334.93  160.36 2334.86  181.07 2335.62  209.87 2335.53  238.62 2336.22
  260.76 2335.49  290.79 2335.98  330.24 2337.01  347.42 2338.24  399.14 2340.17
  491.31 2340.51  539.81 2340.31  557.99 2342.16  579.69 2343.39  598.58 2353.28
#Mann= 3 , 0 , 0
       0     .06       0   80.82     .05       0   118.4     .06       0
#XS Ineff= 2 , 0
       0                  238.62       0 2336.22
Permanent Ineff=
       F       F
Bank Sta=80.82,118.4
Exp/Cntr=0.3,0.1

Type RM Length L Ch R = 1 ,401546.5,173.6,261.39,13.53
XS GIS Cut Line= 6
 1029816.9189931  670828.1009455 1029601.3939815  670717.3450276
 1029435.2601349  670515.2903254 1029327.4976291  670555.7012538
 1029285.5899795  670525.7672227 1029285.5899795  670524.2705317
#Sta/Elev= 30
       0 2349.96    18.8 2338.63   21.51 2340.03   26.37 2335.79   31.56 2334.77
   65.78 2333.17  122.28 2331.78  151.05 2329.65  186.91 2329.72  193.12 2329.29
  198.57 2328.07  203.48 2326.61  213.75 2325.29  220.89 2325.74  232.35 2327.84
  235.04  2328.3  275.21 2327.71  346.18 2329.66  442.68 2328.78  489.05 2331.16
  535.87 2331.52  565.58 2333.27  604.84 2334.64  627.18 2334.39  634.26 2334.89
   641.1 2333.81  649.66 2335.28  658.34 2338.06  663.83 2340.76  671.99 2342.67
#Mann= 3 , 0 , 0
       0     .06       0  198.57     .05       0  232.35     .05       0
Bank Sta=198.57,232.35
Exp/Cntr=0.3,0.1