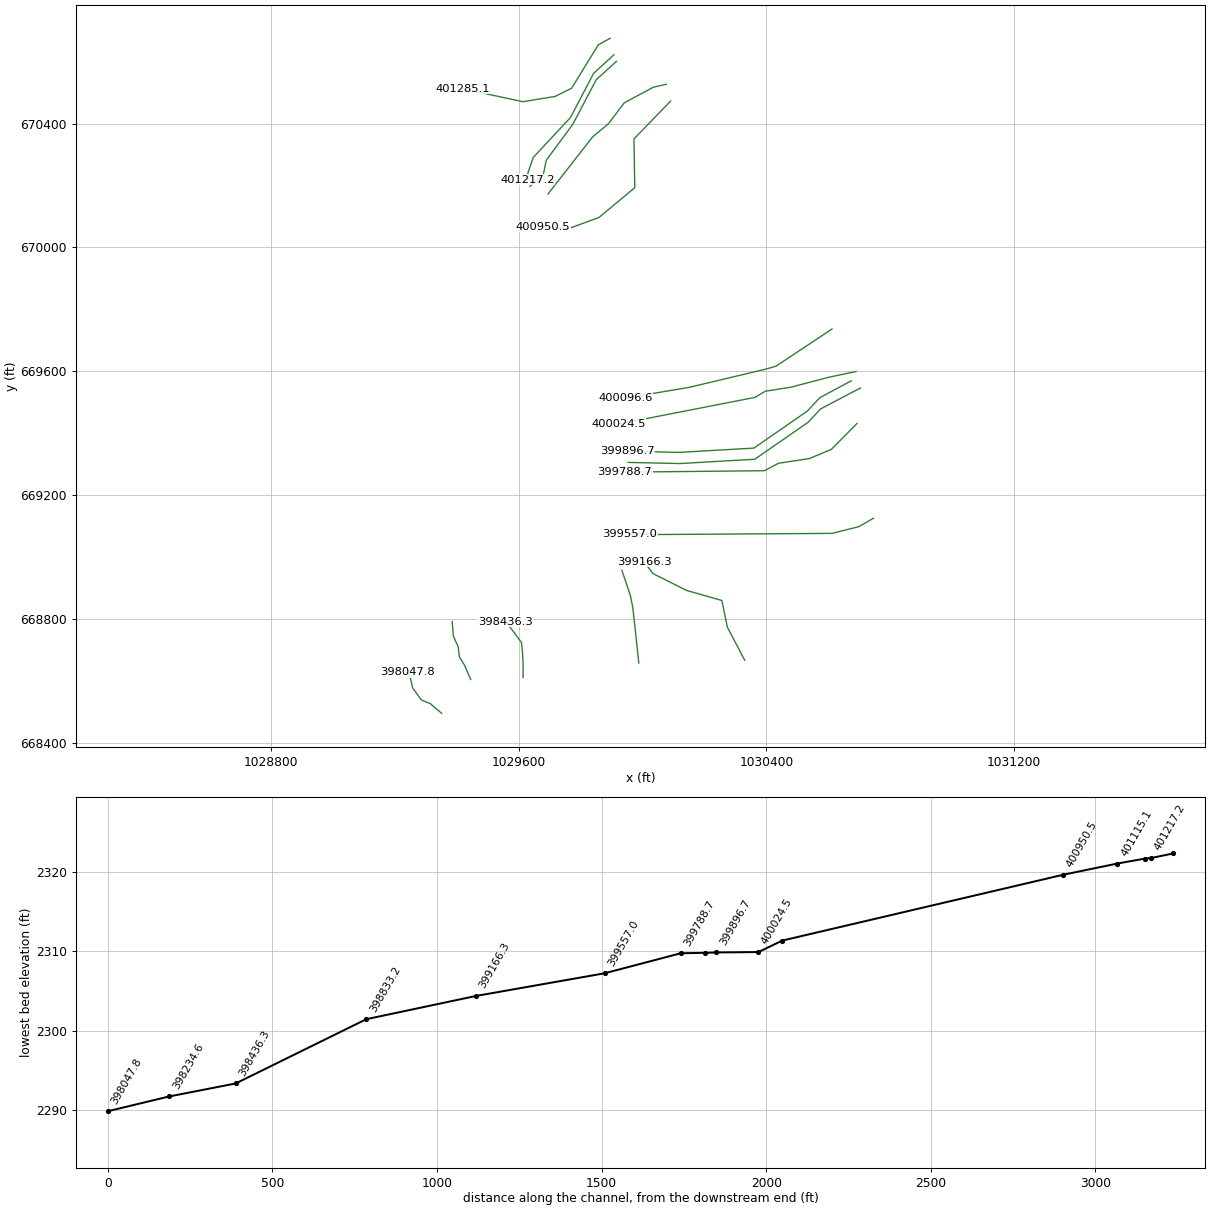
HEC-RAS study lds_broad_rvr.prj: Upper_Broad 3-06-07

--- lds_broad_rvr.g05 (geometry) --- (continued)

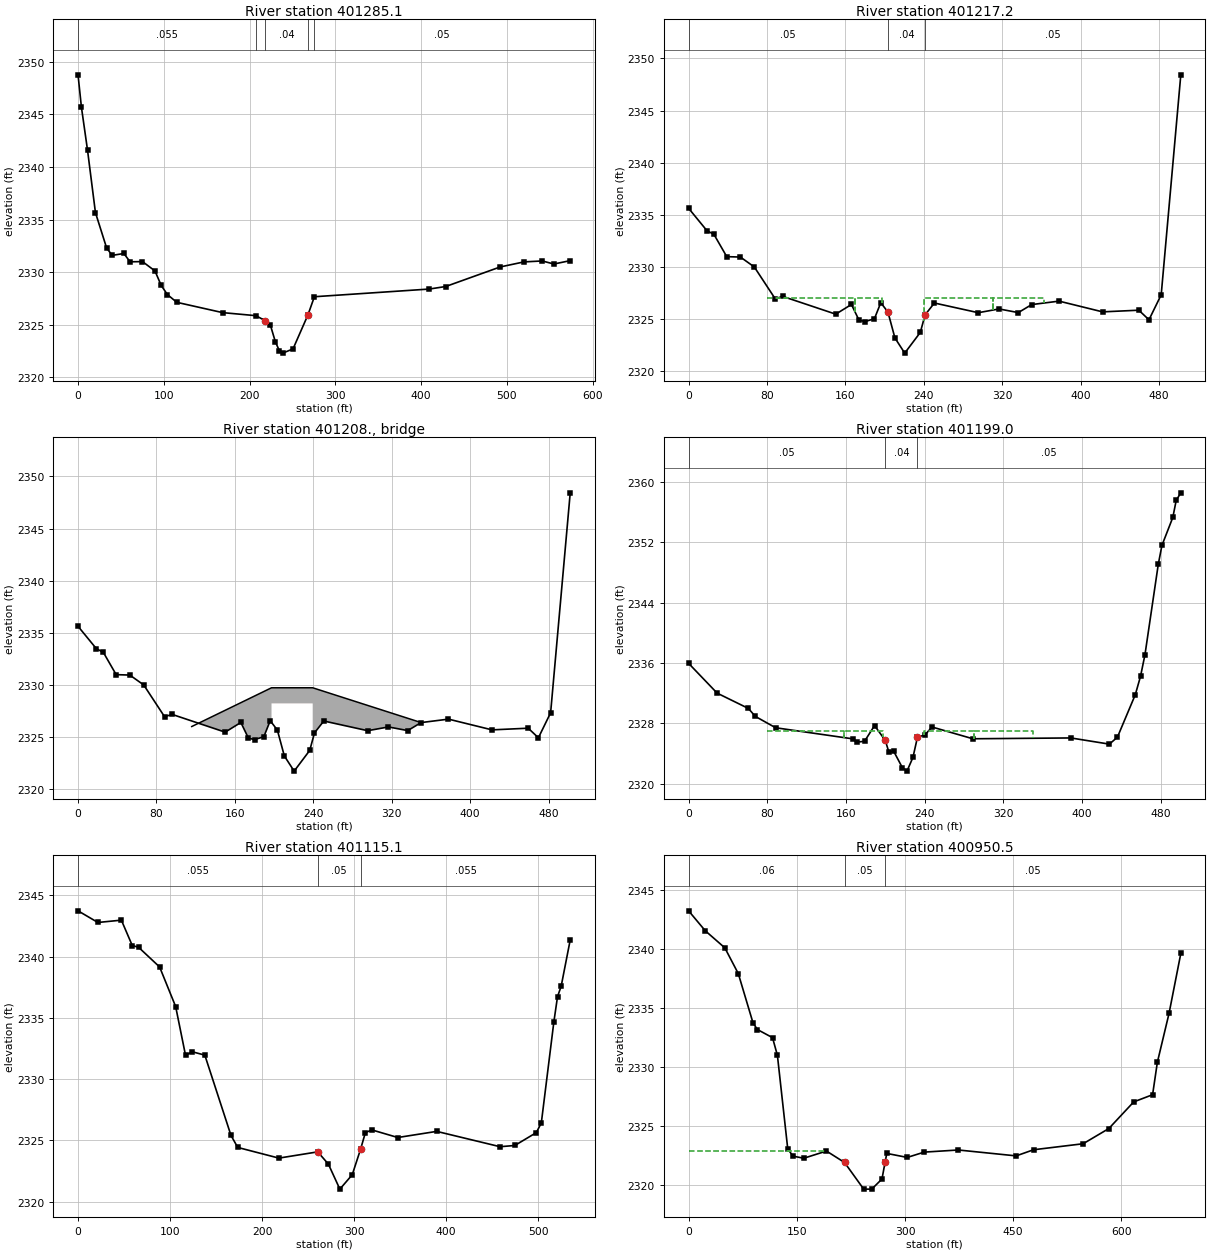
Type RM Length L Ch R = 1 ,401285.1,54.56,67.89,298.61
XS GIS Cut Line= 6
 1029894.8989591   670675.608271 1029856.9963078  670654.7618068
 1029770.7677731  670514.5220031 1029717.7040431   670487.990123
 1029613.4717521   670470.933936 1029419.2206492  670512.6268645
#Sta/Elev= 30
       0 2348.75    3.95 2345.68   11.09 2341.58   20.29 2335.66   33.31  2332.3
   39.79 2331.59   53.44 2331.77   60.66 2330.98   75.14    2331   89.71 2330.11
   96.97 2328.73  104.15 2327.87  115.09 2327.13  168.52 2326.15  207.31 2325.86
  217.85  2325.4  224.34 2324.93  230.06 2323.37  234.68 2322.53  238.55  2322.3
  250.61  2322.7  268.09 2325.95  275.51 2327.66  409.44 2328.39  428.54 2328.63
  492.09 2330.49  519.81 2330.97  541.12 2331.06  554.72 2330.77  573.74 2331.09
#Mann= 5 ,-1 , 0
       0    .055       0  207.31     .08       0  217.85     .04       0
  268.09     .08       0  275.51     .05       0
Bank Sta=217.85,268.09
Exp/Cntr=0.5,0.3

Type RM Length L Ch R = 1 ,401217.2,21.84,18.22,35.17
XS GIS Cut Line= 6
 1029907.5542124  670622.6991196   1029842.04429  670562.7141323
 1029767.0630634  670419.8551497 1029647.0930888  670291.2031386
 1029629.7290159  670241.4787233   1029628.15045  670218.5897154
#Sta/Elev= 30
       0 2335.62   18.72 2333.47   25.82 2333.12    38.9 2330.98   52.85 2330.94
   67.02 2329.99   88.23 2326.95   96.11 2327.16   150.1 2325.46  166.09 2326.39
  173.84 2324.88  180.05 2324.75  189.54 2325.02  196.04 2326.56  203.33 2325.66
  210.44 2323.18  220.45 2321.72  236.36 2323.71   241.2 2325.39   250.7 2326.53
  295.47  2325.6  316.69 2325.96  336.31 2325.61  349.97 2326.38  377.89 2326.71
   422.3 2325.68  459.22 2325.84   469.6 2324.92  482.07 2327.32  502.07 2348.43
#Mann= 3 , 0 , 0
       0     .05       0  203.33     .04       0   241.2     .05       0
#XS Ineff= 4 ,-1
      80     170    2327     170  197.23    2327  239.63     310    2327
     310  363.01    2327
Permanent Ineff=
       F       F       F       F
Bank Sta=203.33,241.2
Exp/Cntr=0.5,0.3

Type RM Length L Ch R = 3 ,401208. ,,,
BEGIN DESCRIPTION:
STR_160
END DESCRIPTION:
Bridge Culvert--1,0,-1,-1, 0
Deck Dist Width WeirC Skew NumUp NumDn MinLoCord MaxHiCord MaxSubmerge Is_Ogee
0.2,18,2.6,0, 4, 4, , , 0.95, 0, 0,0,,
     116  197.37  239.37     350
    2326 2329.72 2329.72 2326.38
         2328.22 2328.22
     116  197.37  239.37     351
    2326 2329.72 2329.722325.916
         2328.22 2328.22
BR Coef=-1 , 1 , 0 ,, 0 ,,,,-1,2,0,
WSPro=,,,, 1 ,,,, 0 ,,,, 0 ,,,,-1 ,-1 ,-1 , 0 , 0 , 0 , 0 , 0
BC Design=,, 0 ,, 0 ,,,,,,

Type RM Length L Ch R = 1 ,401199.0,129.67,83.87,75.83
XS GIS Cut Line= 6
 1029915.4469811  670601.3886776 1029849.9370587  670541.4036902
 1029774.9558321  670398.5447076 1029688.9247052  670281.7318041
 1029679.4534009  670235.9537883 1029636.0432187  670197.2792733
#Sta/Elev= 30
       0 2335.94   29.03 2331.99   60.82 2329.96   67.81 2328.91   88.53  2327.4
  166.97 2325.93  171.09 2325.49  178.94 2325.61  189.11 2327.69     2002325.728
  203.62  2324.2  208.64 2324.27  217.48 2322.09  222.07 2321.65  228.17 2323.47
  232.77 2326.16  240.27 2326.44  247.55  2327.5  289.13 2325.94  388.75 2326.05
  427.93 2325.23  436.11 2326.15  454.28 2331.78  459.61 2334.22  464.13 2337.09
  477.68 2349.08  481.39 2351.58  492.46 2355.29   495.9 2357.55  500.58 2358.55
#Mann= 3 , 0 , 0
       0     .05       0     200     .04       0  232.77     .05       0
#XS Ineff= 4 ,-1
      80  158.12    2327  158.12  197.23    2327  239.56     290    2327
     290     350    2327
Permanent Ineff=
       F       F       F       F
Bank Sta=200,232.77
Exp/Cntr=0.5,0.3

Type RM Length L Ch R = 1 ,401115.1,95.65,164.6,179.63
XS GIS Cut Line= 6
 1030076.4593346  670527.1966885 1030034.6276879  670517.7253842
 1029940.7038226  670467.2117011 1029889.4008717  670399.3339754
 1029838.8871886   670357.502359 1029694.4496402  670172.8116995
#Sta/Elev= 30
       0 2343.73   21.61 2342.78    47.1 2342.97   58.93  2340.9   65.74 2340.76
   88.66 2339.15  106.09 2335.92  116.85 2331.93  123.82 2332.24  137.78 2331.96
  166.21 2325.41  173.55 2324.43  218.23 2323.56  260.49 2324.07  272.03 2323.07
  284.51 2321.03  297.94  2322.2  307.13 2324.31  312.24 2325.64  319.32 2325.86
  347.46 2325.24  389.74 2325.74   458.6 2324.49  474.63 2324.59     498 2325.64
  503.42 2326.43  517.03 2334.66  521.03 2336.73  524.99 2337.58  534.83 2341.36
#Mann= 3 , 0 , 0
       0    .055       0  260.49     .05       0  307.13    .055       0
Bank Sta=260.49,307.13
Exp/Cntr=0.3,0.1

Type RM Length L Ch R = 1 ,400950.5,923.7,853.9,638.23
XS GIS Cut Line= 6
 1030090.5978096  670473.0441891 1029972.1082418  670350.6483571
 1029974.7124077   670193.096269 1029858.8269756   670096.742097
 1029758.5665697  670060.2837731 1029677.8373936  670066.7941729
#Sta/Elev= 30
       0 2343.23   23.08 2341.54   50.22 2340.09   68.92  2337.9   89.26 2333.73
   95.37 2333.16  116.35 2332.47  123.11 2330.97  137.48 2323.02  144.81 2322.42
  159.65 2322.24  191.15 2322.85  216.21 2321.88  242.76 2319.62  253.93 2319.62
   268.1 2320.48  272.53 2321.94  274.75 2322.65  303.13 2322.31  326.65 2322.76
     374 2322.94  454.13 2322.44  478.25 2322.96  546.99 2323.47  582.64 2324.76
  617.13 2327.02   643.3 2327.63  649.91 2330.38  666.11 2334.53  682.42 2339.61
#Mann= 3 , 0 , 0
       0     .06       0  216.21     .05       0  272.53     .05       0
#XS Ineff= 2 , 0
       0  189.61 2322.85  274.75       0 2322.65
Permanent Ineff=
       F       F
Bank Sta=216.21,272.53
Exp/Cntr=0.3,0.1

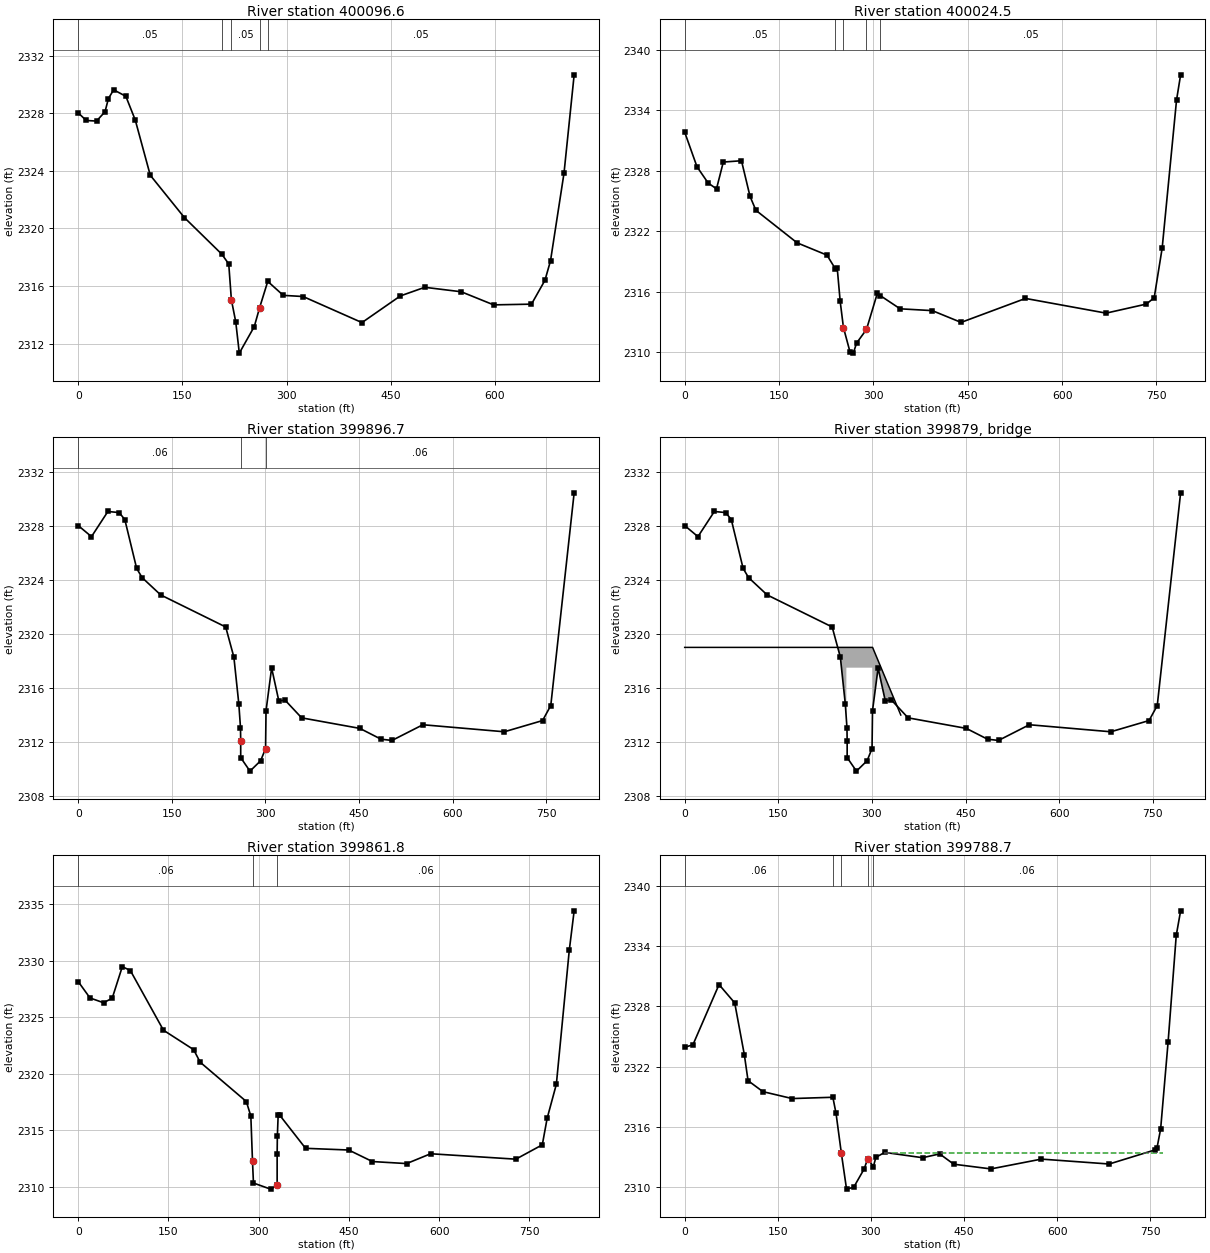
Type RM Length L Ch R = 1 ,400096.6,104.53,72.1,72.33
XS GIS Cut Line= 5
 1030611.8845439  669736.6379434  1030430.351016  669616.2733348
 1030390.8872333  669605.4207817 1030150.1579859  669548.1982619
 1029944.9461824  669513.6674331
#Sta/Elev= 30
       0 2328.02   11.59 2327.49   26.35 2327.45   38.62  2328.1   43.48 2329.01
   51.01 2329.62    68.6 2329.17   82.17 2327.52  103.76 2323.69  152.91 2320.75
  206.78 2318.21   216.8 2317.53   220.6 2315.04  226.85 2313.52  232.02 2311.34
  253.55 2313.18  261.29  2314.5  272.98 2316.32  295.35 2315.35  323.84 2315.27
  408.66 2313.46  463.92 2315.31  499.13 2315.91  551.63  2315.6  598.34 2314.69
  652.83 2314.74  672.24  2316.4  680.22 2317.75  699.65 2323.83  714.27 2330.66
#Mann= 5 ,-1 , 0
       0     .05       0  206.78     .08       0   220.6     .05       0
  261.29     .08       0  272.98     .05       0
#XS Ineff= 2 , 0
       0                  272.98       0 2316.32
Permanent Ineff=
       F       F
Bank Sta=220.6,261.29
Exp/Cntr=0.3,0.1

Type RM Length L Ch R = 1 ,400024.5,78.97,127.84,139.79
XS GIS Cut Line= 6
 1030689.8255852  669599.5012128 1030601.0319907  669580.7559213
 1030479.4793641  669548.8210861 1030396.6976559  669535.8125146
 1030362.4024027  669515.7084028 1029922.2544914  669429.8068531
#Sta/Elev= 30
       0 2331.84   19.59  2328.4   37.28 2326.79   50.59 2326.21   61.41 2328.87
   90.28    2329  103.91 2325.46  113.23 2324.08  178.76 2320.85  226.23 2319.63
  239.42 2318.28  242.43  2318.4  247.23 2315.03  252.41 2312.44   262.7 2310.05
  268.11  2309.9   273.3  2310.9  289.02 2312.25  306.24 2315.83  310.99 2315.61
  342.51  2314.3  393.62 2314.12  439.44 2312.95  541.81 2315.33  669.96 2313.87
  733.94 2314.77  746.43  2315.4  759.13 2320.34  781.99 2335.04  788.44 2337.53
#Mann= 5 ,-1 , 0
       0     .05       0  239.42     .08       0  252.41     .05       0
  289.02     .08       0  310.99     .05       0
Bank Sta=252.41,289.02
Exp/Cntr=0.5,0.3

Type RM Length L Ch R = 1 ,399896.7,32.87,34.9,37.88
XS GIS Cut Line= 6
 1030674.0708909  669569.4409037 1030572.6145064  669514.8773955
 1030532.0163101  669471.4793205 1030359.5936554  669352.0816224
  1030118.186133   669338.207629 1029950.7732523  669341.9073747
#Sta/Elev= 30
       0 2328.01   21.25 2327.19   47.52 2329.05   65.68 2328.97   74.67 2328.45
   93.61 2324.84  102.37 2324.16  132.12 2322.88  236.26 2320.51  249.35 2318.28
  257.25 2314.83  259.94 2313.07  260.26  2312.1  260.26 2310.85  275.15 2309.85
  292.24 2310.62  300.11 2311.52  300.87 2314.32  309.82 2317.48  321.39 2315.03
  331.12 2315.11  357.88 2313.79  451.14 2313.01  485.15 2312.21  502.69 2312.12
  552.11 2313.28  682.62 2312.76  743.84 2313.59  756.97  2314.7  794.41 2330.43
#Mann= 3 , 0 , 0
       0     .06       0  260.26     .05       0  300.11     .06       0
Bank Sta=260.26,300.11
Exp/Cntr=0.5,0.3

Type RM Length L Ch R = 3 ,399879  ,,,
BEGIN DESCRIPTION:
STR_160
END DESCRIPTION:
Bridge Culvert--1,0,-1,-1, 0
Deck Dist Width WeirC Skew NumUp NumDn MinLoCord MaxHiCord MaxSubmerge Is_Ogee
8.45,12,2.6,0, 4, 4, , , 0.95, 0, 0,0,,
       0     259     301  346.15
    2319    2319    2319    2314
          2317.5  2317.5
       0     288     330     368
    2319    2319    2319 2313.76
          2317.5  2317.5
BR Coef=-1 , 1 , 0 ,, 0 ,,,0.8,-1,2,0,
WSPro=,,,, 1 ,,,, 0 ,,,, 0 ,,,,-1 ,-1 ,-1 , 0 , 0 , 0 , 0 , 0
BC Design=,, 0 ,, 0 ,,,,,,

Type RM Length L Ch R = 1 ,399861.8,118.88,73.07,35.29
XS GIS Cut Line= 6
 1030703.6687356  669546.3175611  1030575.389293  669478.8050185
 1030534.7910967  669435.4069435  1030362.368442  669316.0092455
 1030120.9609195  669302.1352521 1029953.5480389  669305.8349978
#Sta/Elev= 30
       0 2328.16   19.63 2326.71   42.09 2326.29   56.54 2326.69    73.3 2329.48
   86.68 2329.14   141.7 2323.86  191.89 2322.14  202.74 2321.03  279.51 2317.55
  287.02 2316.26  289.78 2312.25  291.36 2310.34  319.83  2309.8  330.74 2310.13
  330.74 2312.91   331.1  2314.5  332.43 2316.32  334.73 2316.36  378.01 2313.41
  449.72 2313.26   489.1 2312.24  546.06 2312.06  585.95 2312.93  727.64 2312.45
   771.6 2313.72  779.64 2316.06  794.97 2319.08  816.45 2330.93  824.56 2334.42
#Mann= 3 , 0 , 0
       0     .06       0  289.78     .05       0  330.74     .06       0
Bank Sta=289.78,330.74
Exp/Cntr=0.5,0.3

Type RM Length L Ch R = 1 ,399788.7,267.32,231.74,206.49
XS GIS Cut Line= 6
 1030692.5695287  669431.6258677 1030609.5648666  669347.7798467
 1030538.6091297  669318.2149638 1030439.1379007  669303.0601809
 1030393.8161747  669279.0119397 1029942.4488623  669274.3872651
#Sta/Elev= 30
       0 2323.92   13.34 2324.18   55.35 2330.19    80.6 2328.36   96.07  2323.2
   102.1 2320.59  126.04 2319.49  173.16  2318.8  238.74 2318.93   243.9 2317.31
   252.3 2313.39   260.8 2309.75  272.37 2309.94  289.36 2311.79  294.77 2312.78
  304.11 2312.01  307.96 2312.92  322.18 2313.42  383.28 2312.89  410.85 2313.27
  433.51 2312.24  493.38 2311.77  574.73 2312.75  683.95 2312.26  757.83 2313.67
  760.98 2313.87  766.83 2315.75  778.88 2324.46  791.98  2335.1  799.04 2337.56
#Mann= 5 ,-1 , 0
       0     .06       0  238.74     .08       0   252.3     .05       0
  294.77     .08       0  304.11     .06       0
#XS Ineff= 2 ,-1
  294.77     310 2312.78  321.19     770  2313.4
Permanent Ineff=
       F       F
Bank Sta=252.3,294.77
Exp/Cntr=0.3,0.1

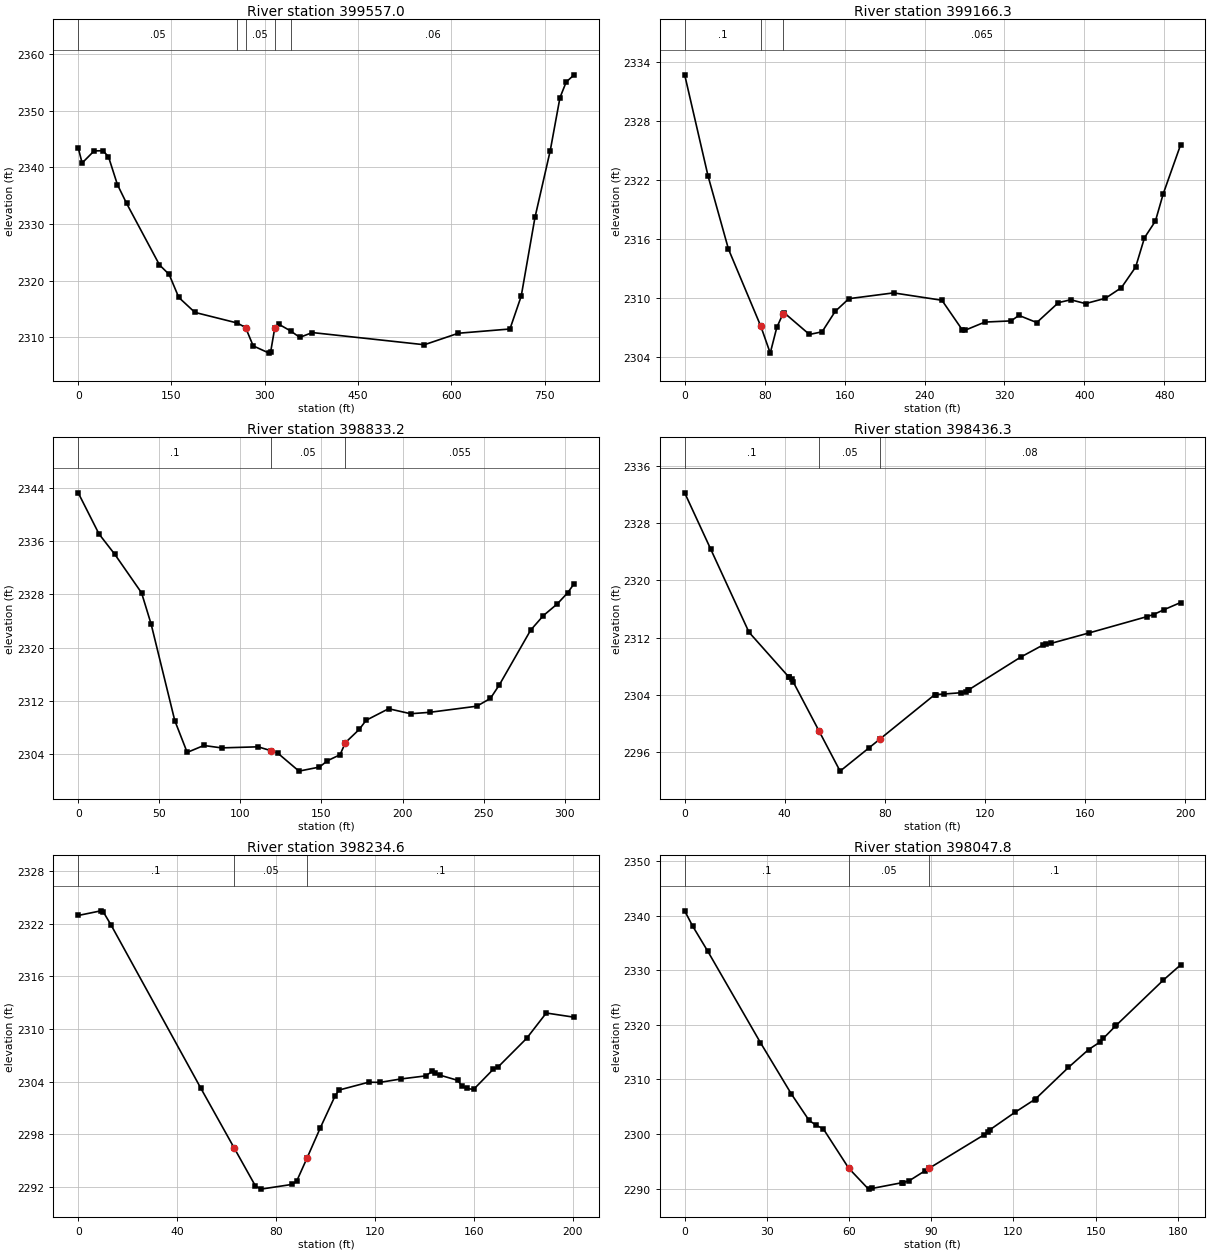
Type RM Length L Ch R = 1 ,399557.0,595.15,390.67,271.72
XS GIS Cut Line= 6
  1030745.558073  669125.3501948 1030698.5888306  669098.2525457
 1030611.8763715  669076.5744385 1030055.4713373  669072.9614105
 1029959.7263083  669074.7679245 1029957.9198245  669074.7679245
#Sta/Elev= 30
       0 2343.47    6.27 2340.79   25.57 2342.93   39.82 2342.96   48.68  2341.9
   63.04 2336.98   77.83 2333.66  130.72  2322.8  146.23 2321.12  161.74 2317.06
  187.66 2314.42  255.72 2312.55  269.16 2311.75  281.41 2308.51  306.98 2307.23
   309.5 2307.45  316.18 2311.73  322.94 2312.31  341.54 2311.15  356.27 2310.01
  376.52 2310.86  556.68 2308.71  611.29 2310.74  694.33 2311.49  712.45 2317.29
  734.59 2331.19  759.15 2342.99  774.75 2352.32  784.77 2355.09  797.59 2356.36
#Mann= 5 ,-1 , 0
       0     .05       0  255.72     .08       0  269.16     .05       0
  316.18     .08       0  341.54     .06       0
#XS Ineff= 2 , 0
       0                  322.94       0 2312.31
Permanent Ineff=
       F       F
Bank Sta=269.16,316.18
Exp/Cntr=0.3,0.1

Type RM Length L Ch R = 1 ,399166.3,359.02,333.12,106.53
XS GIS Cut Line= 6
 1030330.0608264  668666.4967036 1030274.0590141  668773.0807862
 1030255.9939349  668859.7932756 1030142.1837964  668892.3104364
   1030033.79323  668946.5057347 1030004.8890669  668984.4424374
#Sta/Elev= 30
       0  2332.7   23.44 2322.38   43.82 2314.96    76.2 2307.11    85.6 2304.38
   92.16 2306.99   98.05 2308.32   99.61 2308.48  124.82 2306.28  137.49 2306.55
  150.62 2308.63  164.28 2309.92  208.98 2310.51  257.38 2309.76  277.56 2306.78
   280.8 2306.72  300.39 2307.54   326.6 2307.66  334.43 2308.22  352.28 2307.49
  373.99 2309.52   386.3 2309.81  401.09 2309.42  420.98 2309.96  436.97 2311.04
  451.23 2313.14  460.07 2316.12  471.01 2317.82  478.81 2320.59  496.22 2325.58
#Mann= 3 , 0 , 0
       0      .1       0    76.2     .05       0   98.05    .065       0
#XS Ineff= 2 ,-1
  208.98     450 2310.15   99.61     150 2308.48
Permanent Ineff=
       F       F
Bank Sta=76.2,98.05
Exp/Cntr=0.3,0.1

Type RM Length L Ch R = 1 ,398833.2,384.34,396.87,413.89
XS GIS Cut Line= 6
 1029987.7332377  668657.9400068 1029979.9207397  668732.1587831
 1029972.1082418   668803.773363 1029968.2019776   668837.627521
 1029960.3894796  668876.6900109 1029933.0457216   668957.419187
#Sta/Elev= 30
       0 2343.25   12.85 2337.06   22.64 2333.99   39.07 2328.23   44.96 2323.54
   59.53 2309.06   67.19 2304.27   77.46 2305.31   88.36 2304.95  110.94 2305.11
  118.58 2304.55  122.92 2304.19  136.13 2301.46  148.77 2302.07  153.67 2303.02
  161.46 2303.92  164.76 2305.74  173.28 2307.72  177.51 2309.09  191.42 2310.83
  204.97 2310.08  216.74 2310.29   245.8 2311.21  254.19 2312.38  259.69 2314.41
  279.02 2322.64  286.86 2324.82  295.42 2326.57  301.82 2328.24  305.82 2329.61
#Mann= 3 , 0 , 0
       0      .1       0  118.58     .05       0  164.76    .055       0
#XS Ineff= 2 , 0
       0   77.46 2305.31               0
Permanent Ineff=
       F       F
Bank Sta=118.58,164.76
Exp/Cntr=0.3,0.1

Type RM Length L Ch R = 1 ,398436.3,190.06,201.68,204.23
XS GIS Cut Line= 6
 1029614.0353116  668611.0650189 1029614.0353116  668652.7316748
 1029612.7332437   668683.981697 1029608.8269796  668724.3462548
 1029561.9519917  668786.8462689 1029556.7436597  668790.7525331
#Sta/Elev= 27
       0 2332.22   10.36 2324.39   25.68 2312.77   41.67 2306.49   41.77 2306.45
   42.88 2306.21   43.45 2305.77    53.6 2299.03   62.09 2293.38   73.65 2296.63
   77.95 2297.84   99.93 2304.06  100.41 2304.07  103.58 2304.14  110.29 2304.32
  112.29 2304.37  113.34 2304.71   113.5 2304.74  134.23 2309.29  143.09 2310.97
  144.23 2311.06  146.48 2311.22  161.48 2312.66  184.56 2314.93   187.3 2315.23
  191.62 2315.93  198.13 2316.91
#Mann= 3 , 0 , 0
       0      .1       0    53.6     .05       0   77.95     .08       0
Bank Sta=53.6,77.95
Exp/Cntr=0.3,0.1

Type RM Length L Ch R = 1 ,398234.6,170.29,186.84,205.62
XS GIS Cut Line= 6
 1029444.7644917  668604.5545888 1029425.2332316  668650.1275088
 1029408.3061375  668677.4712669 1029404.3999037   668710.023357
 1029388.7749077   668745.179613 1029384.8686436  668792.0546009
#Sta/Elev= 30
       0 2322.95    9.17 2323.48   10.09 2323.38   13.26 2321.88   49.58 2303.27
   63.11 2296.44   71.72  2292.1   73.96 2291.75   86.56 2292.29   88.36 2292.64
   92.51 2295.25   97.99 2298.76     104 2302.42  105.57 2303.05  117.52 2303.94
  122.05 2303.92  130.55 2304.31  140.56 2304.66   143.3 2305.19  144.18    2305
  146.53 2304.73  153.57 2304.15  155.32 2303.48   157.4 2303.23  159.94 2303.11
  167.89  2305.4     170 2305.71  181.43 2308.94  189.38 2311.83  200.66 2311.35
#Mann= 3 , 0 , 0
       0      .1       0   63.11     .05       0   92.51      .1       0
Bank Sta=63.11,92.51
Exp/Cntr=0.3,0.1

Type RM Length L Ch R = 1 ,398047.8,298.9,431.88,504.87
XS GIS Cut Line= 6
 1029351.0144857   668495.179617 1029314.5561617   668526.429609
 1029285.9103055  668538.1483408 1029257.2644796   668577.210861
 1029250.7540495  668605.8566869 1029241.6394836   668627.992113
#Sta/Elev= 30
       0 2340.88    2.88 2338.11    8.42 2333.48   27.67 2316.72   38.92 2307.34
   45.39  2302.5   48.02 2301.58    50.6 2300.94    59.9 2293.71   67.11 2289.89
   68.45 2290.02   79.26 2291.06   79.72  2291.1   81.89  2291.4    87.6 2293.21
   89.16 2293.69  109.25 2299.83  110.74 2300.43  111.54 2300.81  120.59 2303.97
  127.72 2306.29  128.13 2306.44  140.09 2312.19  147.44 2315.46  151.47 2316.79
  152.84 2317.52   157.1 2319.69   157.5 2319.89  174.67 2328.16  181.04 2330.97
#Mann= 3 , 0 , 0
       0      .1       0    59.9     .05       0   89.16      .1       0
Bank Sta=59.9,89.16
Exp/Cntr=0.3,0.1