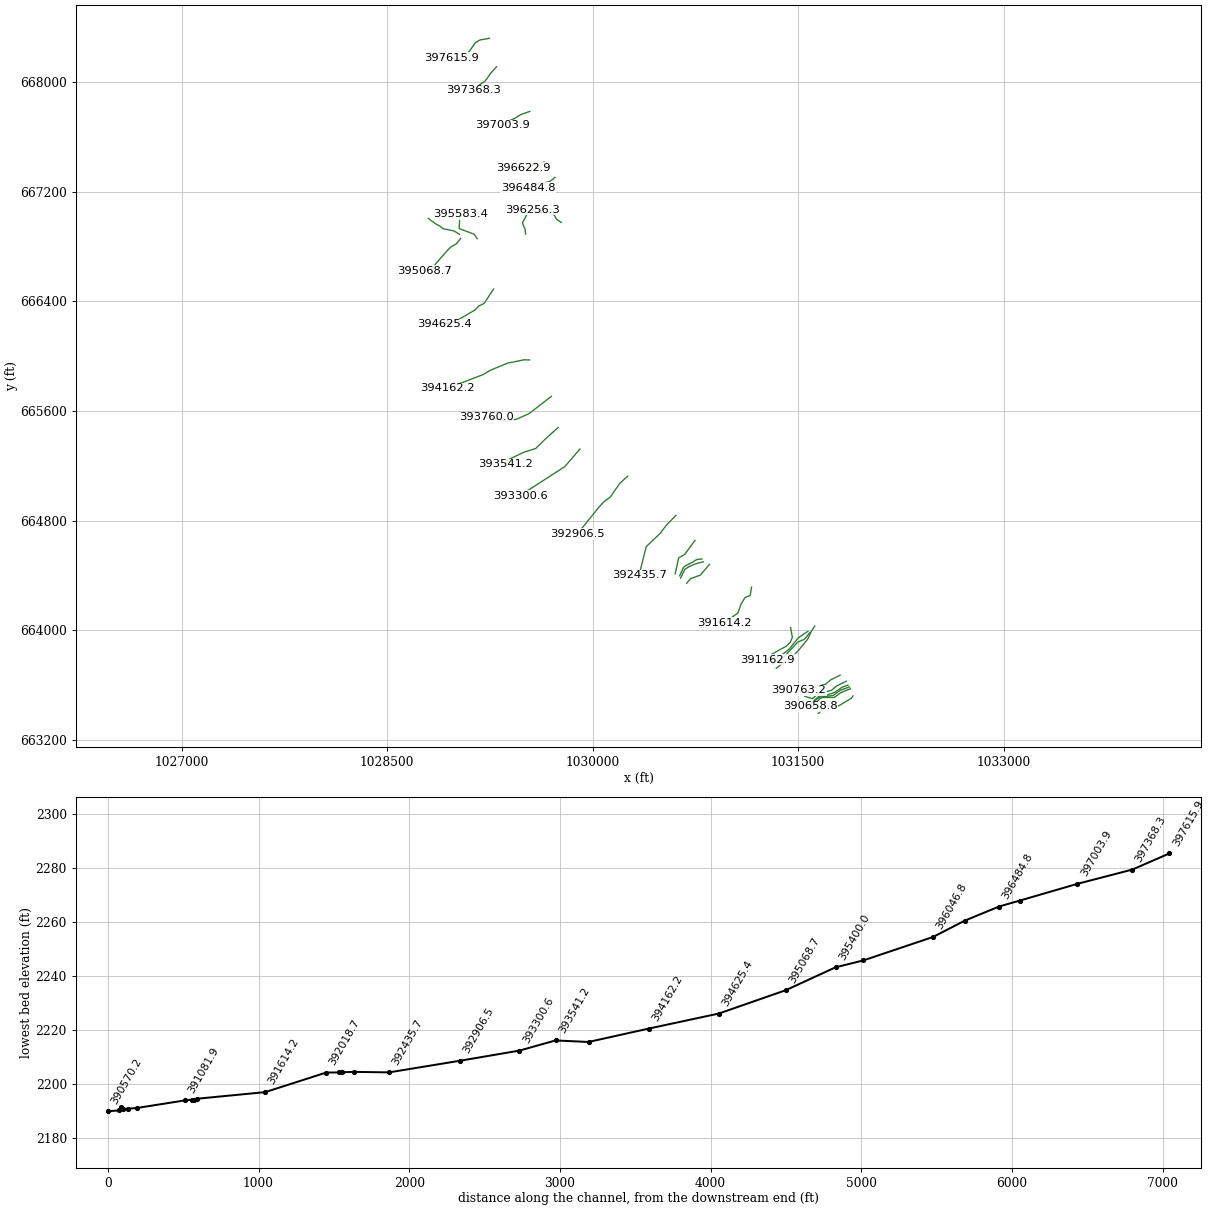
HEC-RAS study lds_broad_rvr.prj: Upper_Broad 3-06-07

--- lds_broad_rvr.g05 (geometry) --- (continued)

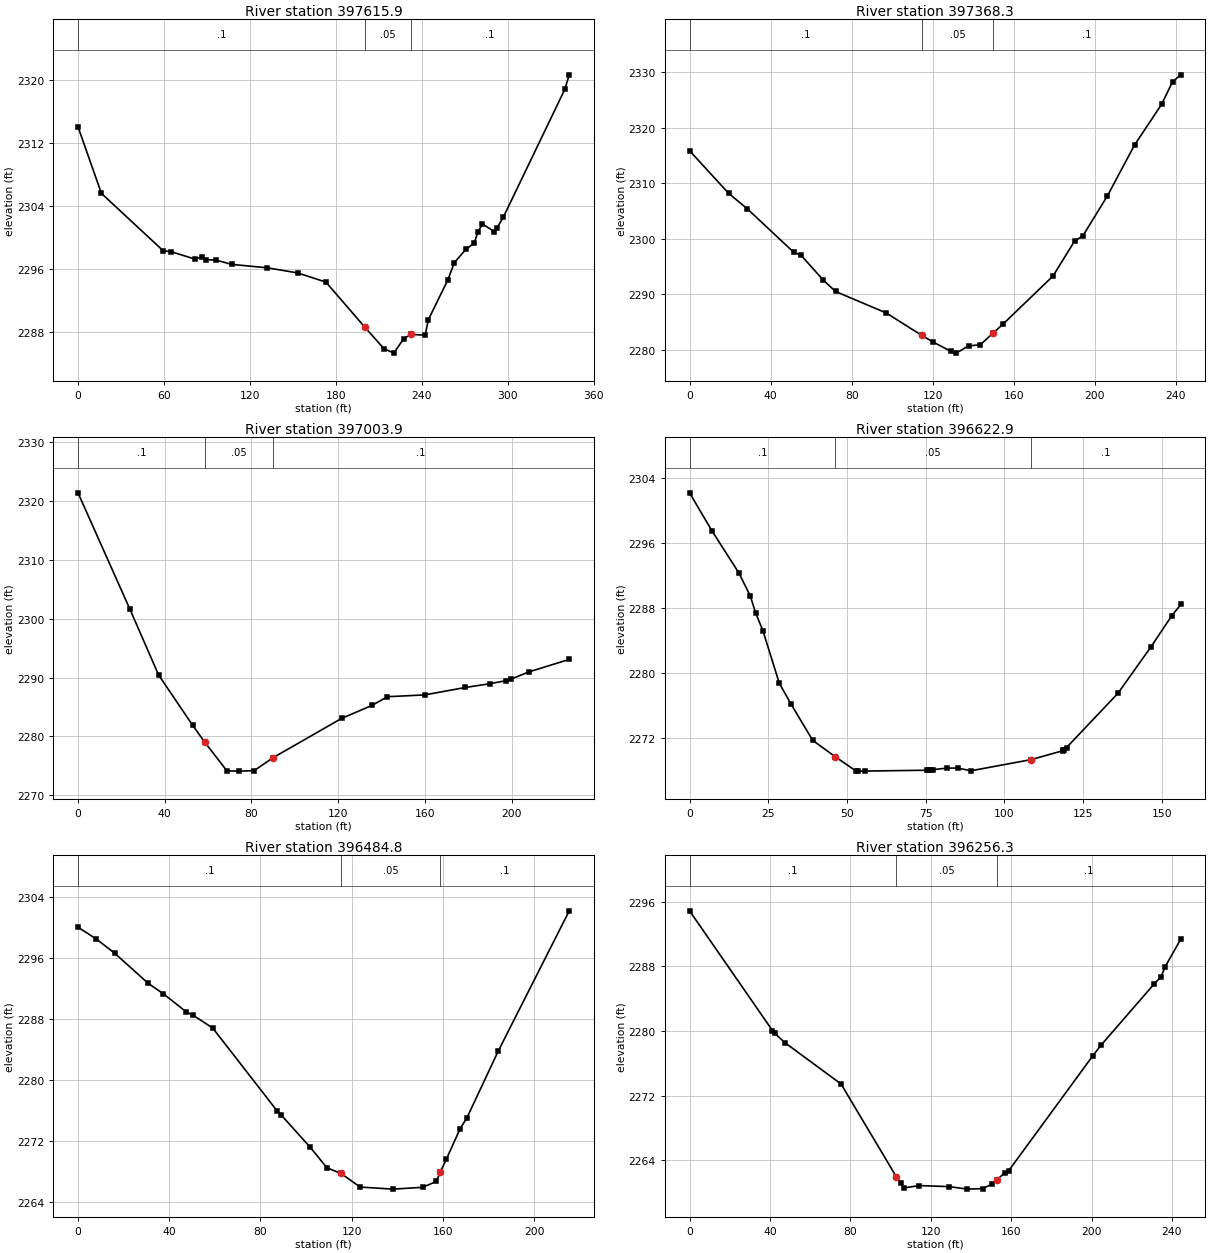
Type RM Length L Ch R = 1 ,397615.9,264.65,247.61,256.84
XS GIS Cut Line= 6
  1029246.489927  668320.3687281 1029179.2587859  668308.6763597
 1029145.6432001  668289.6762421 1029103.2583759  668229.7528501
 1029033.1041351  668161.0601591 1028973.1807431   668177.137177
#Sta/Elev= 30
       0 2314.11   16.34 2305.65   59.51 2298.35   64.71 2298.26   81.45 2297.31
   86.38 2297.53   89.56 2297.22   96.33 2297.18  107.24 2296.63  131.95  2296.2
  153.24 2295.55  173.05 2294.38  200.23 2288.65  213.59 2285.92  220.46 2285.36
  227.37 2287.21  232.55 2287.74  242.34 2287.64  244.55 2289.61  258.17 2294.66
  262.68 2296.85  270.82 2298.55  276.56 2299.33   279.1 2300.72  282.28 2301.76
  290.65 2300.79   292.4 2301.24  296.96 2302.65  339.78 2318.85  342.91  2320.7
#Mann= 3 , 0 , 0
       0      .1       0  200.23     .05       0  232.55      .1       0
Bank Sta=200.23,232.55
Exp/Cntr=0.3,0.1

Type RM Length L Ch R = 1 ,397368.3,386.99,364.43,372.37
XS GIS Cut Line= 6
 1029299.1056001  668112.8291355 1029255.2591958  668064.5980817
 1029227.4898094  668023.6748073 1029212.8743413  668007.5977893
  1029177.797236  667982.7515026  1029131.027732  667940.3666482
#Sta/Elev= 24
       0 2315.86   19.34 2308.16   28.57 2305.36   51.36 2297.56   54.99 2297.02
   66.06 2292.51   72.04 2290.48   97.15 2286.59  114.64 2282.55  120.09 2281.38
  128.85  2279.7  131.65 2279.36  137.68 2280.67  143.47 2280.86  149.85 2282.99
  154.84 2284.64  179.35 2293.26  189.99 2299.54  194.11 2300.52  206.15 2307.67
  219.63  2316.9  233.07 2324.29  238.36 2328.31  242.47 2329.55
#Mann= 3 , 0 , 0
       0      .1       0  114.64     .05       0  149.85      .1       0
Bank Sta=114.64,149.85
Exp/Cntr=0.3,0.1

Type RM Length L Ch R = 1 ,397003.9,393.24,380.94,362.12
XS GIS Cut Line= 6
  1029541.722298  667786.9042784 1029474.4911569  667763.5195113
 1029432.1063024  667735.7501552 1029399.9522968  667722.5962369
 1029369.2598107  667699.2114698 1029341.4904243   667684.596032
#Sta/Elev= 19
       0 2321.39   23.97 2301.59   37.17 2290.44   52.82 2281.91   58.48    2279
   68.69 2274.13   74.39 2274.09   81.24 2274.17   89.95 2276.37  121.53 2283.04
  135.74 2285.29  142.73 2286.74  159.84 2287.04  178.66 2288.31  189.84 2288.94
  197.36 2289.46  199.61 2289.71  207.82 2290.94  226.56 2293.08
#Mann= 3 , 0 , 0
       0      .1       0   58.48     .05       0   89.95      .1       0
Bank Sta=58.48,89.95
Exp/Cntr=0.3,0.1

Type RM Length L Ch R = 1 ,396622.9,151.37,138.19,138.41
XS GIS Cut Line= 2
 1029647.2001163  667418.1984499 1029497.2598193  667374.8422052
#Sta/Elev= 29
       0 2302.157.070007  2297.5   15.63 2292.3219.29001 2289.4720.96001 2287.41
   23.34 2285.15   28.51 2278.73   32.14 2276.23   39.12  2271.7   46.26  2269.7
   52.86 2267.9453.49001 2267.92   55.59 2267.93   75.48 2268.03   75.63 2268.04
76.56001 2268.11   77.29  2268.1   81.94  2268.3   85.17 2268.29   89.47 2267.97
  108.45 2269.33  118.49 2270.42  118.75 2270.47  118.81 2270.47  119.76 2270.82
  136.09 2277.49  146.65 2283.24  153.21 2287.04  156.08 2288.42
#Mann= 3 , 0 , 0
       0      .1       0   46.26     .05       0  108.45      .1       0
Bank Sta=46.26,108.45
Exp/Cntr=0.3,0.1

Type RM Length L Ch R = 1 ,396484.8,246.15,228.47,211.63
XS GIS Cut Line= 6
 1029725.5608232  667305.0391334 1029691.6347788  667278.0723025
 1029648.1398765  667264.1539059  1029609.864354  667264.1539059
 1029584.6372962  667261.5442311 1029530.7035737  667229.3579901
#Sta/Elev= 23
       0 2300.05    8.04 2298.49   16.07 2296.64   30.85 2292.67    37.4 2291.33
   47.41 2288.96   50.66 2288.47   59.11 2286.82   87.34 2275.96   89.01 2275.47
  101.83  2271.2  109.18 2268.51   115.4 2267.76  123.76 2265.98  138.21 2265.71
  151.21 2265.95  157.21 2266.73  158.83 2267.92   161.6 2269.66  167.61 2273.64
  170.61 2275.08   184.3  2283.8  215.46 2302.19
#Mann= 3 , 0 , 0
       0      .1       0   115.4     .05       0  158.83      .1       0
Bank Sta=115.4,158.83
Exp/Cntr=0.3,0.1

Type RM Length L Ch R = 1 ,396256.3,262.36,209.45,124.36
XS GIS Cut Line= 6
 1029770.7955288  666977.0874418 1029736.8695147  667000.5746963
 1029721.2113451  667028.4114592 1029697.7240906  667045.8094322
 1029597.6857608   667051.028812 1029562.0199433   667068.426785
#Sta/Elev= 22
       0 2294.87   41.26 2280.06   42.35 2279.73   47.42 2278.57   75.38 2273.46
  102.87 2261.99  105.19 2261.18  106.55  2260.6  114.28  2260.9  129.16 2260.77
  138.19 2260.46  145.85 2260.52  150.59  2261.1   152.8  2261.6     157  2262.5
  158.82 2262.75  200.73 2276.98  204.66 2278.24  231.16 2285.83  234.65 2286.74
  236.67 2287.98  244.44 2291.38
#Mann= 3 , 0 , 0
       0      .1       0  102.87     .05       0   152.8      .1       0
Bank Sta=102.87,152.8
Exp/Cntr=0.3,0.1

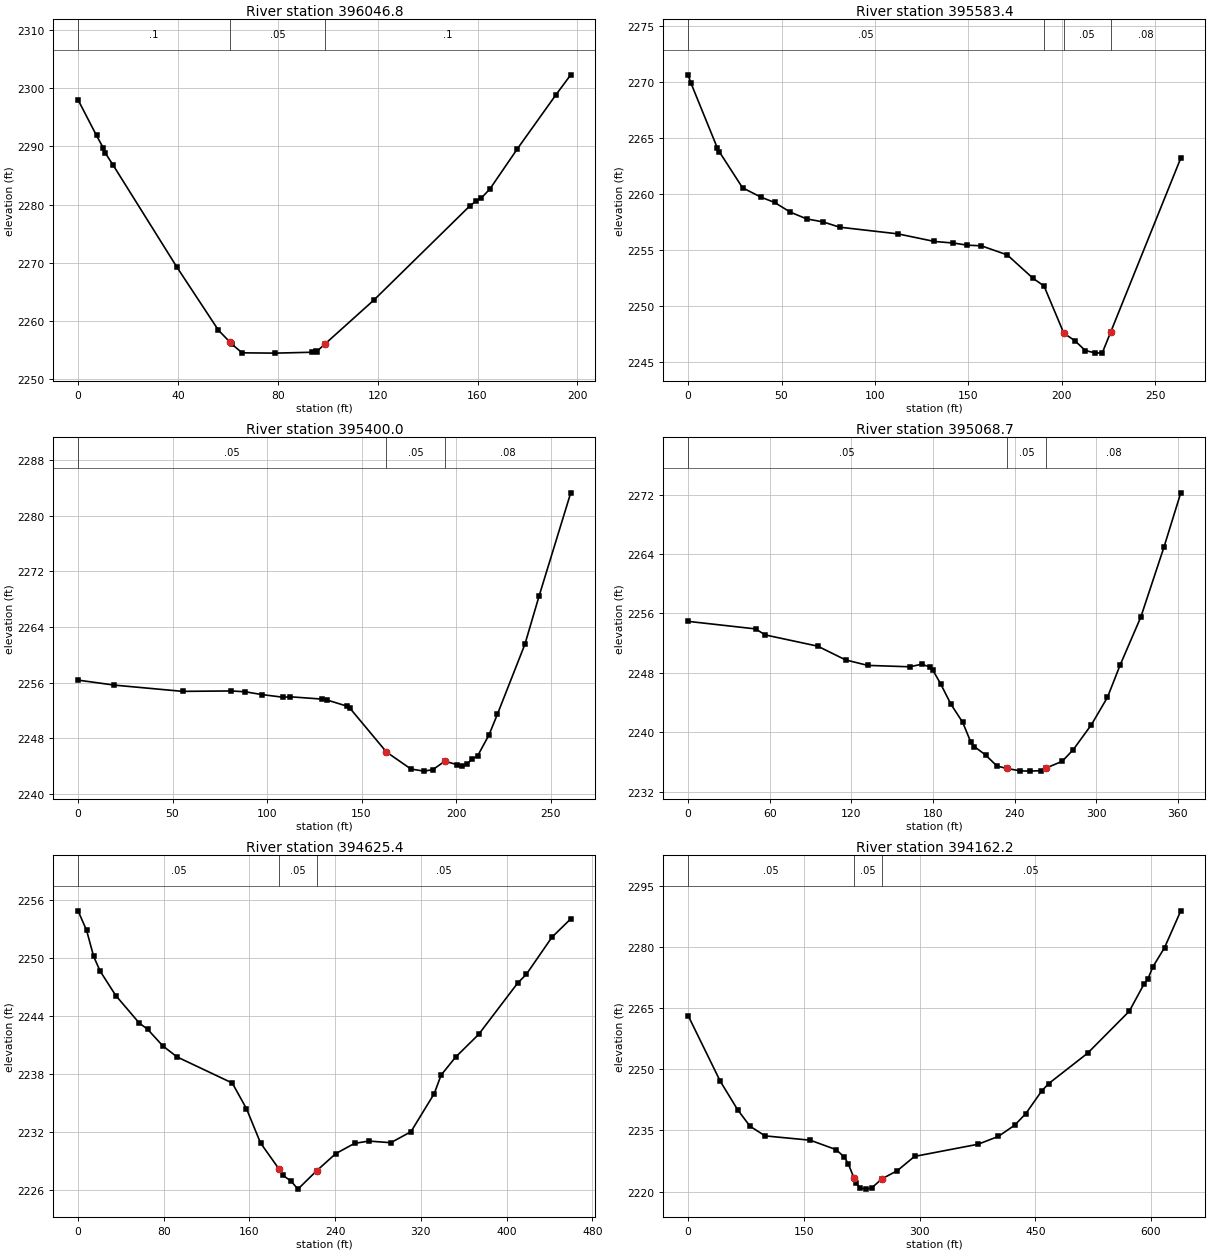
Type RM Length L Ch R = 1 ,396046.8,455.68,463.4,492.67
XS GIS Cut Line= 6
 1029511.5658276  666891.8374103 1029506.3464175  666930.9828345
 1029488.9484748  666969.2583569 1029488.9484748  666977.0874418
 1029525.4841939  667043.1997272 1029508.9561226  667071.0364598
#Sta/Elev= 23
       0    2298    7.39 2291.87   10.05 2289.77   10.79 2288.93    14.1 2286.74
   39.49  2269.3   56.22 2258.39   60.89 2256.32   61.65 2255.98   65.69  2254.5
   79.05 2254.45   93.52  2254.6   95.29 2254.77   95.54 2254.72   98.74 2255.96
  118.49 2263.58  156.81 2279.72  159.42 2280.61   161.4 2281.07  164.94 2282.67
  175.98  2289.6  191.34 2298.84  197.32  2302.3
#Mann= 3 , 0 , 0
       0      .1       0   60.89     .05       0   98.74      .1       0
Bank Sta=60.89,98.74
Exp/Cntr=0.3,0.1

Type RM Length L Ch R = 1 ,395583.4,101.76,183.46,227.89
XS GIS Cut Line= 4
 1029157.6359782   666858.180418 1029135.9578408  666890.6975788
 1029025.7607605  666932.2473095 1029032.9867861  667038.8313921
#Sta/Elev= 26
       0 2270.671.509979 2269.94    15.7 2264.1116.65999  2263.829.15999 2260.56
39.07999 2259.7246.29999 2259.2554.76999 2258.3863.46999 2257.78   72.25 2257.51
81.04999 2257.04   112.3 2256.44  131.87 2255.76  142.02 2255.62  149.42 2255.43
  156.97 2255.37   170.8 2254.56  184.69 2252.45  190.48 2251.78  201.09 2247.55
  207.02 2246.88  212.58    2246  217.64  2245.8  221.62 2245.77  226.21 2247.67
  263.68 2263.22
#Mann= 4 ,-1 , 0
       0     .05       0  190.48     .08       0  201.09     .05       0
  226.21     .08       0
Bank Sta=201.09,226.21
Exp/Cntr=0.3,0.1

Type RM Length L Ch R = 1 ,395400.0,199.71,331.24,399.01
XS GIS Cut Line= 6
 1029028.5134514  666890.7686783 1028988.4332916  666914.8167681
 1028908.2729719  666930.8488381 1028889.2348982  666947.8828992
 1028858.1727796  666963.9149692 1028801.0585283  667005.9991416
#Sta/Elev= 27
       0 2256.35   19.21 2255.63    55.3 2254.73   81.11 2254.79   88.45 2254.67
   97.45 2254.26  108.59 2253.88  112.19 2253.95  128.89 2253.62  131.69 2253.49
  142.52 2252.58  143.77 2252.33  163.18 2245.99  176.15 2243.54  183.05 2243.24
   187.7 2243.45  194.05 2244.67  200.44 2244.18  202.89 2243.92  206.04 2244.28
  208.32 2244.96  211.41 2245.44  217.41 2248.45  221.87 2251.43  236.43 2261.52
  243.88 2268.42  260.68 2283.33
#Mann= 3 , 0 , 0
       0     .05       0  163.18     .05       0  194.05     .08       0
Bank Sta=163.18,194.05
Exp/Cntr=0.3,0.1

Type RM Length L Ch R = 1 ,395068.7,457.82,443.38,424.49
XS GIS Cut Line= 6
 1029036.7560271  666859.5264955 1029004.6918871  666819.4463356
 1028965.9477255  666798.0702423 1028944.5716322  666776.6941792
 1028829.6751759   666645.765653 1028772.2269478  666623.0535614
#Sta/Elev= 30
       0 2254.92   49.74  2253.9   56.51  2253.1   95.28 2251.58  115.74 2249.73
  132.03 2248.99  163.21  2248.8  171.56 2249.15  178.02 2248.76  179.68 2248.42
  185.58 2246.52  193.17 2243.77  201.86 2241.31   207.7  2238.7  210.42 2238.05
   218.6 2236.93  227.01 2235.44  234.04 2235.12  243.99 2234.79   251.1 2234.75
  259.05 2234.81  263.27 2235.18  274.97 2236.07  283.14 2237.65   296.4 2240.99
  308.24 2244.69  317.67 2249.09  332.76  2255.5  349.74  2264.9  362.13 2272.23
#Mann= 3 , 0 , 0
       0     .05       0  234.04     .05       0  263.27     .08       0
Bank Sta=234.04,263.27
Exp/Cntr=0.3,0.1

Type RM Length L Ch R = 1 ,394625.4,504.33,463.12,441.71
XS GIS Cut Line= 6
 1029277.0104304  666490.3010868 1029208.8741859   666386.092647
 1029168.7940261  666366.0525822 1029142.0739094  666337.9964672
 1029016.4894065  666264.5161691 1028914.9529935  666233.7880577
#Sta/Elev= 30
       0 2254.86    7.99 2252.84   14.57 2250.15   20.65 2248.63   35.19 2246.12
   57.04 2243.29   65.06 2242.62   79.21 2240.91   92.46 2239.78  143.92 2237.09
  157.12 2234.46  170.33  2230.9  187.81 2228.18  191.26 2227.56  198.91 2226.96
  205.19 2226.14  222.78 2228.04  240.48  2229.8  258.04 2230.86  271.43  2231.1
  291.86 2230.93  310.68 2232.06  332.45    2236  338.86 2237.91  352.35 2239.76
  373.84  2242.1  410.29  2247.4  418.49 2248.32  442.32 2252.14  459.86 2254.03
#Mann= 3 , 0 , 0
       0     .05       0  187.81     .05       0  222.78     .05       0
#XS Ineff= 2 , 0
       0                  271.43       0  2231.1
Permanent Ineff=
       F       F
Bank Sta=187.81,222.78
Exp/Cntr=0.3,0.1

Type RM Length L Ch R = 1 ,394162.2,365.95,402.25,399.81
XS GIS Cut Line= 6
 1029540.6160337  665972.9905963 1029497.6198266  665973.9234553
 1029378.0301691  665949.5059751 1029254.4668407  665897.7711304
 1029199.6906091  665865.7070207  1028942.661299   665767.048487
#Sta/Elev= 30
       0 2263.21    41.6 2247.12   64.28 2240.07   80.23 2236.05   99.72 2233.67
  158.32 2232.61  192.07 2230.28   202.7 2228.42  207.72 2226.77  215.03 2223.33
  217.88 2221.99  223.12 2220.89  230.69  2220.6  238.01 2220.89  251.04  2223.1
  271.32 2225.15  293.54 2228.63  375.93 2231.62  402.28 2233.55   423.5 2236.32
  437.75 2239.14  458.41  2244.7  467.46 2246.51  517.89 2253.97  571.88 2264.27
  590.72 2270.84  595.78 2272.07  602.45 2275.16  617.56 2279.86  638.63 2288.91
#Mann= 3 , 0 , 0
       0     .05       0  215.03     .05       0  251.04     .05       0
Bank Sta=215.03,251.04
Exp/Cntr=0.3,0.1

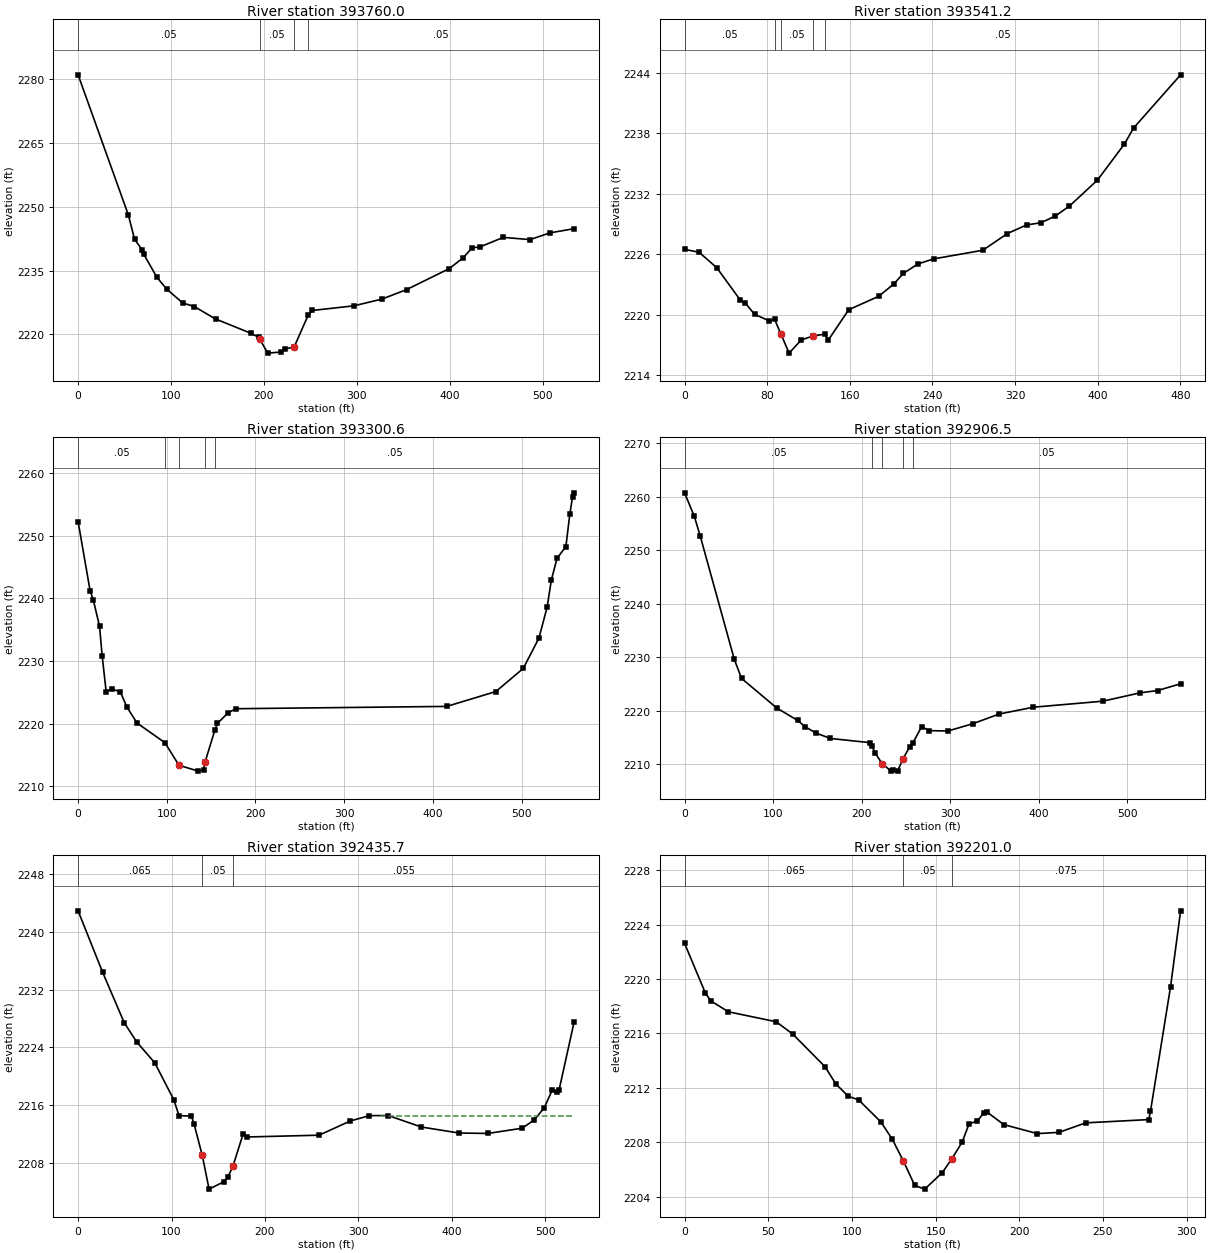
Type RM Length L Ch R = 1 ,393760.0,220.58,218.77,280.97
XS GIS Cut Line= 6
 1029699.1881224  665707.4019562 1029534.8594881  665580.4814247
 1029445.9436413  665541.0654048 1029369.7315069  665525.8229658
 1029266.0830246  665552.2431874 1029223.4042075  665554.2755005
#Sta/Elev= 30
       0 2280.98    54.1 2248.06   60.77 2242.34   68.71 2239.95   70.76 2238.81
    84.7 2233.46    95.3 2230.65  112.38 2227.44  125.24 2226.53  147.89 2223.64
  185.76  2220.3  194.52 2219.31  195.62 2218.86     204 2215.62  218.43 2215.88
  223.03 2216.59  232.54 2217.09  247.42 2224.47  252.15 2225.64  296.75 2226.73
  326.92 2228.31  353.55 2230.55  399.36 2235.47  414.25 2237.99  424.07 2240.39
  432.01 2240.53  457.51  2242.8  486.33 2242.28  507.63 2243.86  533.74 2244.85
#Mann= 4 ,-1 , 0
       0     .05       0  195.62     .05       0  232.54     .08       0
  247.42     .05       0
Bank Sta=195.62,232.54
Exp/Cntr=0.3,0.1

Type RM Length L Ch R = 1 ,393541.2,228.23,240.58,246.28
XS GIS Cut Line= 6
 1029748.3646873  665479.8134302 1029656.2326862  665396.7139688
 1029583.9722784  665326.2601052 1029497.2598193  665299.1624561
 1029392.4822507  665248.5801857 1029361.7715736  665212.4499667
#Sta/Elev= 30
       0 2226.48   14.04 2226.19   31.16 2224.66   53.98 2221.44   58.67 2221.17
    67.7 2220.04   82.16 2219.37   87.08 2219.55   93.29 2218.07  101.18 2216.18
  112.99 2217.49  124.32 2217.88  135.48 2218.06  139.24 2217.49  158.91 2220.49
  187.75 2221.81  202.41 2223.03   211.9  2224.1  225.88 2225.03  240.99 2225.53
  288.72 2226.39  312.54 2228.05     331  2228.9  344.96 2229.12  358.78 2229.78
  372.61 2230.78  399.65 2233.35  425.76 2236.93  434.63 2238.52  480.17  2243.8
#Mann= 5 ,-1 , 0
       0     .05       0   87.08     .08       0   93.29     .05       0
  124.32     .08       0  135.48     .05       0
#XS Ineff= 2 , 0
       0   87.08 2219.55  135.48       0 2218.06
Permanent Ineff=
       F       F
Bank Sta=93.29,124.32
Exp/Cntr=0.3,0.1

Type RM Length L Ch R = 1 ,393300.6,388.48,394.1,421.25
XS GIS Cut Line= 6
 1029907.3375239  665322.6470773 1029797.1404436  665194.3848874
 1029558.6811433  665040.8315322  1029504.485845  665006.5078574
 1029470.1621702  664984.8297502 1029470.1621702  664983.0232362
#Sta/Elev= 30
       0 2252.29   13.54 2241.23   17.28 2239.69   24.16 2235.58   27.11 2230.89
   31.62 2225.14   37.91 2225.55   47.54 2225.08   55.17 2222.63   66.39 2220.11
   97.91 2216.96   113.7 2213.36  135.45 2212.42   141.4 2212.66  143.19 2213.89
  154.35 2219.05   157.1 2220.04   169.1 2221.74  178.02 2222.39  415.63 2222.76
  470.96 2225.13  501.92 2228.83  519.53 2233.66  528.74 2238.57  533.62 2242.99
  540.03 2246.43  549.96 2248.29  554.36 2253.46  557.47 2256.25  559.27 2256.88
#Mann= 5 ,-1 , 0
       0     .05       0   97.91     .08       0   113.7     .05       0
  143.19     .08       0  154.35     .05       0
Bank Sta=113.7,143.19
Exp/Cntr=0.3,0.1

Type RM Length L Ch R = 1 ,392906.5,455.83,470.83,478.11
XS GIS Cut Line= 6
 1030256.3023656  665124.9036248 1030197.5181392  665071.4633915
 1030129.3818644  664972.5990052 1030079.9496562  664935.1908419
 1030044.6322837  664896.3107468 1029890.2369035  664705.3979294
#Sta/Elev= 30
       0 2260.73      11 2256.34   17.72 2252.63   56.17 2229.58   64.32 2226.02
  103.95  2220.5  127.73 2218.15  136.28 2216.96  148.53 2215.78  164.68 2214.78
  209.16    2214  211.85 2213.28  215.15 2212.07  223.17 2210.06  233.25 2208.67
  235.64  2208.9  240.79 2208.78  246.58 2210.97  254.07 2213.15  257.52 2213.85
  267.71 2216.99  276.09 2216.25  297.22 2216.17  325.33 2217.53   355.4 2219.36
  394.01 2220.63  472.19 2221.75   514.3 2223.31  534.26 2223.75  560.15 2225.01
#Mann= 5 ,-1 , 0
       0     .05       0  211.85     .08       0  223.17     .05       0
  246.58     .08       0  257.52     .05       0
Bank Sta=223.17,246.58
Exp/Cntr=0.3,0.1

Type RM Length L Ch R = 1 ,392435.7,236.7,234.7,266.28
XS GIS Cut Line= 6
 1030608.2633435  664838.5024508 1030536.0029357   664764.435529
 1030494.4532353   664708.433747 1030391.4821504  664610.8822041
 1030348.1259359  664437.4572556  1030339.093366  664401.3270668
#Sta/Elev= 30
       0 2242.91   26.33 2234.38   49.34 2227.43   62.75 2224.75      82 2221.88
  102.38 2216.77  108.06 2214.55  121.32 2214.48  124.13  2213.4  132.91 2209.05
  140.22 2204.37  155.77 2205.37  160.47 2206.05  165.91 2207.61  176.55 2211.96
  180.89 2211.59     258 2211.84  291.28  2213.8  311.93 2214.55  332.11 2214.56
  367.53 2212.97  407.88 2212.14  438.56 2212.08  475.28  2212.8  488.46 2213.96
  499.13 2215.65  507.43 2218.04  512.89 2217.81  514.81 2218.03  531.06 2227.54
#Mann= 3 , 0 , 0
       0    .065       0  132.91     .05       0  165.91    .055       0
#XS Ineff= 2 , 0
       0                  323.24       0 2214.56
Permanent Ineff=
       F       F
Bank Sta=132.91,165.91
Exp/Cntr=0.3,0.1

Type RM Length L Ch R = 1 ,392201.0,126.09,76.95,45.58
XS GIS Cut Line= 4
  1030747.364587  664656.0449627 1030673.2976954  664554.8804221
 1030628.1349368  664527.7827729 1030602.8438016  664412.1661204
#Sta/Elev= 30
       0 2222.62   12.47 2218.96   15.81 2218.38   26.23 2217.59   54.72 2216.86
   64.58 2215.96   83.96 2213.55   90.44 2212.28   97.88 2211.38  104.01 2211.12
  117.36 2209.49  124.21 2208.21  130.76 2206.62  137.54 2204.83  143.51 2204.56
  153.98 2205.77  159.69 2206.79  165.85 2208.01  169.98 2209.35   174.9 2209.57
  178.97 2210.19  180.94  2210.2  190.79  2209.3  210.77 2208.64   223.7 2208.73
  239.67 2209.43  277.36 2209.67   278.4 2210.28  290.37 2219.42   296.4 2225.01
#Mann= 3 , 0 , 0
       0    .065       0  130.76     .05       0  159.69    .075       0
Bank Sta=130.76,159.69
Exp/Cntr=0.5,0.3

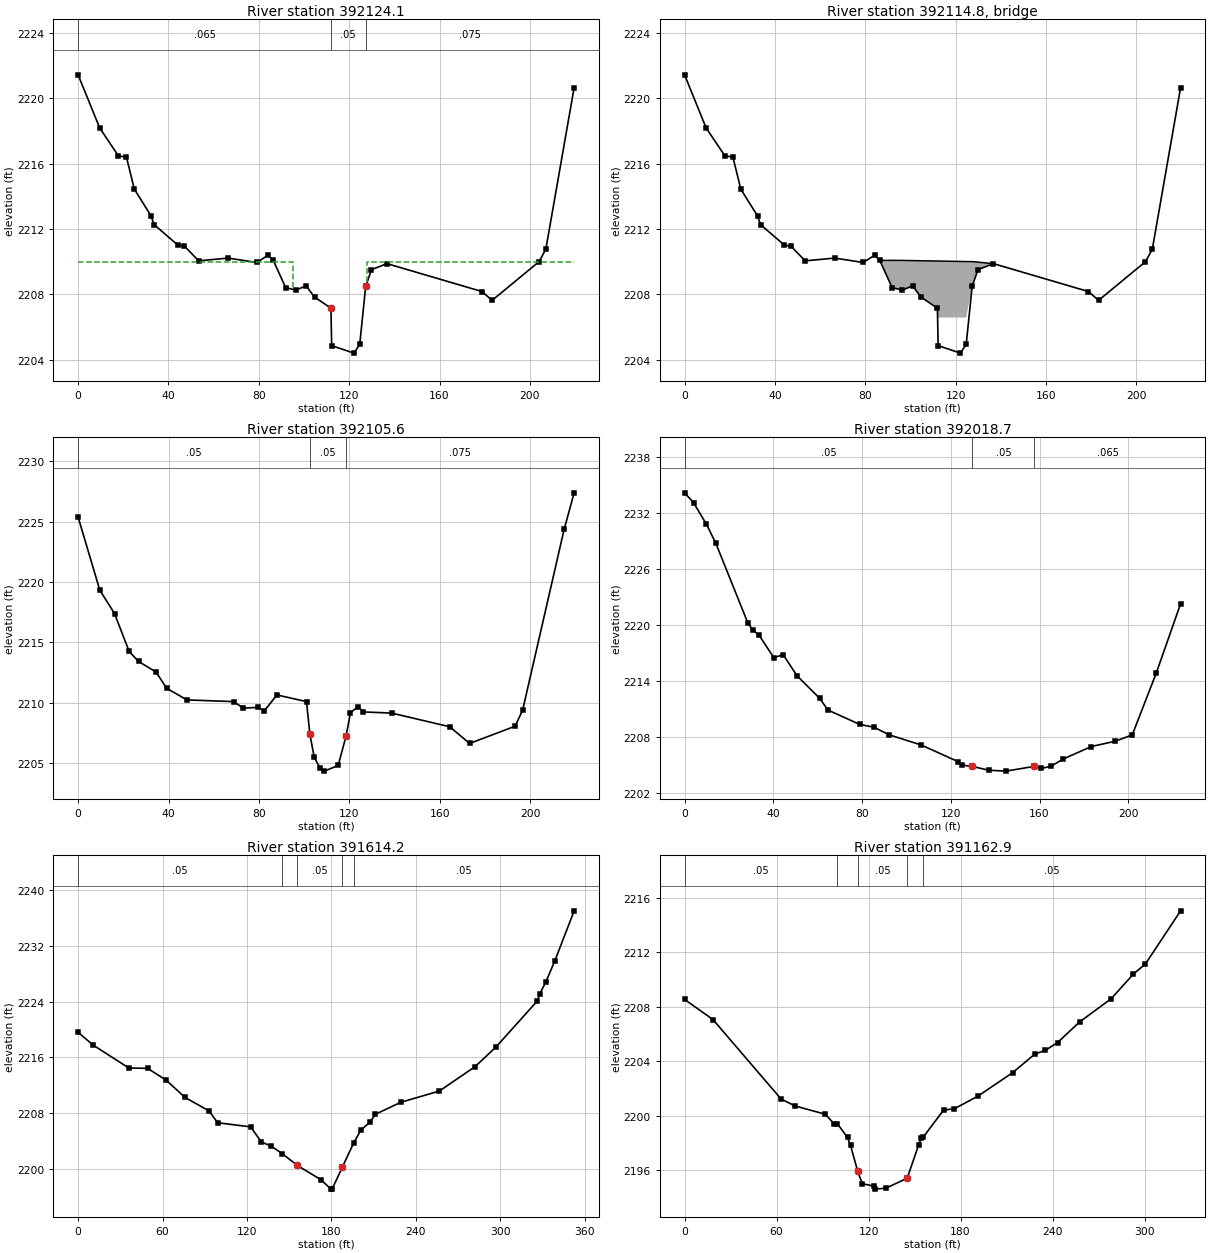
Type RM Length L Ch R = 1 ,392124.1,24.17,18.45,15.26
XS GIS Cut Line= 6
 1030798.8360094  664520.9660006 1030759.9678097  664516.3932659
 1030727.9587271   664495.816005 1030683.0076627  664473.6721644
 1030664.7026492  664460.7584225 1030634.9799189  664397.5023446
#Sta/Elev= 30
       0 2221.44    9.55 2218.19   17.88 2216.47   21.39 2216.41    24.9 2214.44
    32.3  2212.8   33.64 2212.27    44.2 2211.01   47.07 2210.95   53.41 2210.05
   66.44 2210.22   79.09 2209.95    84.1 2210.39   86.39 2210.08   91.89 2208.41
   96.46 2208.26  100.94 2208.52  104.69 2207.83  111.93 2207.15  112.25 2204.86
  122.11  2204.4  124.68 2204.94   127.3 2208.48  129.87 2209.51  136.72 2209.88
  178.81 2208.17  183.27 2207.63  204.04    2210  207.06 2210.76  219.59 2220.66
#Mann= 3 , 0 , 0
       0    .065       0  111.93     .05       0   127.3    .075       0
#XS Ineff= 2 , 0
       0      95    2210     128       0    2210
Permanent Ineff=
       F       F
Bank Sta=111.93,127.3
Exp/Cntr=0.5,0.3

Type RM Length L Ch R = 3 ,392114.8,,,
BEGIN DESCRIPTION:
STR_157
END DESCRIPTION:
Bridge Culvert--1,0,-1,-1, 0
Deck Dist Width WeirC Skew NumUp NumDn MinLoCord MaxHiCord MaxSubmerge Is_Ogee
3.5,12,2.6,0, 4, 4, 2213, , 0.95, 0, 0,0,,
   86.39      95     128  135.69
 2210.08 2210.08    2210 2209.89
         2206.58 2206.58
   86.39      95     128     140
 2210.08 2210.08    2210    2209
         2206.58 2206.58
BR Coef=-1 , 1 , 0 ,, 0 ,,,0.8,0,2,0,
WSPro=,,,, 1 ,,,, 0 ,,,, 0 ,,,,-1 ,-1 ,-1 , 0 , 0 , 0 , 0 , 0
BC Design=,, 0 ,, 0 ,,,,,,

Type RM Length L Ch R = 1 ,392105.6,56.98,86.92,66.25
XS GIS Cut Line= 6
 1030809.5057137  664500.3887397 1030769.8753965  664490.4811529
 1030735.5799315  664479.0493312  1030690.628867  664456.9054906
 1030672.3238535  664443.9917487 1030642.6011232  664380.7356708
#Sta/Elev= 30
       0 2225.38    9.58 2219.34   16.12 2217.39   22.58 2214.26   26.74 2213.43
   34.46 2212.56   39.19 2211.21   48.17 2210.25   68.87 2210.11   73.07 2209.57
   79.44 2209.63   82.41 2209.36   87.94 2210.66  101.03 2210.11  102.51 2207.42
  104.43 2205.51  107.01 2204.61  108.91 2204.36  115.04 2204.83  118.57  2207.3
  120.47  2209.2  123.92  2209.7     126 2209.26  138.72 2209.16  164.36 2208.03
  173.17 2206.65  193.24 2208.07   196.6 2209.39  214.96 2224.35   219.4 2227.38
#Mann= 3 , 0 , 0
       0     .05       0  102.51     .05       0  118.57    .075       0
#XS Ineff= 2 , 0
       0      95    2208     128       0    2208
Permanent Ineff=
       F       F
Bank Sta=102.51,118.57
Exp/Cntr=0.5,0.3

Type RM Length L Ch R = 1 ,392018.7,384.31,404.52,448.8
XS GIS Cut Line= 4
 1030853.7087353  664482.0978311 1030786.6420703   664402.837227
 1030714.2405532  664376.9250837 1030687.5662925  664343.3917664
#Sta/Elev= 30
       0 2234.19    4.04 2233.14    9.87 2230.81   14.12 2228.76   28.48 2220.24
   30.68 2219.47   33.52 2218.92   40.22 2216.49   44.46  2216.8    50.7 2214.54
   60.89 2212.12   64.61 2210.86   79.04 2209.31   85.32 2209.02   92.22  2208.2
  106.73  2207.1  123.17 2205.33  124.93 2204.95  129.76  2204.8  137.08  2204.4
  144.79  2204.3  157.62 2204.81  160.86  2204.6  164.94  2204.8  170.75 2205.61
  183.32 2206.94  194.07 2207.51  201.78 2208.19  212.67 2214.88  223.57 2222.28
#Mann= 3 , 0 , 0
       0     .05       0  129.76     .05       0  157.62    .065       0
Bank Sta=129.76,157.62
Exp/Cntr=0.3,0.1

Type RM Length L Ch R = 1 ,391614.2,431.11,451.29,402.55
XS GIS Cut Line= 6
 1031160.0815079  664315.1932406 1031150.1739513  664253.4614278
 1031114.3542515  664240.5053713 1031084.6314909  664194.0159671
 1031061.0057301  664126.9492719 1030960.0282153  664053.4089826
#Sta/Elev= 30
       0 2219.61    10.7 2217.77   36.07 2214.48   49.35 2214.43   62.52 2212.74
   75.97 2210.25   93.07  2208.3   99.17 2206.61  122.57 2206.02  130.24 2203.84
  136.98 2203.28  145.17 2202.15  155.79 2200.47   172.4 2198.44  179.71 2197.07
  180.46 2197.07  187.63 2200.18  195.72 2203.68  200.85 2205.55  207.21 2206.67
  211.27 2207.83  229.12 2209.54  256.66 2211.17     282 2214.67  296.82 2217.48
  326.35 2224.14  327.81 2225.07  332.35 2226.86  338.72 2229.89  352.42 2237.07
#Mann= 5 ,-1 , 0
       0     .05       0  145.17     .08       0  155.79     .05       0
  187.63     .08       0  195.72     .05       0
Bank Sta=155.79,187.63
Exp/Cntr=0.3,0.1

Type RM Length L Ch R = 1 ,391162.9,49.25,24.08,45.35
XS GIS Cut Line= 6
 1031444.7441195  664019.5799471 1031458.5301542  663948.8117203
 1031442.4464471  663912.0489914 1031414.4148795  663884.4769522
 1031306.6968071  663825.3574172 1031278.4382296  663786.8943543
#Sta/Elev= 30
       0 2208.54    18.5 2207.07   62.95 2201.24   72.07 2200.73   91.88 2200.12
   97.43 2199.43   99.56 2199.44  106.28 2198.42  108.26 2197.83  112.93 2195.94
  115.86 2195.03  123.46 2194.85  124.13 2194.63  131.34  2194.7  145.21 2195.43
  152.68 2197.87  154.42 2198.36  155.78 2198.46  168.96 2200.43  175.86 2200.52
  191.21 2201.44  213.97 2203.17  228.49 2204.54  235.17  2204.8  243.28 2205.38
  257.64 2206.89  278.33  2208.6  292.79 2210.41  300.56 2211.14  323.54 2215.04
#Mann= 5 ,-1 , 0
       0     .05       0   99.56     .08       0  112.93     .05       0
  145.21     .08       0  155.78     .05       0
Bank Sta=112.93,145.21
Exp/Cntr=0.5,0.3

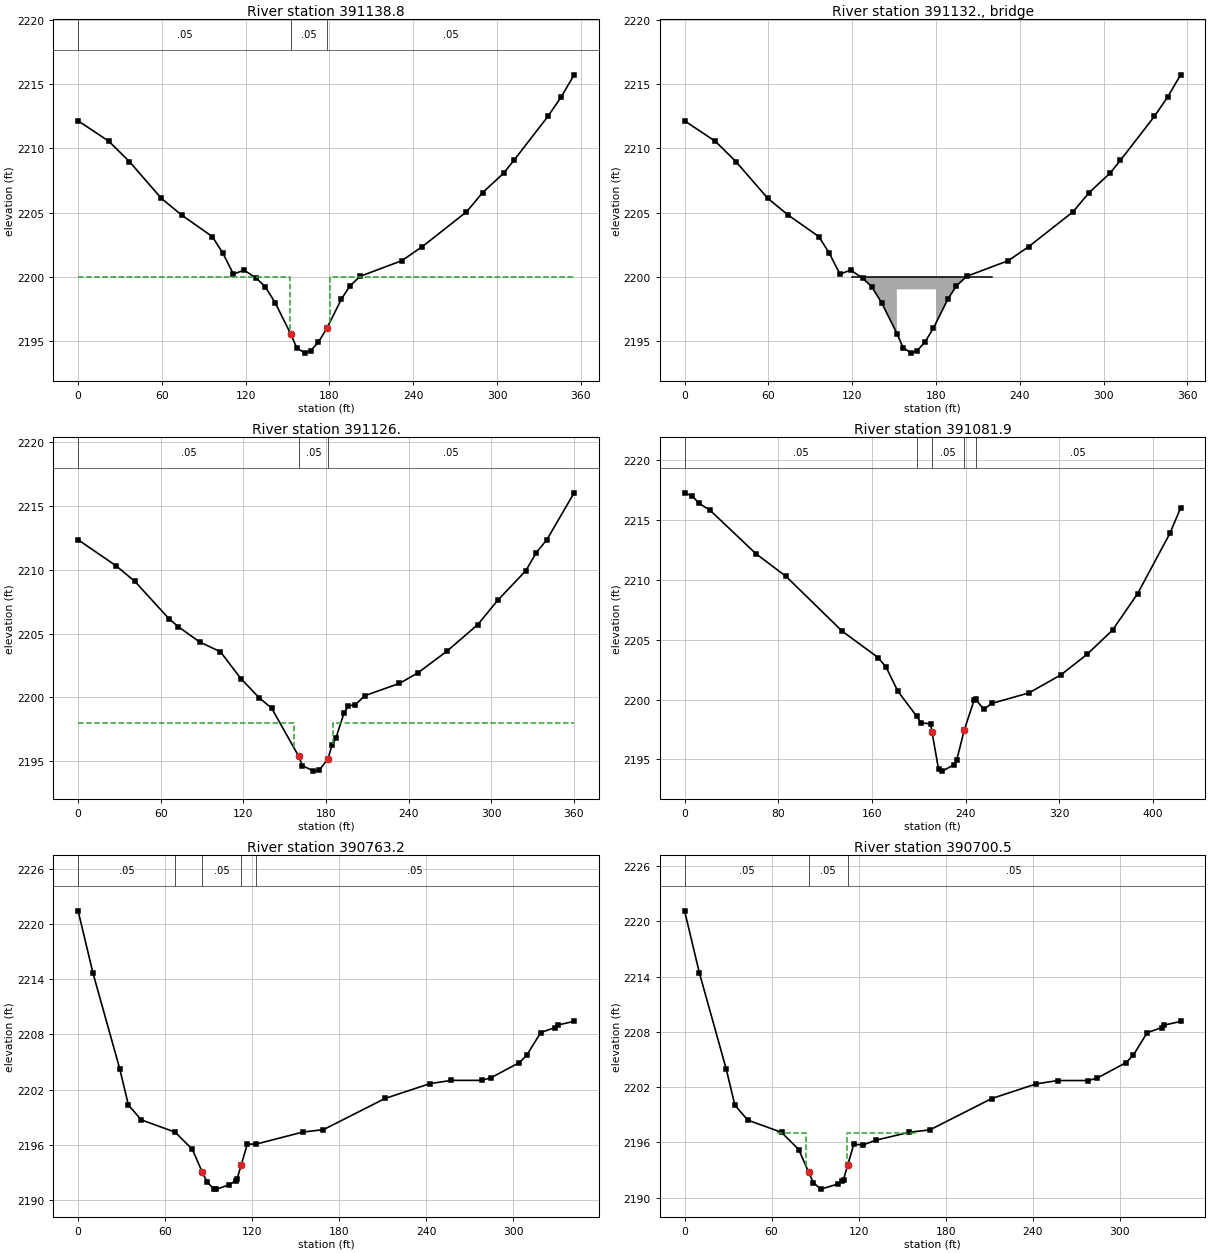
Type RM Length L Ch R = 1 ,391138.8,22,12.84,14.6
XS GIS Cut Line= 6
  1031571.115953  663992.4674364 1031501.7263418  663945.1354323
   1031435.55346  663864.2574588 1031425.9032417  663855.5263277
 1031374.4354212  663815.5468694  1031297.939585    663771.46495
#Sta/Elev= 30
       0 2212.16   22.04 2210.56   36.73 2208.98   59.56 2206.11   74.16  2204.8
   96.11 2203.12  103.77  2201.8   111.2 2200.19   118.9  2200.5  127.46 2199.88
  133.94 2199.21  141.03 2197.97  152.22 2195.52  156.47 2194.45  162.31 2194.02
  166.44 2194.21  171.88 2194.85  178.13 2195.96   188.5 2198.23  194.63 2199.27
  202.04 2200.02  231.81 2201.24  246.49 2202.34  278.09 2205.05  289.62 2206.55
  304.64 2208.07  312.03 2209.07  336.36  2212.5  345.82 2214.01  355.17 2215.75
#Mann= 3 , 0 , 0
       0     .05       0  152.22     .05       0  178.13     .05       0
#XS Ineff= 2 , 0
       0  151.95    2200  180.04       0    2200
Permanent Ineff=
       F       F
Bank Sta=152.22,178.13
Exp/Cntr=0.5,0.3

Type RM Length L Ch R = 3 ,391132. ,,,
BEGIN DESCRIPTION:
Private Bridge
END DESCRIPTION:
Bridge Culvert--1,0,-1,-1, 0
Deck Dist Width WeirC Skew NumUp NumDn MinLoCord MaxHiCord MaxSubmerge Is_Ogee
2.4,8,2.6,0, 4, 4, 2200, , 0.95, 0, 0,0,,
     120     152     180     220
    2200    2200    2200    2200
            2199    2199
     120     157     185     220
    2200    2200    2200    2200
            2199    2199
BR Coef=-1 , 1 , 0 ,, 0 ,,,0.8,0,2,0,
WSPro=,,,, 1 ,,,, 0 ,,,, 0 ,,,,-1 ,-1 ,-1 , 0 , 0 , 0 , 0 , 0
BC Design=,, 0 ,, 0 ,,,,,,

Type RM Length L Ch R = 1 ,391126. ,38.9,44.04,37.8
XS GIS Cut Line= 6
 1031584.9649095   663982.884838 1031553.7166126   663942.445821
  1031540.849665  663932.3360744  1031497.193949   663913.954725
 1031402.9894692  663812.3977297 1031314.0419318  663753.7449874
#Sta/Elev= 30
       0 2212.36   27.43 2210.33   41.29 2209.09   65.89 2206.18    72.8 2205.54
   88.36 2204.34  103.36 2203.58  118.16 2201.48  131.62 2199.96  140.54 2199.16
  160.23 2195.38  162.81 2194.66  170.95 2194.22  175.15 2194.29  181.54  2195.2
   184.3 2196.23  187.23 2196.81  193.07 2198.76  196.24 2199.33  201.35 2199.44
  208.38 2200.14  233.41  2201.1  246.74 2201.92  268.05 2203.64  290.28 2205.71
  304.65  2207.6   325.2 2209.94  332.58 2211.32  340.52 2212.38  360.25 2216.04
#Mann= 3 , 0 , 0
       0     .05       0  160.23     .05       0  181.54     .05       0
#XS Ineff= 2 , 0
       0     157    2198     185       0    2198
Permanent Ineff=
       F       F
Bank Sta=160.23,181.54
Exp/Cntr=0.5,0.3

Type RM Length L Ch R = 1 ,391081.9,427,318.96,330.7
XS GIS Cut Line= 6
 1031621.6998276  664030.7152334 1031597.6517377  663994.6430986
 1031569.5956228  663934.5228437 1031509.4753679  663861.0425456
 1031480.0832547  663828.9784359 1031340.7690155  663723.3370494
#Sta/Elev= 30
       0 2217.26     6.7 2216.99   12.37 2216.37   21.38 2215.84   60.88 2212.18
   86.65 2210.28  134.64  2205.7  165.32  2203.5  172.05  2202.7  182.07  2200.7
  198.25 2198.59  202.06 2198.04  210.02 2197.98  211.25 2197.29  216.81  2194.2
  219.93 2194.02  230.18 2194.56  232.31 2194.92  238.73 2197.43  247.15 2199.93
  248.68 2200.01  255.44 2199.17  262.08 2199.67  294.03 2200.55  321.48 2202.07
  343.64 2203.77  365.42  2205.8  386.86 2208.85   414.4 2213.88  423.52    2216
#Mann= 5 ,-1 , 0
       0     .05       0  198.25     .08       0  211.25     .05       0
  238.73     .08       0  248.68     .05       0
Bank Sta=211.25,238.73
Exp/Cntr=0.3,0.1

Type RM Length L Ch R = 1 ,390763.2,61.2,62.68,54.1
XS GIS Cut Line= 6
 1031807.0547595  663672.5088524 1031736.2654662  663637.4449742
 1031701.2016183  663607.0121874 1031596.0100442  663576.5794006
 1031559.6230014  663544.8234794 1031505.3732813  663562.0245895
#Sta/Elev= 30
       0 2221.42   10.16 2214.72   28.73 2204.25   34.67 2200.34   43.54 2198.72
   66.85 2197.39   78.75 2195.52   85.45  2193.1   89.04 2191.94   93.75 2191.21
   95.39  2191.2  104.34 2191.68  108.65 2192.11  109.57 2192.27  112.45 2193.83
  116.65 2196.09  122.76 2196.09  154.75 2197.39  169.15 2197.66  211.67 2201.05
  242.43 2202.65  257.41 2203.01  278.38 2203.01  284.59 2203.29  304.29 2204.95
  309.36 2205.76  318.92  2208.2  328.84 2208.75  330.61 2209.02  341.97 2209.42
#Mann= 5 ,-1 , 0
       0     .05       0   66.85     .08       0   85.45     .05       0
  112.45     .08       0  122.76     .05       0
Bank Sta=85.45,112.45
Exp/Cntr=0.5,0.3

Type RM Length L Ch R = 1 ,390700.5,30.61,29.42,25.87
XS GIS Cut Line= 6
  1031851.664753  663628.5859603 1031780.8754597  663593.5220821
 1031745.8116118  663563.0892953 1031640.6200377  663532.6565085
 1031604.2329949  663500.9005873 1031549.9832748  663518.1016974
#Sta/Elev= 30
       0 2221.13   10.16 2214.43   28.73 2203.96   34.67 2200.05   43.54 2198.43
   66.85  2197.1   78.75 2195.23   85.45 2192.81   88.83 2191.63   93.94 2190.94
  105.92  2191.5  108.65 2191.82  109.57 2191.98  112.45 2193.54  116.65  2195.8
  123.29 2195.74  131.65 2196.24  154.75  2197.1  169.15 2197.37  211.67 2200.76
  242.43 2202.36  257.41 2202.72  278.38 2202.72  284.59    2203  304.29 2204.66
  309.36 2205.47  318.92 2207.91  328.84 2208.46  330.61 2208.73  341.97 2209.13
#Mann= 3 , 0 , 0
       0     .05       0   85.45     .05       0  112.45     .05       0
#XS Ineff= 2 ,-1
   63.64      84    2197     112     160    2197
Permanent Ineff=
       T       T
Bank Sta=85.45,112.45
Exp/Cntr=0.5,0.3

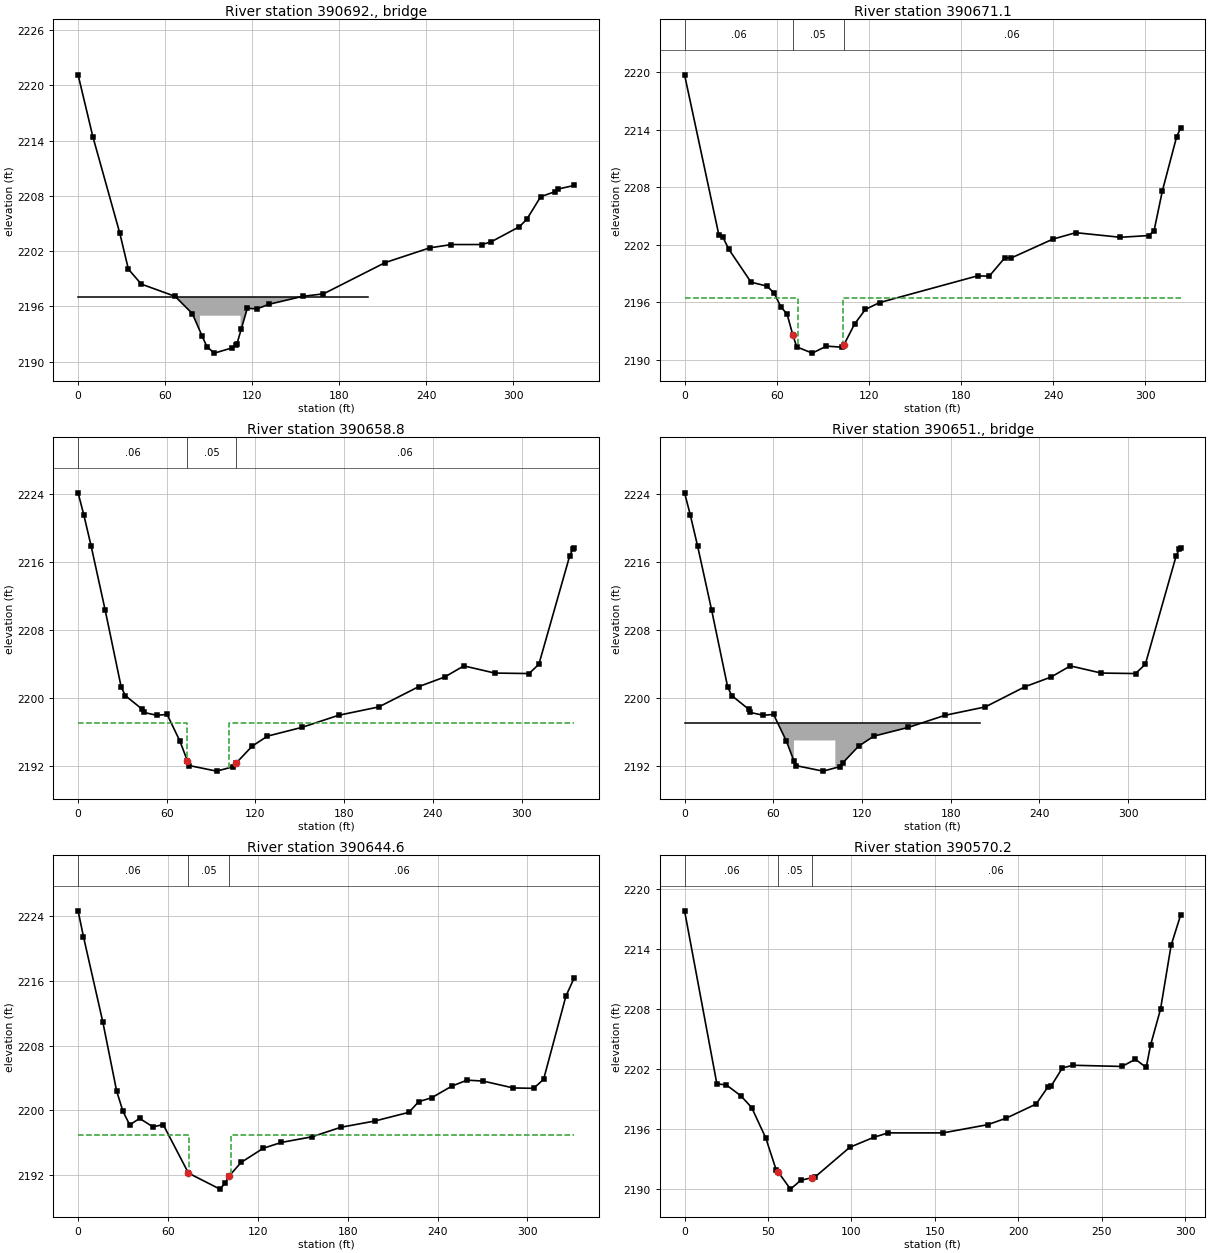
Type RM Length L Ch R = 3 ,390692. ,,,
BEGIN DESCRIPTION:
STR_1067
END DESCRIPTION:
Bridge Culvert--1,0,-1,-1, 0
Deck Dist Width WeirC Skew NumUp NumDn MinLoCord MaxHiCord MaxSubmerge Is_Ogee
3.5,12,2.6,0, 4, 4, 2197, , 0.95, 0, 0,0,,
       0      84     112     200
    2197    2197    2197    2197
            2195    2195
       0      74     103     200
    2197    2197    2197    2197
            2195    2195
BR Coef=-1 , 1 , 0 ,, 0 ,,,0.8,0,2,0,
WSPro=,,,, 1 ,,,, 0 ,,,, 0 ,,,,-1 ,-1 ,-1 , 0 , 0 , 0 , 0 , 0
BC Design=,, 0 ,, 0 ,,,,,,

Type RM Length L Ch R = 1 ,390671.1,17.17,12.34,6.22
XS GIS Cut Line= 6
 1031864.2348322  663600.1379053 1031821.8935636   663584.921527
 1031765.6590814  663546.5497524 1031710.7477639  663527.3638499
 1031651.2053549  663518.7632948 1031586.3702874   663457.236154
#Sta/Elev= 30
       0 2219.74   22.38 2203.01   24.87 2202.84   28.85 2201.54   43.28 2198.12
   53.81  2197.7   58.49 2196.94    62.7 2195.54   66.73  2194.8   70.52 2192.59
   73.03 2191.37   83.15 2190.72    92.4 2191.45  102.54 2191.34  103.63 2191.55
  110.69 2193.75  117.74 2195.28  126.98 2195.99  190.84 2198.78  198.36 2198.74
  208.36 2200.63   212.8 2200.65  239.83 2202.61  254.76 2203.28   283.7  2202.8
  302.33 2202.98  305.71  2203.5   311.1 2207.64  320.41  2213.3  322.98 2214.17
#Mann= 3 , 0 , 0
       0     .06       0   70.52     .05       0  103.63     .06       0
#XS Ineff= 2 , 0
       0      74  2196.5     103       0  2196.5
Permanent Ineff=
       F       F
Bank Sta=70.52,103.63
Exp/Cntr=0.5,0.3

Type RM Length L Ch R = 1 ,390658.8,14.5,14.13,13.12
XS GIS Cut Line= 6
 1031875.4817166  663586.9062589 1031809.3235147  663563.0892953
 1031755.0737643  663524.0559534 1031655.1748488  663511.4858742
 1031612.1719828  663479.0683555 1031586.3702874  663446.6508369
#Sta/Elev= 30
       0 2224.09    3.89 2221.48    8.83 2217.83   18.36 2210.28    29.1 2201.32
   31.87 2200.28   43.37 2198.67   44.25  2198.3    53.3 2197.96   60.21 2198.06
   68.92 2194.91   73.86 2192.64    75.3 2192.05   93.64  2191.4  104.82 2191.91
  106.88 2192.34  117.72 2194.33  128.08 2195.51  151.43 2196.54  176.21 2197.96
   203.4 2198.94  230.48 2201.33   247.9 2202.45  260.94 2203.76  281.82 2202.92
  305.06 2202.86   311.7 2203.96  332.43 2216.62  334.59  2217.5  335.54 2217.63
#Mann= 3 , 0 , 0
       0     .06       0   73.86     .05       0  106.88     .06       0
#XS Ineff= 2 , 0
       0      74    2197  102.14       0    2197
Permanent Ineff=
       T       T
Bank Sta=73.86,106.88
Exp/Cntr=0.5,0.3

Type RM Length L Ch R = 3 ,390651. ,,,
BEGIN DESCRIPTION:
Private Bridge
END DESCRIPTION:
Bridge Culvert--1,0,-1,-1, 0
Deck Dist Width WeirC Skew NumUp NumDn MinLoCord MaxHiCord MaxSubmerge Is_Ogee
1,12,2.6,0, 4, 4, 2197, , 0.95, 0, 0,0,,
       0      74     102     200
    2197    2197    2197    2197
            2195    2195
       0      74     102     200
    2197    2197    2197    2197
            2195    2195
BR Coef=-1 , 1 , 0 ,, 0 ,,,0.8,0,2,0,
WSPro=,,,, 1 ,,,, 0 ,,,, 0 ,,,,-1 ,-1 ,-1 , 0 , 0 , 0 , 0 , 0
BC Design=,, 0 ,, 0 ,,,,,,

Type RM Length L Ch R = 1 ,390644.6,65.68,74.4,72.74
XS GIS Cut Line= 6
 1031881.4359726  663573.0130452 1031813.9545758  663546.5497524
 1031763.0127521  663509.5011423 1031679.6533796  663510.1627398
 1031661.1290746  663502.2237519 1031596.9556045  663438.0502516
#Sta/Elev= 30
       0 2224.64    3.57 2221.46   16.51 2210.92   25.76 2202.38   29.98 2199.88
    34.5 2198.21   41.04 2199.02   50.05 2197.97   56.81 2198.26   73.68 2192.27
    94.7 2190.29   98.17 2191.03  100.83  2191.9  108.87 2193.59  123.61 2195.33
  135.64 2196.05  155.99 2196.74  175.57 2197.93  197.98 2198.69   220.9 2199.77
  227.46 2201.09  236.01 2201.56  249.61 2203.01  259.74 2203.74  270.41 2203.63
  290.48 2202.78  304.17 2202.73  310.83 2203.84  325.75 2214.12  331.23 2216.35
#Mann= 3 , 0 , 0
       0     .06       0   73.68     .05       0  100.83     .06       0
#XS Ineff= 2 , 0
       0      74    2197  102.13       0    2197
Permanent Ineff=
       T       T
Bank Sta=73.68,100.83
Exp/Cntr=0.5,0.3

Type RM Length L Ch R = 1 ,390570.2,374.34,382.78,404.56
XS GIS Cut Line= 6
 1031900.6218448  663520.7480267  1031888.713363  663504.2084838
 1031796.7534354  663449.2971662 1031768.9669779  663445.3276723
 1031708.7630018  663445.3276723 1031646.5742635  663393.7242512
#Sta/Elev= 30
       0 2217.86   19.37 2200.53   24.97 2200.44   33.74 2199.34   40.19 2198.17
   48.66 2195.12   54.86 2191.94   56.02 2191.73   63.45    2190   69.62 2190.88
   76.11 2191.14    78.2 2191.22   99.01 2194.19  113.55  2195.2  121.96 2195.63
  154.87 2195.63  181.57 2196.45  192.67  2197.1  210.66 2198.52  217.52 2200.19
  219.73 2200.35  226.35 2202.13  232.68  2202.4  262.05 2202.28   270.1    2203
  276.57 2202.18  279.25 2204.46  285.14    2208  291.49  2214.4  297.19 2217.43
#Mann= 3 , 0 , 0
       0     .06       0   56.02     .05       0   76.11     .06       0
Bank Sta=56.02,76.11
Exp/Cntr=0.3,0.1