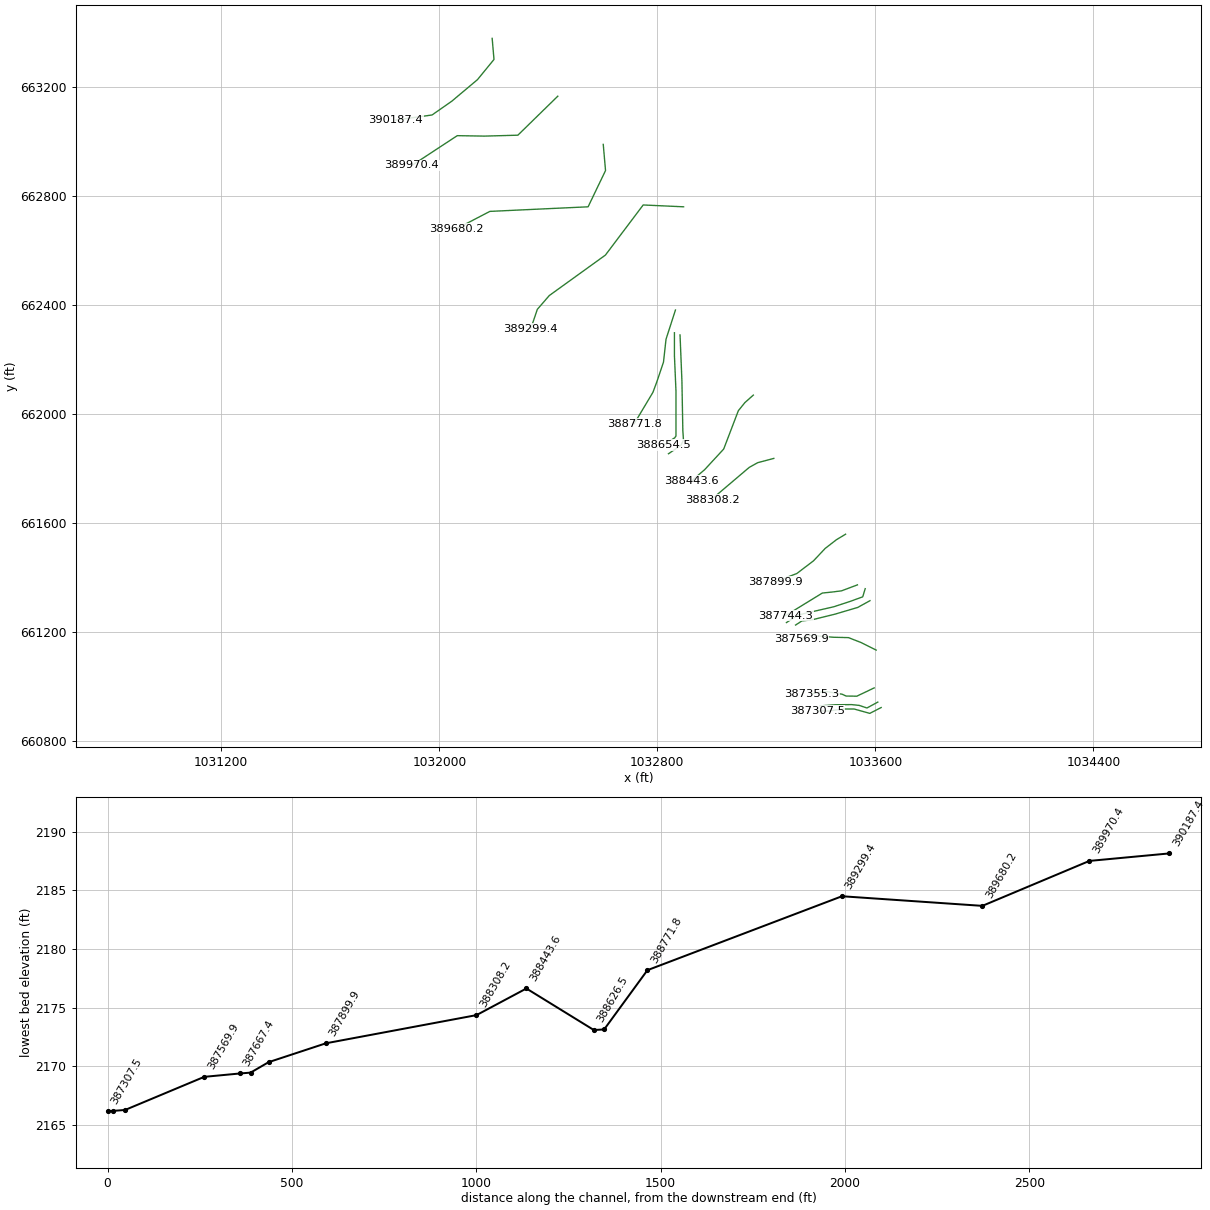
HEC-RAS study lds_broad_rvr.prj: Upper_Broad 3-06-07

--- lds_broad_rvr.g05 (geometry) --- (continued)

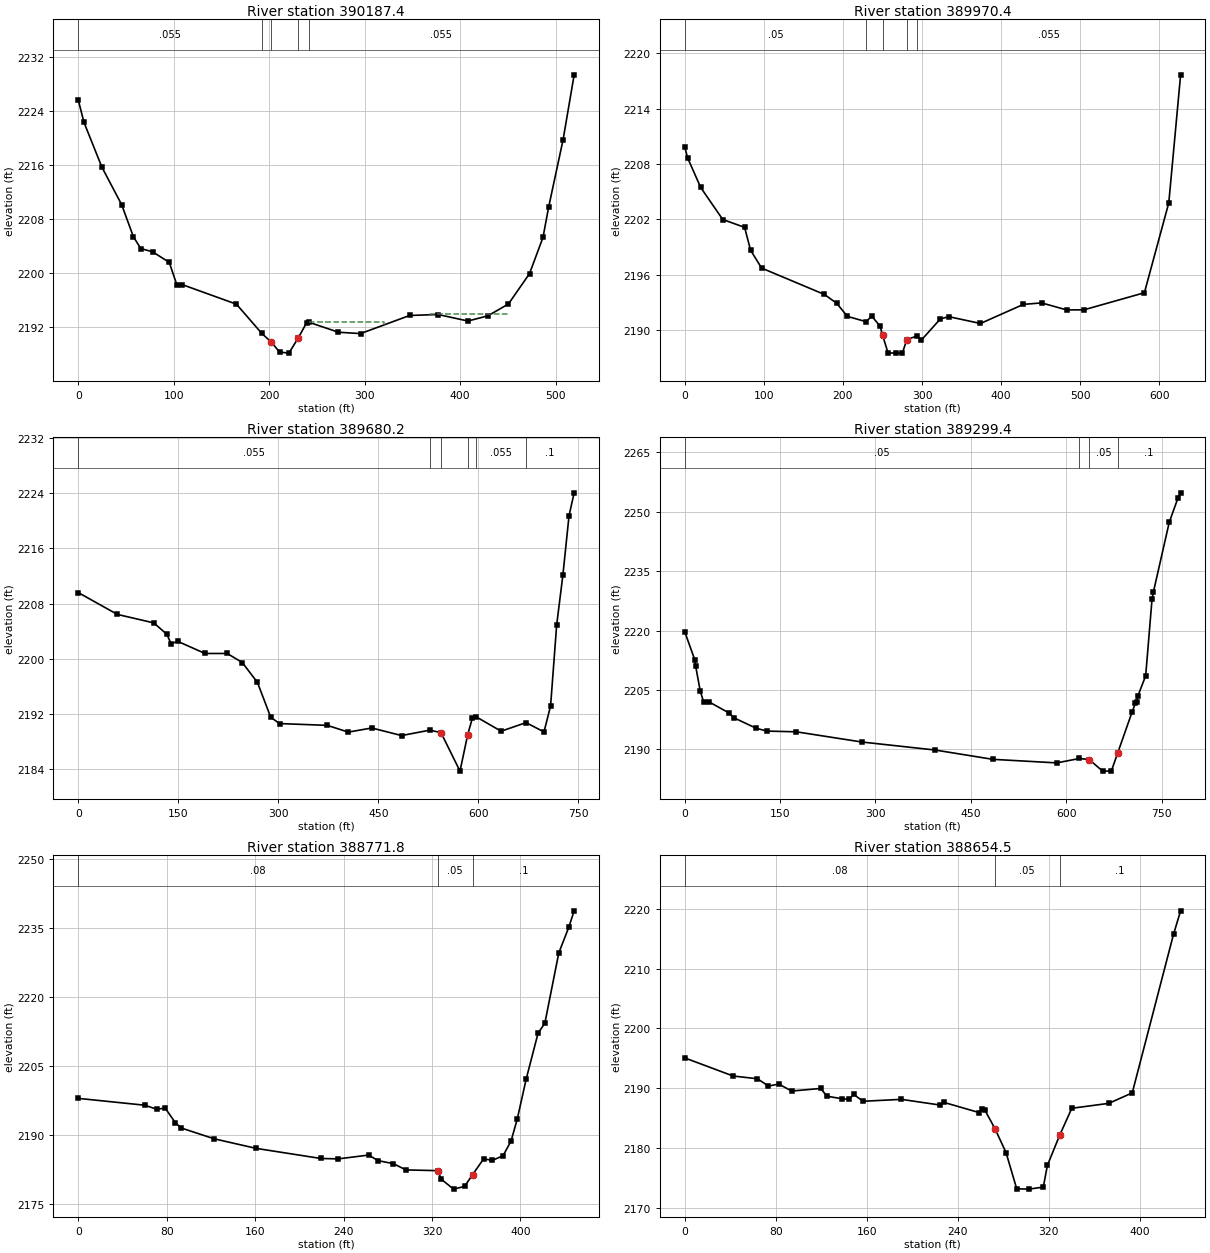
Type RM Length L Ch R = 1 ,390187.4,259.1,217.01,162.12
XS GIS Cut Line= 6
 1032193.9430049  663377.2976986 1032200.6803843   663299.817911
 1032140.0440301   663225.706798 1032045.7208393  663146.5426882
 1031973.2940787   663096.012388 1031840.2309639  663077.4846021
#Sta/Elev= 30
       0 2225.61    6.09 2222.26   24.81 2215.65   45.51  2210.1   57.76 2205.37
   65.52 2203.62   77.94 2203.13   95.37 2201.57  103.46 2198.17  108.76 2198.29
  165.68 2195.39  192.28 2191.06  202.35 2189.76  210.78 2188.31  220.56 2188.15
  230.25 2190.35  239.27 2192.67  241.35 2192.73  272.48 2191.24  295.65 2191.04
  347.07 2193.72  376.88 2193.86  408.08  2192.9  428.94 2193.66  450.53 2195.42
  472.59 2199.91  486.71 2205.27  492.69  2209.8  507.76 2219.72  519.33 2229.31
#Mann= 5 ,-1 , 0
       0    .055       0  192.28     .08       0  202.35     .05       0
  230.25     .08       0  241.35    .055       0
#XS Ineff= 2 ,-1
  241.35     320 2192.73  368.68     450 2193.91
Permanent Ineff=
       F       F
Bank Sta=202.35,230.25
Exp/Cntr=0.3,0.1

Type RM Length L Ch R = 1 ,389970.4,409.17,290.24,297.77
XS GIS Cut Line= 5
 1032434.8040693  663165.0704437 1032288.2662259  663021.9013052
 1032165.3091953  663018.5326003 1032065.9329473  663020.2169528
 1031899.1829657  662910.7346508
#Sta/Elev= 30
       0 2209.85    3.74 2208.65   20.16 2205.46   48.12 2201.98   75.73 2201.13
   83.29 2198.65   97.25 2196.72  176.67 2193.86  192.07 2192.91  205.66 2191.49
  229.08 2190.92  236.54 2191.51  246.99 2190.42  250.02 2189.47  256.95 2187.54
  266.52 2187.51  275.05 2187.51  280.78 2188.98  293.46 2189.36   299.2 2188.93
  323.05 2191.21  333.73 2191.46  373.78 2190.72  428.08 2192.79  451.09 2192.95
  482.63 2192.19   504.6  2192.2  580.98 2194.05  611.79 2203.79  626.74 2217.65
#Mann= 5 ,-1 , 0
       0     .05       0  229.08     .08       0  250.02     .05       0
  280.78     .08       0  293.46    .055       0
#XS Ineff= 3 ,-1
     200  236.54 2191.51  333.73     400 2191.46  451.09     550 2192.95
Permanent Ineff=
       F       F       F
Bank Sta=250.02,280.78
Exp/Cntr=0.3,0.1

Type RM Length L Ch R = 1 ,389680.2,191.63,380.81,426.15
XS GIS Cut Line= 5
  1032601.554051  662988.2144384 1032609.9757525  662892.2068649
 1032545.9707237  662759.1437804 1032185.5213033   662742.300347
 1032062.5642425  662678.2953182
#Sta/Elev= 30
       0 2209.59   58.63 2206.42  113.28 2205.19  132.63 2203.56  139.24 2202.19
  149.37  2202.5  190.17 2200.75  223.36 2200.75  245.97 2199.44  268.69 2196.55
  288.62 2191.49  301.95 2190.58  373.48 2190.32  404.83 2189.34   440.1 2189.94
  484.79 2188.84  526.71 2189.62  543.79 2189.28  572.35 2183.68  583.93 2188.98
  590.77 2191.33  596.73 2191.55  634.05 2189.47  671.33 2190.72  698.28 2189.37
  708.17 2193.15  717.29  2204.9  726.62 2212.14  735.84 2220.76  743.49 2224.06
#Mann= 6 ,-1 , 0
       0    .055       0  526.71     .08       0  543.79     .05       0
  583.93     .08       0  596.73    .055       0  671.33      .1       0
#XS Ineff= 2 , 0
       0                  596.73       0 2191.55
Permanent Ineff=
       F       F
Bank Sta=543.79,583.93
Exp/Cntr=0.3,0.1

Type RM Length L Ch R = 1 ,389299.4,421.73,527.57,558.69
XS GIS Cut Line= 6
 1032896.3140902  662759.1437804 1032748.0918943  662765.8811295
 1032609.4665241     662581.9077 1032403.7217014  662433.6111358
 1032359.6335468  662382.8429293 1032335.4278213  662311.1085184
#Sta/Elev= 30
       0 2219.75   16.19 2212.46   17.19 2211.09   24.55 2204.65   29.67 2202.08
   37.83 2202.02   69.31 2199.23    77.5 2197.96  112.45 2195.33  129.32 2194.61
  175.45 2194.43  278.79 2191.85  393.82 2189.83  484.53 2187.48  585.03 2186.58
  620.83 2187.69  636.09 2187.43  657.38  2184.5  671.04 2184.53   680.9 2189.04
  703.45 2199.34  708.98 2201.71  710.86 2202.05  712.52  2203.4     725 2208.56
  734.97 2227.89  737.02 2229.64  762.01  2247.3  775.82 2253.49  779.96 2254.78
#Mann= 4 ,-1 , 0
       0     .05       0  620.83     .08       0  636.09     .05       0
   680.9      .1       0
Bank Sta=636.09,680.9
Exp/Cntr=0.3,0.1

Type RM Length L Ch R = 1 ,388771.8,41.73,117.35,165.7
XS GIS Cut Line= 6
 1032866.4794894  662380.4067203 1032831.8293442  662273.0186596
 1032822.6756721  662189.4913603 1032798.0859671  662116.6030736
 1032783.8743041  662078.4092746 1032715.4807817  661963.8278778
#Sta/Elev= 30
       0 2197.95    60.2 2196.46   71.32 2195.56   78.58 2195.87   87.98 2192.62
   93.25  2191.5  123.14 2189.14   160.9 2187.07  219.45 2184.87  235.14 2184.78
  262.63 2185.61  271.43 2184.39  285.19 2183.74  296.45 2182.38  325.37 2182.22
  328.36 2180.37  339.59  2178.2  349.55 2178.79  356.73 2181.35   366.8 2184.79
  374.79 2184.46  384.36 2185.47  391.63 2188.69  397.28 2193.54  405.27 2202.16
  416.01 2212.14  422.14  2214.3  434.78 2229.61  443.78 2235.17  448.66 2238.76
#Mann= 3 , 0 , 0
       0     .08       0  325.37     .05       0  356.73      .1       0
Bank Sta=325.37,356.73
Exp/Cntr=0.5,0.3

Type RM Length L Ch R = 1 ,388654.5,29.86,27.95,37.95
XS GIS Cut Line= 6
 1032862.7229912  662297.0470753 1032862.7229912   662213.519776
 1032868.4440628  662081.9356757 1032868.4440628  661918.3137382
 1032863.8672116  661911.4484765 1032822.6756721  661885.1316504
#Sta/Elev= 30
       0 2195.08   42.58 2192.05   64.01 2191.59   73.63 2190.37   82.77  2190.7
   94.02 2189.54  119.54 2189.97  125.07 2188.68  138.23 2188.25  144.29 2188.16
   148.7 2188.97   156.8 2187.83  190.53 2188.15  224.47  2187.2  228.18 2187.63
   258.7 2185.95  261.71 2186.54  264.09 2186.29  272.85 2183.24  282.55 2179.25
  291.93  2173.2   302.7 2173.15  315.32 2173.49  318.88  2177.1  329.64 2182.13
  340.37 2186.66  372.83 2187.48  393.51 2189.23  429.81 2215.74  436.04 2219.65
#Mann= 3 , 0 , 0
       0     .08       0  272.85     .05       0  329.64      .1       0
#XS Ineff= 2 , 0
       0  261.71  2186.1  340.37       0  2186.1
Permanent Ineff=
       F       F
Bank Sta=272.85,329.64
Exp/Cntr=0.5,0.3

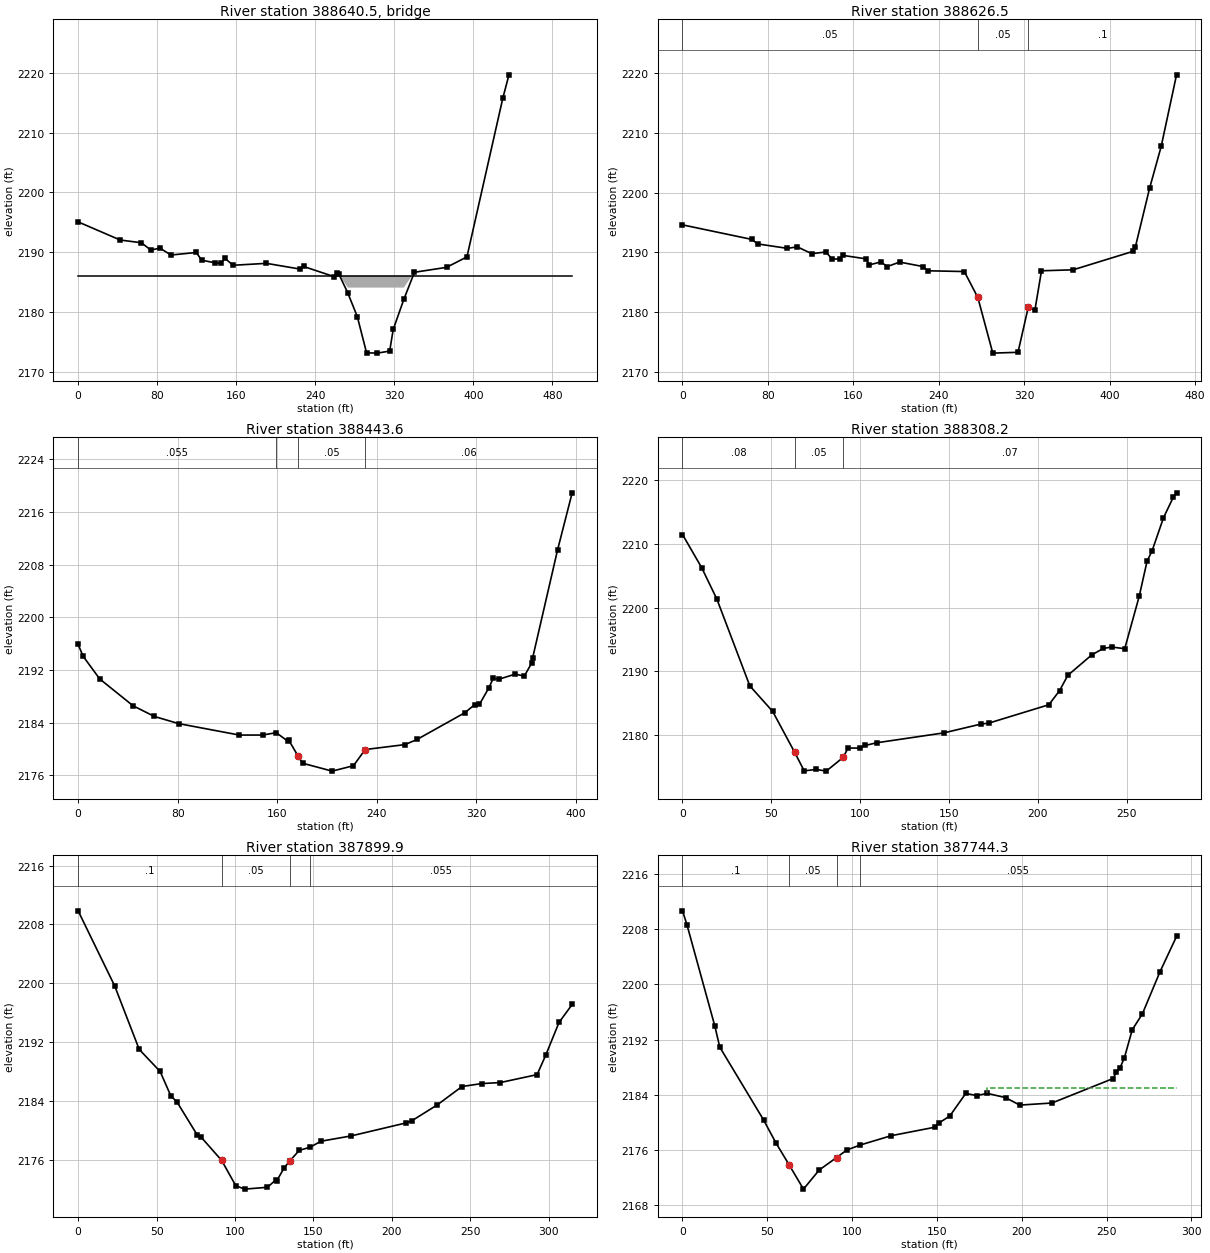
Type RM Length L Ch R = 3 ,388640.5,,,
BEGIN DESCRIPTION:
STR_156
END DESCRIPTION:
Bridge Culvert--1,0,-1,-1, 0
Deck Dist Width WeirC Skew NumUp NumDn MinLoCord MaxHiCord MaxSubmerge Is_Ogee
2,24,2.6,0, 4, 4, , , 0.95, 0, 0,0,,
       0  261.71  340.37     500
  2186.1  2186.1  2186.1  2186.1
          2184.1  2184.1
       0  261.71  340.37     500
  2186.1  2186.1  2186.1  2186.1
          2184.1  2184.1
BR Coef=-1 , 1 , 0 ,, 0 ,,,0.8,0,2,0,
WSPro=,,,, 1 ,,,, 0 ,,,, 0 ,,,,-1 ,-1 ,-1 , 0 , 0 , 0 , 0 , 0
BC Design=,, 0 ,, 0 ,,,,,,

Type RM Length L Ch R = 1 ,388626.5,292.65,182.93,127.1
XS GIS Cut Line= 6
 1032883.3187761  662289.0375933 1032890.1840377   662121.983025
 1032893.6166685  661937.7652724  1032895.905079  661903.4389946
 1032886.7514069  661883.9874301 1032840.9830163   661853.093783
#Sta/Elev= 30
       0 2194.61   64.88 2192.17   70.25 2191.42   98.17 2190.67  107.52 2190.92
  121.01 2189.78  134.41 2190.06  140.08 2188.85  147.93 2188.93  150.21 2189.49
  171.57 2188.92  174.96  2187.9  185.73 2188.39   191.8 2187.62   203.3 2188.37
  225.22 2187.62  229.78 2186.91  263.91 2186.78  276.55 2182.43  290.55  2173.1
  314.17 2173.24   323.8 2180.82  329.96 2180.27  336.17 2186.91  365.74 2187.07
  421.77 2190.16  424.06  2190.9  437.37 2200.74  448.25 2207.77  462.62 2219.77
#Mann= 3 , 0 , 0
       0     .05       0  276.55     .05       0   323.8      .1       0
#XS Ineff= 2 , 0
       0  261.71    2185  340.37       0    2185
Permanent Ineff=
       F       F
Bank Sta=276.55,323.8
Exp/Cntr=0.5,0.3

Type RM Length L Ch R = 1 ,388443.6,221.04,135.37,100.37
XS GIS Cut Line= 6
 1033152.2080181  662068.2051524 1033121.3143408  662040.7441362
 1033097.2859554  662010.9946793  1033043.508113  661870.2569371
  1032973.711337  661794.7390895 1032925.6545359    661753.54755
#Sta/Elev= 30
       0 2195.89    3.99  2194.1   17.34 2190.65   44.15 2186.57   61.37 2184.94
   80.75 2183.86  129.57 2182.12  148.25 2182.12  159.21 2182.48  168.45  2181.2
  169.12  2181.4  176.77 2178.92  180.46 2177.84  204.14 2176.64  221.26 2177.46
  230.72 2179.92  262.72 2180.67  272.45 2181.46  310.86 2185.52  318.73 2186.75
  322.54 2186.79  329.97 2189.25  333.59 2190.73  338.35 2190.61  351.26 2191.38
  358.54 2191.07  364.73 2193.13  365.21 2193.79   385.3 2210.25  397.03 2218.92
#Mann= 4 ,-1 , 0
       0    .055       0  159.21     .08       0  176.77     .05       0
  230.72     .06       0
Bank Sta=176.77,230.72
Exp/Cntr=0.3,0.1

Type RM Length L Ch R = 1 ,388308.2,409.9,408.33,408.73
XS GIS Cut Line= 5
 1033227.4816334  661835.9439166 1033168.4977594  661820.3305133
 1033137.2710133  661802.9823311 1033000.2202437  661686.7493923
 1033000.2202437  661685.0145831
#Sta/Elev= 30
       0 2211.44   10.85 2206.22   19.41 2201.28    37.9 2187.73   50.78 2183.72
   63.11 2177.34   68.53 2174.41   75.29 2174.64   80.92 2174.37   90.47 2176.52
    93.2 2177.98    99.9 2177.99  102.87 2178.39  109.29 2178.81  147.14 2180.36
     168 2181.74  172.47 2181.89  206.28 2184.77  212.34 2186.99  216.94 2189.37
  230.43 2192.58  236.94 2193.59  241.73 2193.81  248.99 2193.55  257.13 2201.73
  261.61  2207.3  264.35 2208.84  270.82 2214.06  276.44 2217.34  278.17 2217.97
#Mann= 3 , 0 , 0
       0     .08       0   63.11     .05       0   90.47     .07       0
Bank Sta=63.11,90.47
Exp/Cntr=0.3,0.1

Type RM Length L Ch R = 1 ,387899.9,174.1,155.55,111.74
XS GIS Cut Line= 6
 1033490.7712995  661557.7693368 1033457.3711612   661537.729272
 1033415.9550031   661505.665132 1033373.2028164  661460.2409489
 1033311.7465935  661413.4807674 1033234.2582703  661384.0886542
#Sta/Elev= 30
       0 2209.86   23.29 2199.64   38.95 2190.99   52.26 2187.99   59.03  2184.7
   63.15 2183.79   75.96 2179.33   78.61    2179   91.48 2175.88  100.47 2172.44
  106.15 2171.97   120.6 2172.22  125.92 2173.19  126.67 2173.12  131.41 2174.89
  134.75 2175.77  140.98 2177.25  147.93 2177.68  154.74 2178.49  174.17 2179.22
  209.14 2180.99  212.81 2181.29  228.93 2183.44  244.69 2185.94  257.15 2186.34
  269.12 2186.48  292.56 2187.56  298.12 2190.24  306.52 2194.66   314.9 2197.11
#Mann= 4 ,-1 , 0
       0      .1       0   91.48     .05       0  134.75     .08       0
  147.93    .055       0
Bank Sta=91.48,134.75
Exp/Cntr=0.3,0.1

Type RM Length L Ch R = 1 ,387744.3,48.34,48.73,66.96
XS GIS Cut Line= 5
 1033534.2059382  661371.8931109 1033475.6557741  661349.9368107
 1033440.5256696  661345.5455628 1033405.3955651  661341.8861643
 1033270.7301543  661259.1840306
#Sta/Elev= 30
       0 2210.63    2.68 2208.57   19.06 2193.96   21.97 2190.91   47.79 2180.38
   55.15 2177.02   63.01 2173.82   71.33 2170.36   80.62 2173.13   90.85 2174.93
   96.87 2176.02  104.62 2176.73  123.02 2178.09  148.59 2179.31  151.11 2179.92
  157.56 2180.93  167.03 2184.21  173.38  2183.9  179.83 2184.21  190.49  2183.6
  198.84 2182.52  217.81 2182.82  253.86 2186.36  255.72 2187.24  257.89 2187.87
  260.53 2189.36   265.2 2193.43  271.15 2195.72  281.55 2201.82  291.29 2206.92
#Mann= 4 ,-1 , 0
       0      .1       0   63.01     .05       0   90.85     .08       0
  104.62    .055       0
#XS Ineff= 2 , 0
       0                  179.61       0    2185
Permanent Ineff=
       F       F
Bank Sta=63.01,90.85
Exp/Cntr=0.5,0.3

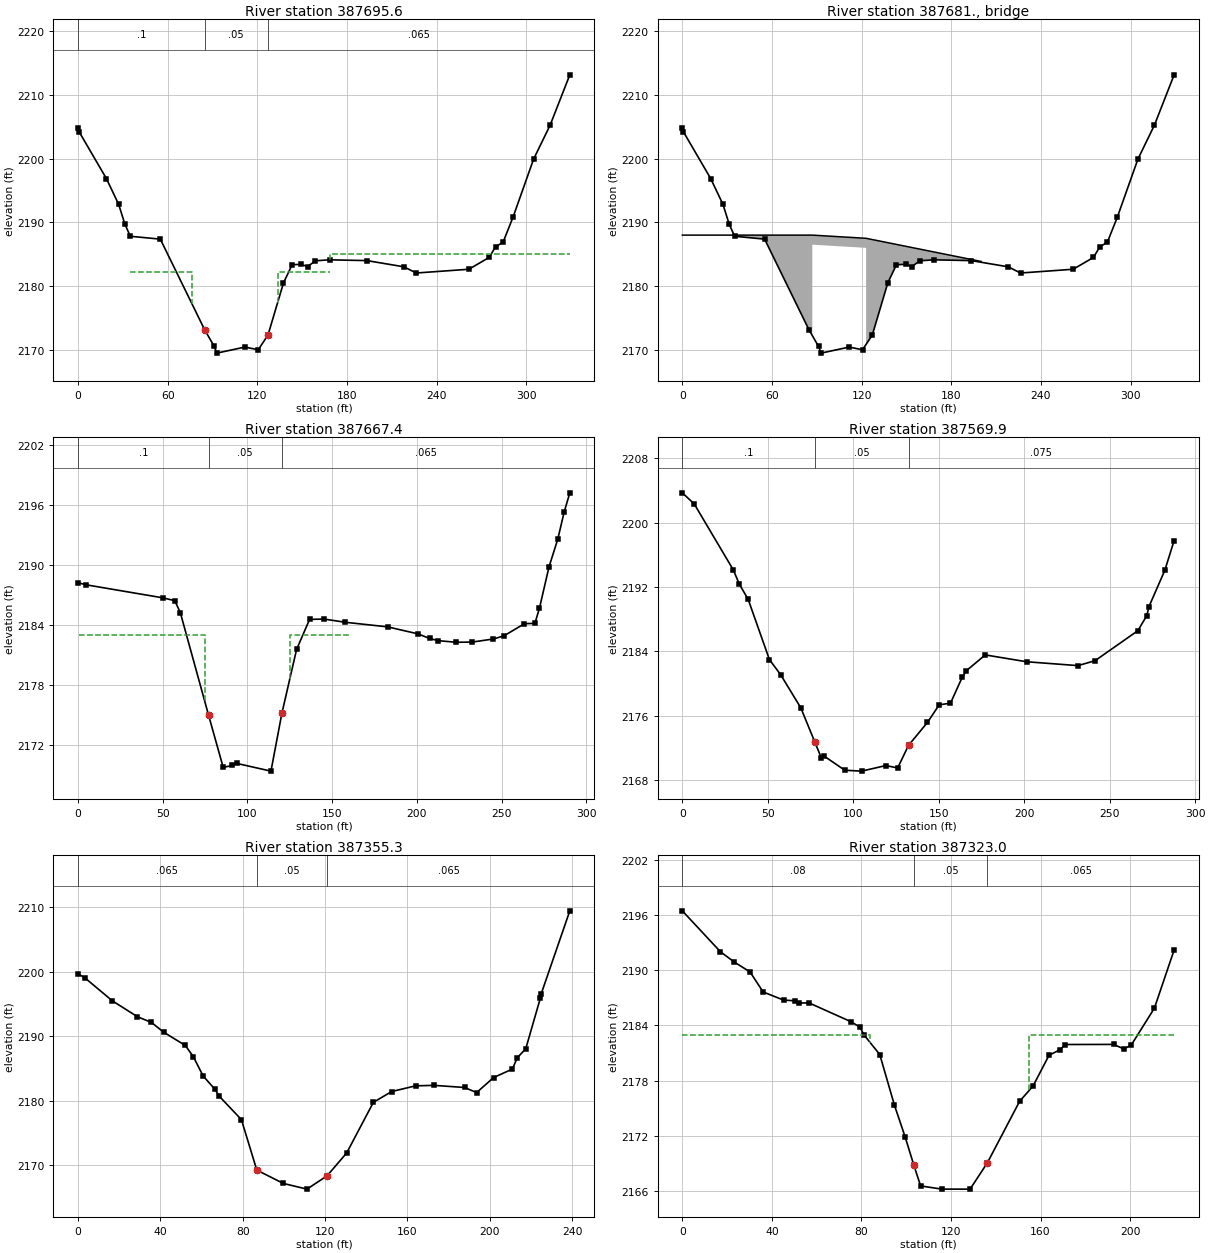
Type RM Length L Ch R = 1 ,387695.6,31.74,28.23,32.15
XS GIS Cut Line= 6
 1033562.7491557  661357.9874572 1033553.6765716  661328.0431047
  1033508.451703  661311.5324374 1033447.2763367  661291.5327804
 1033316.1065444  661261.3796697 1033273.6576731  661233.5683319
#Sta/Elev= 30
       0 2204.88      .7 2204.24   18.97 2196.89   27.25 2192.81   31.29 2189.77
   34.98 2187.82   55.09 2187.37   84.69 2173.17   91.18 2170.52   92.87 2169.47
  111.67 2170.42   120.6    2170  127.15 2172.31  137.52  2180.5   143.3 2183.35
  149.51 2183.41   153.6 2183.05  158.92 2183.97  168.31 2184.12  193.34    2184
  218.18 2183.02  226.33 2182.05  261.57 2182.64  275.13 2184.49  279.42 2186.16
  284.48 2186.89  291.18 2190.85   304.9 2199.93  315.98 2205.28  329.14 2213.17
#Mann= 3 , 0 , 0
       0      .1       0   84.69     .05       0  127.15    .065       0
#XS Ineff= 3 ,-1
   34.92   76.44  2182.2  133.53   168.4  2182.2   168.4  329.14    2185
Permanent Ineff=
       T       T       F
Bank Sta=84.69,127.15
Exp/Cntr=0.5,0.3

Type RM Length L Ch R = 3 ,387681. ,,,
BEGIN DESCRIPTION:
STR_155
END DESCRIPTION:
Bridge Culvert--1,0,-1,-1, 0
Deck Dist Width WeirC Skew NumUp NumDn MinLoCord MaxHiCord MaxSubmerge Is_Ogee
2,26,2.6,0, 4, 4, , , 0.95, 0, 0,0,,
       0      87     123     200
    2188    2188  2187.52183.866
          2186.5    2186
       0      80     116   197.4
    2188    2188  2187.5 2183.24
          2186.5    2186
BR Coef=-1 , 1 , 0 ,, 0 ,,,0.8,0,2,0,
WSPro=,,,, 1 ,,,, 0 ,,,, 0 ,,,,-1 ,-1 ,-1 , 0 , 0 , 0 , 0 , 0
BC Design=,, 0 ,, 0 ,,,,,,

Type RM Length L Ch R = 1 ,387667.4,190.95,97.51,89.34
XS GIS Cut Line= 6
 1033580.2151409  661313.8853187 1033535.5100643  661289.1798992
 1033451.9821294  661264.4744494  1033366.101283  661243.2983366
 1033330.8077919  661239.7689996 1033307.2787979  661224.4751353
#Sta/Elev= 30
       0 2188.24    4.61 2188.03   50.15 2186.72    57.1 2186.44   60.41 2185.22
   77.02    2175   85.67 2169.77   90.97 2169.97   93.71 2170.17  113.85  2169.4
  120.29 2175.18  128.96 2181.56  136.64 2184.57   145.2  2184.6  157.73 2184.28
  182.74 2183.82   200.6 2183.12  207.47 2182.66   212.6 2182.44  223.25 2182.28
  232.54  2182.3  245.13 2182.61  251.41 2182.93   263.4 2184.14  269.57 2184.17
  272.22 2185.66  277.91 2189.82  283.09  2192.6   286.8 2195.27  290.18 2197.22
#Mann= 3 , 0 , 0
       0      .1       0   77.02     .05       0  120.29    .065       0
#XS Ineff= 2 ,-1
     .33      75    2183     125  160.64    2183
Permanent Ineff=
       F       F
Bank Sta=77.02,120.29
Exp/Cntr=0.5,0.3

Type RM Length L Ch R = 1 ,387569.9,200.79,214.55,206.67
XS GIS Cut Line= 6
 1033603.0023879  661132.5692965 1033547.3797426  661160.3806343
 1033501.4593462  661178.3438316 1033445.3471163  661179.6798298
 1033353.1627516  661187.6958497 1033329.1146618  661174.3358065
#Sta/Elev= 30
       0 2203.69    6.97 2202.31   29.79 2194.13   33.35 2192.35   38.55 2190.44
   50.96 2182.97   57.53 2181.09   69.31 2176.98    77.52172.738   81.32 2170.76
   82.93 2170.98   95.07 2169.22  104.91 2169.11  119.05  2169.8  126.01 2169.51
  132.34 2172.31  143.42 2175.16  150.28 2177.35  156.89 2177.55  163.72 2180.75
   166.2 2181.59  177.24 2183.55  201.42  2182.7  231.47 2182.22  241.45 2182.83
  266.51 2186.56  271.73 2188.43  273.03 2189.56   282.3 2194.07  287.73 2197.76
#Mann= 3 , 0 , 0
       0      .1       0    77.5     .05       0  132.34    .075       0
Bank Sta=77.5,132.34
Exp/Cntr=0.3,0.1

Type RM Length L Ch R = 1 ,387355.3,32.12,32.25,42.15
XS GIS Cut Line= 6
 1033595.6095554  660993.8541212 1033532.1015874  660963.4733045
 1033492.6421632  660963.9487236 1033478.3797408  660970.6045308
 1033415.0705123  660981.4317194 1033367.8653613  660972.3219359
#Sta/Elev= 30
       0 2199.65    3.32 2199.03    16.7 2195.46   28.87    2193   35.68 2192.12
   41.53 2190.62   52.12 2188.55   55.99 2186.82   60.79 2183.82   66.45 2181.78
   68.58 2180.69   79.37 2177.06   86.84 2169.24   99.74 2167.17  111.23 2166.29
  120.97 2168.35  130.51  2171.9  143.47 2179.74  152.35 2181.41  163.93 2182.29
  172.75 2182.37  187.74 2182.04  193.62 2181.25  201.86 2183.58  210.97 2184.89
  213.35 2186.64  217.48 2188.04  224.52 2195.83  224.97 2196.54  238.88 2209.41
#Mann= 3 , 0 , 0
       0    .065       0   86.84     .05       0  120.97    .065       0
Bank Sta=86.84,120.97
Exp/Cntr=0.5,0.3

Type RM Length L Ch R = 1 ,387323.0,16.06,15.5,20.04
XS GIS Cut Line= 6
 1033608.8601193  660941.6799974 1033569.1083973  660920.1478121
 1033540.6590408  660929.7188493 1033512.6095848   660932.571364
  1033453.182739  660932.0959449 1033396.6084079  660927.8172031
#Sta/Elev= 30
       0 2196.46   16.99 2192.02   23.28 2190.88   30.24 2189.82   36.11 2187.64
   45.21 2186.76   50.27 2186.68   52.01 2186.43   56.52 2186.46   75.22 2184.42
   79.33 2183.82   81.15 2182.97   88.19 2180.84   94.75 2175.33   99.47 2171.92
  103.42 2168.81  106.43 2166.56  115.89 2166.21  128.54 2166.21  136.29 2169.09
  150.64 2175.75  156.65 2177.42   163.8 2180.76  168.69 2181.36  171.07 2181.93
  192.65 2181.94  197.29 2181.44  200.59  2181.9  210.85 2185.88  219.66  2192.2
#Mann= 3 , 0 , 0
       0     .08       0  103.42     .05       0  136.29    .065       0
#XS Ineff= 2 , 0
       0      84    2183     155       0    2183
Permanent Ineff=
       F       F
Bank Sta=103.42,136.29
Exp/Cntr=0.5,0.3

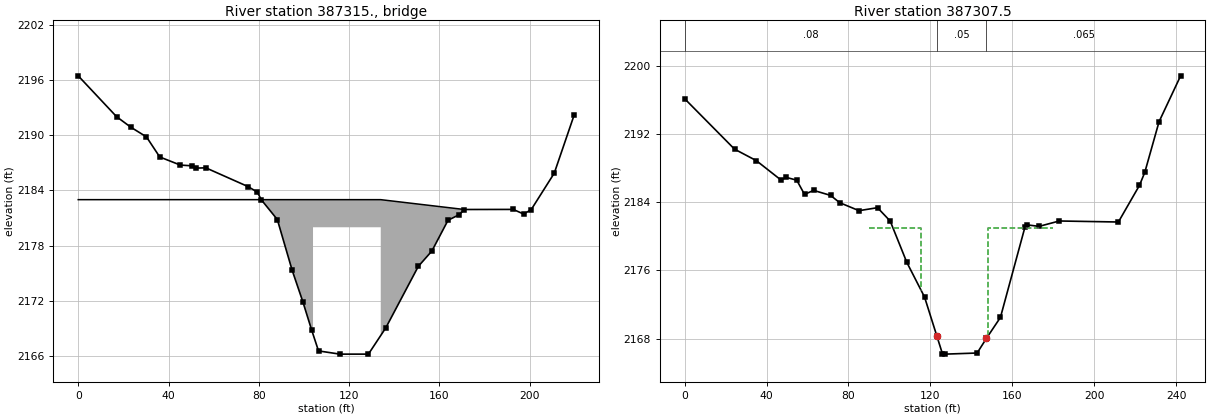
Type RM Length L Ch R = 3 ,387315. ,,,
BEGIN DESCRIPTION:
STR_154
END DESCRIPTION:
Bridge Culvert--1,0,-1,-1, 0
Deck Dist Width WeirC Skew NumUp NumDn MinLoCord MaxHiCord MaxSubmerge Is_Ogee
1.5,12,2.6,0, 4, 4, 2183, , 0.95, 0, 0,0,,
       0     104     134  171.07
    2183    2183    2183 2181.93
            2180    2180
       0     116     148  171.08
    2183    2183    21832181.229
            2180    2180
BR Coef=-1 , 1 , 0 ,, 0 ,,,0.8,0,2,0,
WSPro=,,,, 1 ,,,, 0 ,,,, 0 ,,,,-1 ,-1 ,-1 , 0 , 0 , 0 , 0 , 0
BC Design=,, 0 ,, 0 ,,,,,,

Type RM Length L Ch R = 1 ,387307.5,41.25,37.66,44.44
XS GIS Cut Line= 6
 1033621.2825211  660921.8041363 1033579.5398321  660900.3841847
 1033522.1178765  660916.4072651 1033481.2322253  660916.4072651
  1033429.887444  660909.2760388 1033386.9130601  660909.3817346
#Sta/Elev= 30
       0 2196.14   24.34 2190.23      35 2188.88   46.92 2186.63   49.65 2186.91
   54.73 2186.59   58.53 2184.92   62.99 2185.39   71.29  2184.8   75.69 2183.95
   85.15 2183.01   94.19 2183.36  100.39 2181.79  108.51 2176.94  117.16 2172.88
  123.23 2168.26  125.89 2166.23  127.24 2166.18  142.85 2166.31  147.42 2168.04
  154.23 2170.49   166.2 2181.08  167.02 2181.35  173.14 2181.17  182.98  2181.8
  211.85 2181.68  222.14 2185.98  224.73  2187.5  231.71 2193.45  242.24 2198.83
#Mann= 3 , 0 , 0
       0     .08       0  123.23     .05       0  147.42    .065       0
#XS Ineff= 2 ,-1
      90  115.66    2181  148.12     180    2181
Permanent Ineff=
       T       T
Bank Sta=123.23,147.42
Exp/Cntr=0.5,0.3