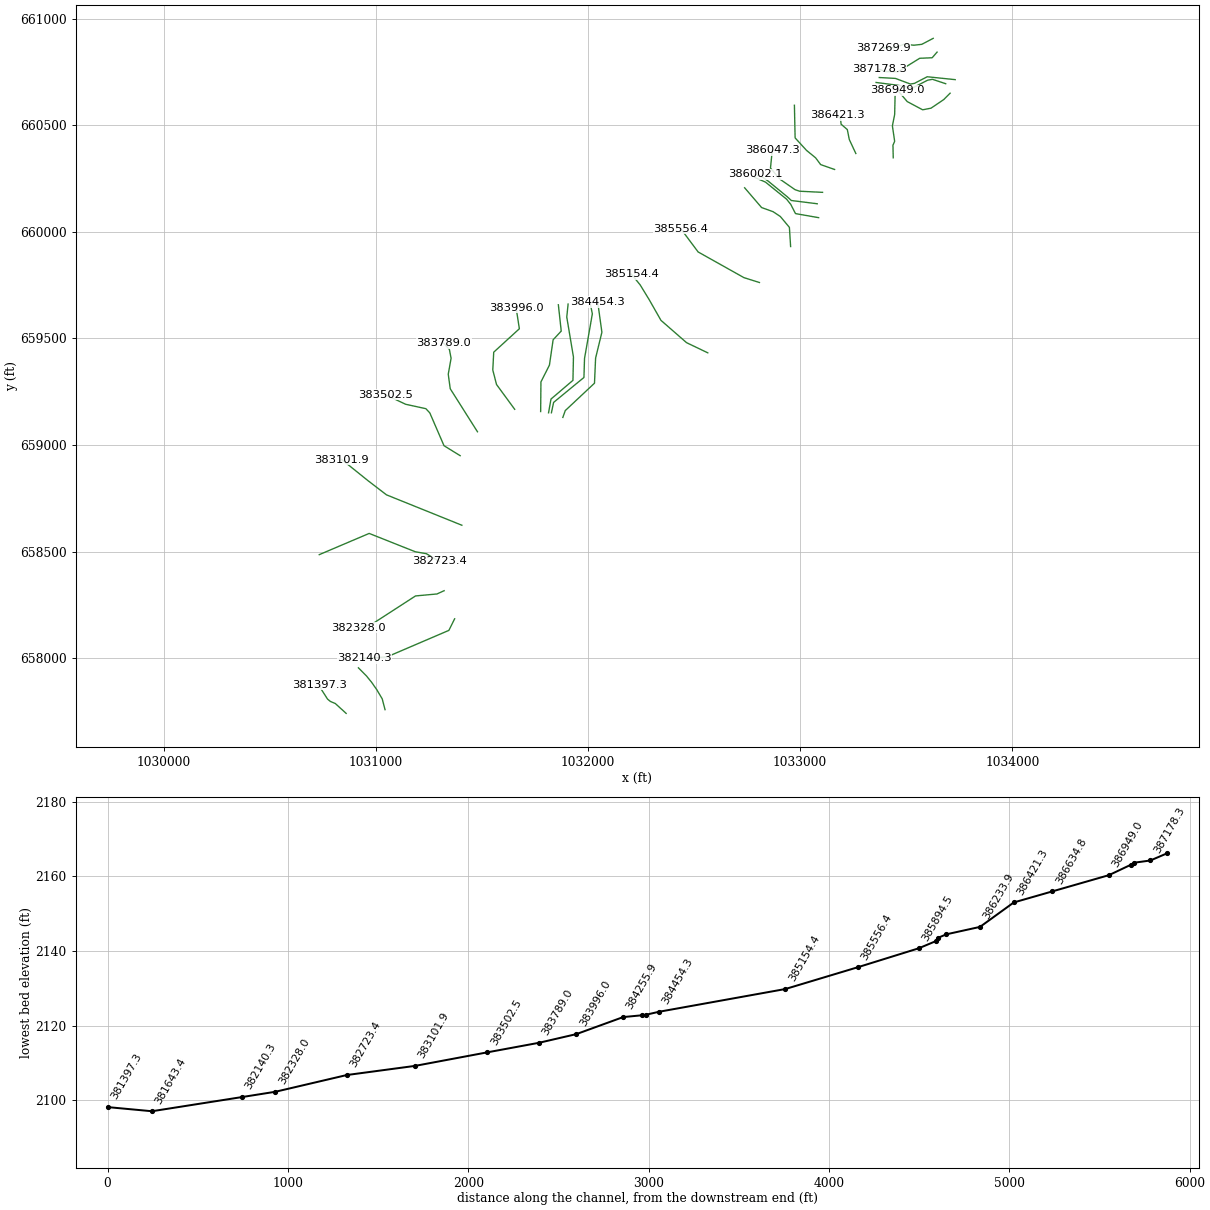
HEC-RAS study lds_broad_rvr.prj: Upper_Broad 3-06-07

--- lds_broad_rvr.g05 (geometry) --- (continued)

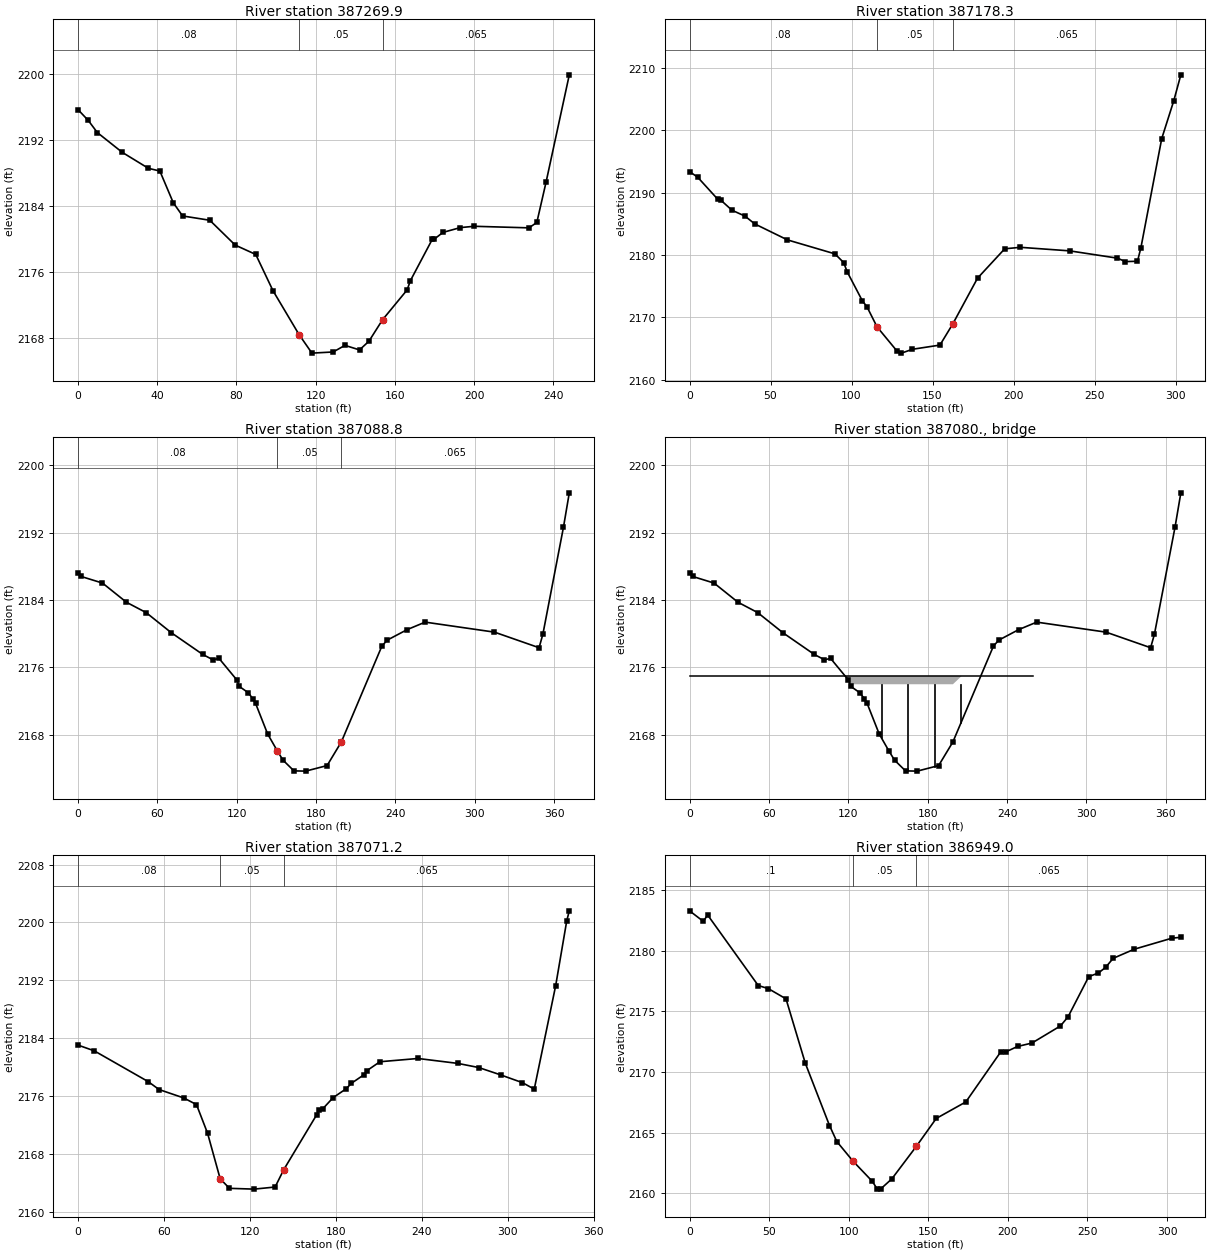
Type RM Length L Ch R = 1 ,387269.9,68.66,91.62,104.15
XS GIS Cut Line= 6
 1033627.0796561  660907.7254103  1033573.249208  660879.5679582
 1033535.9049101  660875.5215836 1033488.8388405  660879.8003254
 1033445.1007047  660863.6362265 1033391.0538708  660863.8329078
#Sta/Elev= 30
       0 2195.66    5.18 2194.35    9.77 2192.88   22.31 2190.49   35.55 2188.55
   41.35 2188.22   48.14 2184.37   52.84 2182.78   66.56 2182.26    79.4 2179.25
   89.77 2178.12   98.47 2173.73  111.65 2168.41  118.14 2166.17  128.86 2166.31
  134.81 2167.11  142.17 2166.56  146.92 2167.61  153.79 2170.21  166.19 2173.82
  167.87 2174.95  178.93 2179.96  179.79 2179.95   184.3 2180.79  193.07 2181.37
  200.03 2181.53  227.73 2181.34   231.7 2181.99  236.39  2186.9   248.1 2199.87
#Mann= 3 , 0 , 0
       0     .08       0  111.65     .05       0  153.79    .065       0
Bank Sta=111.65,153.79
Exp/Cntr=0.3,0.1

Type RM Length L Ch R = 1 ,387178.3,101.19,89.51,82.3
XS GIS Cut Line= 6
 1033645.2991928  660843.1288847 1033622.1106833  660816.6277266
 1033563.3112926  660814.1432704 1033461.4475314  660751.2030388
 1033401.8199483   660752.031201 1033373.6624962  660761.9691466
#Sta/Elev= 30
       0  2193.4    4.99 2192.51   17.53 2188.93   19.22 2188.84    26.2  2187.2
   34.23 2186.26   40.23 2185.01   60.45 2182.44   89.75  2180.2   95.12 2178.81
   97.36  2177.3  106.74 2172.64  109.47 2171.74  115.76 2168.48  127.93 2164.65
   130.8 2164.27  137.63 2164.89  154.58 2165.56  162.52 2168.96  177.79  2176.3
  194.56 2181.01  204.22 2181.25  234.69 2180.68  264.17 2179.51  269.03 2178.96
  276.53 2179.01  278.64 2181.18   291.5  2198.7  298.86 2204.71   303.3 2208.93
#Mann= 3 , 0 , 0
       0     .08       0  115.76     .05       0  162.52    .065       0
Bank Sta=115.76,162.52
Exp/Cntr=0.5,0.3

Type RM Length L Ch R = 1 ,387088.8,14.98,17.54,19.94
XS GIS Cut Line= 6
 1033730.5997416  660713.9358335 1033598.8247108  660727.4788769
 1033538.8688413   660696.644434 1033520.0255723  660693.2183713
 1033449.0250993  660719.7329382 1033372.8343341  660723.8737488
#Sta/Elev= 30
       0 2187.26    2.27 2186.81   18.53 2186.02   36.65 2183.74   51.55 2182.51
   70.58 2180.12   94.33 2177.54  101.99 2176.91  106.63 2177.07  119.99 2174.53
  121.97 2173.74  128.75 2172.99  132.26 2172.26  134.22 2171.74  143.36  2168.1
  150.74 2166.07  155.01 2164.98  163.28 2163.71  172.12 2163.68  188.31 2164.34
   199.1 2167.15  229.76 2178.54  233.78 2179.24  248.84 2180.49  262.46 2181.38
  314.86 2180.19  348.57 2178.34  351.44 2179.94  366.98 2192.63  371.42 2196.74
#Mann= 3 , 0 , 0
       0     .08       0  150.74     .05       0   199.1    .065       0
Bank Sta=150.74,199.1
Exp/Cntr=0.5,0.3

Type RM Length L Ch R = 3 ,387080. ,,,
BEGIN DESCRIPTION:
STR_153
END DESCRIPTION:
Bridge Culvert--1,0,-1,-1, 0
Deck Dist Width WeirC Skew NumUp NumDn MinLoCord MaxHiCord MaxSubmerge Is_Ogee
2,12,2.6,0, 2, 2, 2175, , 0.95, 0, 0,0,,
       0     260
    2175    2175
    2174    2174
       0     260
    2175    2175
    2174    2174
Pier Skew, UpSta & Num, DnSta & Num=  ,145, 2 ,106, 2 , 0 , 0 , 0 ,,
       1       1
    2160    2174
       1       1
    2160    2174
Pier Skew, UpSta & Num, DnSta & Num=  ,165, 2 ,126, 2 , 0 , 0 , 0 ,,
       1       1
    2160    2174
       1       1
    2160    2174
Pier Skew, UpSta & Num, DnSta & Num=  ,185, 2 ,146, 2 , 0 , 0 , 0 ,,
       1       1
    2160    2174
       1       1
    2160    2174
Pier Skew, UpSta & Num, DnSta & Num=  ,205, 2 ,166, 2 , 0 , 0 , 0 ,,
       1       1
    2160    2174
       1       1
    2160    2174
BR Coef=-1 , 1 , 0 ,, 0 ,,,0.8,0,2,0,
WSPro=,,,, 1 ,,,, 0 ,,,, 0 ,,,,-1 ,-1 ,-1 , 0 , 0 , 0 , 0 , 0
BC Design=,, 0 ,, 0 ,,,,,,

Type RM Length L Ch R = 1 ,387071.2,118.36,122.23,79.06
XS GIS Cut Line= 6
 1033685.8790467  660694.8881346 1033623.6635819   660715.487703
  1033600.537727  660711.2051473 1033528.5907138  660674.3751024
 1033461.4475314  660687.4346754 1033357.9274459  660700.6852393
#Sta/Elev= 30
       0 2183.05   11.33 2182.26   49.04    2178   56.59 2176.91   73.78 2175.75
   82.72 2174.83   90.46 2170.87   99.25 2164.58  105.74 2163.26  122.96 2163.15
  137.59 2163.44  143.66 2165.85  166.67 2173.44  168.13 2174.08  170.69 2174.21
  178.09 2175.79  187.17 2177.01  190.91 2177.78  199.51 2178.94  201.78 2179.53
  210.76 2180.75  237.34  2181.2  265.17 2180.52  279.72 2179.95  294.93 2178.94
  310.23 2177.86  318.49 2176.97  333.46 2191.28  341.17 2200.22  342.95  2201.6
#Mann= 3 , 0 , 0
       0     .08       0   99.25     .05       0  143.66    .065       0
Bank Sta=99.25,143.66
Exp/Cntr=0.5,0.3

Type RM Length L Ch R = 1 ,386949.0,421.12,314.21,145.31
XS GIS Cut Line= 6
  1033706.745276  660650.3927546 1033676.7673261  660620.4148349
 1033616.8114868  660580.1587576 1033577.4119024  660572.4501393
  1033504.608366  660610.9932005 1033458.3566866  660664.9534679
#Sta/Elev= 30
       0 2183.27    8.68  2182.4   11.36 2182.93   43.15 2177.12   49.56 2176.86
   60.61 2176.02   72.73 2170.72   87.93 2165.59   92.54 2164.27  102.61 2162.67
  114.84 2160.99  117.97 2160.35  120.06 2160.36  127.13  2161.2  142.48 2163.87
  154.99 2166.17  173.58 2167.53  195.61 2171.67  198.67 2171.65  206.07  2172.1
  215.11 2172.38  233.03 2173.79  237.81 2174.54  250.82 2177.85  256.89 2178.15
  261.37 2178.61  266.17 2179.36  279.43 2180.11  303.15 2181.02  308.68 2181.09
#Mann= 3 , 0 , 0
       0      .1       0  102.61     .05       0  142.48    .065       0
Bank Sta=102.61,142.48
Exp/Cntr=0.3,0.1

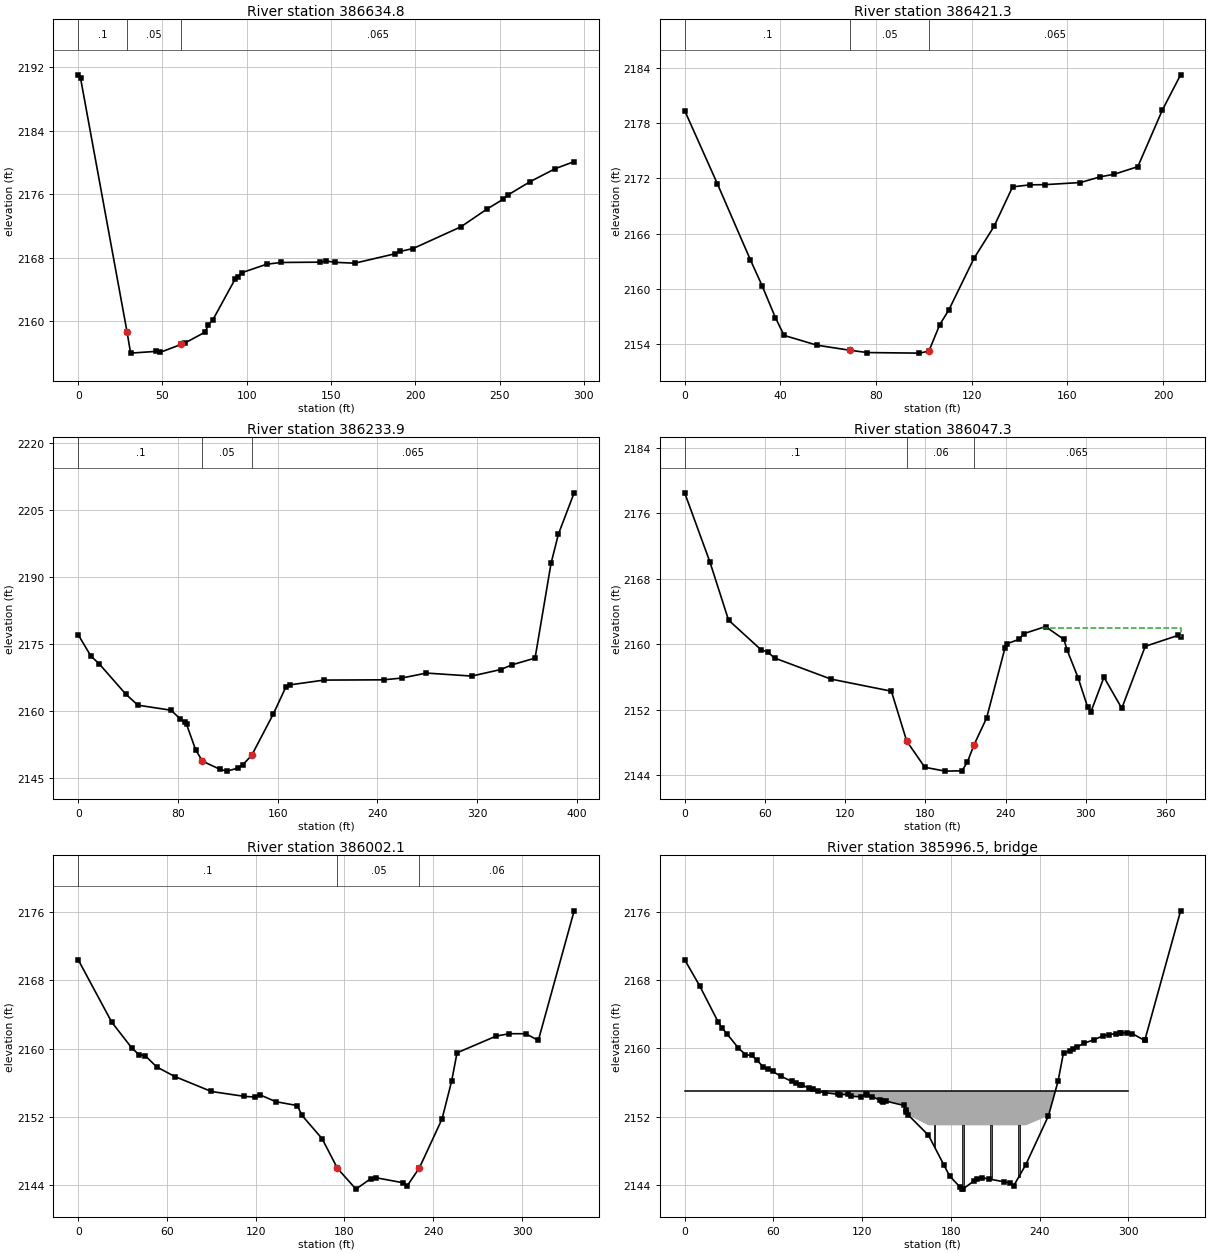
Type RM Length L Ch R = 1 ,386634.8,212.29,213.54,231.39
XS GIS Cut Line= 6
 1033438.6670947  660347.3484909 1033437.3310964  660406.1327476
 1033445.3471163  660424.8368141 1033434.6590696   660496.981114
 1033445.3471163   660550.421317 1033447.3687751   660637.745038
#Sta/Elev= 30
       0 2191.05    1.38 2190.64      29 2158.63   31.08 2155.99   46.13 2156.21
   48.66 2156.09   61.05 2157.09   63.12 2157.25   75.35 2158.64   77.13 2159.54
    79.8 2160.16   93.21 2165.36    94.5 2165.53   97.03 2166.12  111.81 2167.19
  120.19 2167.41  143.73 2167.45  147.05  2167.6  152.16 2167.43  164.06 2167.32
  187.82  2168.5     191  2168.8  198.71 2169.17  227.08 2171.91  242.43 2174.13
  252.11 2175.38   255.2 2175.95  268.27 2177.61  282.91 2179.22  294.21 2180.12
#Mann= 3 , 0 , 0
       0      .1       0      29     .05       0   61.05    .065       0
Bank Sta=29,61.05
Exp/Cntr=0.3,0.1

Type RM Length L Ch R = 1 ,386421.3,177.15,187.32,211.86
XS GIS Cut Line= 6
 1033262.3143853   660367.388586 1033231.5862738   660432.852834
 1033222.2342254  660479.6130154 1033192.8421122  660504.9971338
 1033190.1700854   660530.381222 1033175.4740439   660546.413292
#Sta/Elev= 24
       0 2179.33   13.66  2171.4   27.51 2163.12    32.4 2160.32   37.94 2156.87
   41.57 2154.95   55.31 2153.89   69.08 2153.34   76.36 2153.09   98.11 2153.03
  102.08 2153.24  106.62 2156.11  110.46 2157.73  120.96 2163.32  129.34 2166.78
  137.08 2171.06  144.39 2171.28  150.58  2171.3  165.46 2171.53  173.72 2172.15
  179.43 2172.42  189.43 2173.25  199.74 2179.42  207.32 2183.21
#Mann= 3 , 0 , 0
       0      .1       0   69.08     .05       0  102.08    .065       0
Bank Sta=69.08,102.08
Exp/Cntr=0.3,0.1

Type RM Length L Ch R = 1 ,386233.9,170.92,186.6,187.89
XS GIS Cut Line= 6
 1033162.1139705  660292.5722896 1033096.6497225  660315.2843812
 1033072.6016326  660347.3484909  1033029.849446  660382.0846275
 1032976.1453667  660440.6428126 1032972.8327181  660593.8525355
#Sta/Elev= 30
       0 2177.03   10.18 2172.24   16.82 2170.51   38.08 2163.74   47.88 2161.25
   74.46 2160.12   81.86 2158.15   85.45 2157.51   86.85 2156.99   94.14 2151.28
   99.61 2148.71  113.58  2146.9  119.21 2146.48     128 2147.15  131.94  2147.9
  139.08    2150  156.46 2159.28  166.62 2165.38     170 2165.81  197.14 2166.87
     245 2166.93  259.25 2167.32  279.22 2168.44  315.55 2167.77  338.79 2169.23
  347.99  2170.3  366.36 2171.79  379.17 2193.02  385.11 2199.59   397.7 2208.81
#Mann= 3 , 0 , 0
       0      .1       0   99.61     .05       0  139.08    .065       0
Bank Sta=99.61,139.08
Exp/Cntr=0.3,0.1

Type RM Length L Ch R = 1 ,386047.3,58.6,45.19,44.09
XS GIS Cut Line= 6
  1033105.519602  660185.2328696 1032997.7376642  660190.4403844
 1032975.9857031  660197.6910179 1032905.8960844  660246.0287058
 1032860.0217256  660298.8979337 1032868.4068331  660383.2150456
#Sta/Elev= 30
       0 2178.47   18.85 2170.04   32.81 2162.93    57.3 2159.28   61.96 2159.05
   67.26  2158.3  109.35 2155.73  154.61 2154.25  166.11 2148.15  179.62 2144.96
  194.84 2144.49  207.49 2144.53  211.53 2145.63  216.53 2147.73  225.83 2150.97
  239.63 2159.55   241.1 2160.05  250.21 2160.58  253.58 2161.27  269.95 2162.14
  283.65 2160.57  286.21 2159.22  294.25 2155.91  301.49 2152.27  303.91 2151.74
  313.63 2155.96  326.97 2152.16  344.52 2159.73  368.83 2161.05  370.98 2160.87
#Mann= 3 , 0 , 0
       0      .1       0  166.11     .06       0  216.53    .065       0
#XS Ineff= 2 , 0
       0                     267       0    2162
Permanent Ineff=
       F       F
Bank Sta=166.11,216.53
Exp/Cntr=0.5,0.3

Type RM Length L Ch R = 1 ,386002.1,25.94,11.4,12.18
XS GIS Cut Line= 6
 1033080.3642187   660131.661243 1032958.2618953  660146.9364622
 1032938.9268322    660164.66027 1032851.1133754  660236.3611743
 1032825.3332611  660254.8906248 1032787.4687475  660270.1975649
#Sta/Elev= 30
       0 2170.37   22.63 2163.09   36.24 2160.06   41.11 2159.27   45.28 2159.17
   52.97 2157.86   65.27 2156.73   90.02 2154.98  112.24 2154.41   119.3 2154.33
  122.55 2154.61  133.57 2153.79  148.14 2153.33  151.24 2152.19  164.81 2149.48
  175.252145.998  187.74 2143.57  197.72 2144.79  201.06 2144.91  219.67 2144.31
  222.38 2143.95  230.62 2146.05  245.92 2151.76  252.41 2156.17  256.08  2159.5
  282.61 2161.46   291.5 2161.73   302.5 2161.73  311.04 2160.95  335.25 2176.09
#Mann= 3 , 0 , 0
       0      .1       0  175.25     .05       0  230.62     .06       0
Bank Sta=175.25,230.62
Exp/Cntr=0.5,0.3

Type RM Length L Ch R = 3 ,385996.5,,,
BEGIN DESCRIPTION:
STR_151
END DESCRIPTION:
Bridge Culvert--1,0,-1,-1, 0
Deck Dist Width WeirC Skew NumUp NumDn MinLoCord MaxHiCord MaxSubmerge Is_Ogee
0.05,11.3,2.6,0, 2, 2, , , 0.95, 0, 0,0,,
       0     300
    2155    2155
    2151    2151
       0     300
    2155    2155
    2151    2151
Pier Skew, UpSta & Num, DnSta & Num=  ,169, 2 ,215, 2 , 0 , 0 , 0 ,,
       1       1
    2140    2151
       1       1
    2140    2151
Pier Skew, UpSta & Num, DnSta & Num=  ,188, 2 ,234, 2 , 0 , 0 , 0 ,,
       1       1
    2140    2151
       1       1
    2140    2151
Pier Skew, UpSta & Num, DnSta & Num=  ,207, 2 ,253, 2 , 0 , 0 , 0 ,,
       1       1
    2140    2151
       1       1
    2140    2151
Pier Skew, UpSta & Num, DnSta & Num=  ,226, 2 ,272, 2 , 0 , 0 , 0 ,,
       1       1
    2140    2151
       1       1
    2140    2151
BR Coef=-1 , 1 , 0 ,, 0 ,,,0.8,0,2,0,
WSPro=,,,, 1 ,,,, 0 ,,,, 0 ,,,,-1 ,-1 ,-1 , 0 , 0 , 0 , 0 , 0
BR U #Sta/Elev= 69
       0 2170.37   10.09 2167.33   22.63 2163.09   25.37 2162.37    28.5 2161.72
   36.24 2160.06   41.11 2159.27   45.28 2159.17   48.57 2158.67   52.97 2157.86
   56.03 2157.55   59.41  2157.3   65.27 2156.73   72.21 2156.15   74.92 2155.94
   77.86 2155.76   79.62 2155.69   83.72 2155.37    86.7  2155.2   90.02 2154.98
   94.78 2154.82  103.34 2154.64  104.89  2154.6  110.37 2154.61  112.24 2154.41
   119.3 2154.33  122.55 2154.61  123.05 2154.59  126.61 2154.35  132.32 2153.93
  133.57 2153.79  134.32 2153.77  136.07 2153.83  148.14 2153.33  149.28 2152.84
  149.81 2152.61  151.24 2152.19  164.81 2149.84  175.252146.358  179.08 2145.08
  186.08 2143.79  187.74 2143.54  188.34 2143.59  195.62  2144.5  197.72 2144.76
  201.06 2144.88  206.03 2144.71  215.63 2144.41  219.67 2144.28  222.38 2143.92
  230.62 2146.41  245.92 2152.12  252.41 2156.17  256.08  2159.5  260.55  2159.7
  262.66 2159.92  265.47 2160.19  270.13 2160.62  276.74 2161.01  282.61 2161.46
  286.63  2161.6   291.5 2161.73  294.41 2161.79  295.21 2161.81  299.15 2161.84
   302.5 2161.73  310.95 2160.93  311.04 2160.95  335.25 2176.09
BR U #Mann= 3
       0    .065  175.25     .04  230.62     .06
BR D #Sta/Elev= 74
       0 2171.33   21.37 2164.62   29.82 2162.81   36.85  2161.4   41.54 2160.48
    45.8 2160.07   47.12 2159.92   57.25  2159.3   57.46 2159.29   58.96 2159.28
   61.57 2159.24   61.94 2159.23   62.85 2159.21   69.18 2158.92   72.63 2158.85
   75.39 2158.91   80.94 2159.19    89.7 2157.95    97.6 2156.25   99.54 2156.39
  103.74 2156.16  106.84 2156.28  110.26 2156.23  110.79 2156.26  119.11 2156.03
  119.69 2156.04  120.34 2156.01  123.65 2155.78  130.84 2155.05  132.79 2155.04
  144.24 2154.67  147.86 2154.57   154.3 2154.32  158.99 2154.12  159.53 2154.09
  164.77 2154.17  170.61 2153.95   173.5 2153.94  180.08 2154.29  180.17 2154.28
  191.07 2153.11  191.98 2152.94  196.31 2152.28  201.83 2149.86  212.76 2146.67
  216.66 2145.88   220.7 2144.53  223.19 2144.06  228.81 2143.47  239.02 2143.18
  241.74 2143.51  242.23 2143.53  250.91 2143.83   259.1 2143.55  262.24 2143.13
  265.43  2142.7  270.05 2144.09  286.32 2149.07  292.75 2151.48  299.58 2156.12
  305.16 2158.37  306.14 2159.03  307.53 2159.29  316.14 2160.39  317.25 2160.51
  318.31 2160.59  324.54 2160.95  330.86  2161.2  332.03 2161.27  339.61 2161.49
  344.63  2161.7  345.74  2161.6  353.87 2161.12  375.32 2174.51
BR D #Mann= 3
       0    .065   220.7     .04  250.91     .06
BC Design=,, 0 ,, 0 ,,,,,,

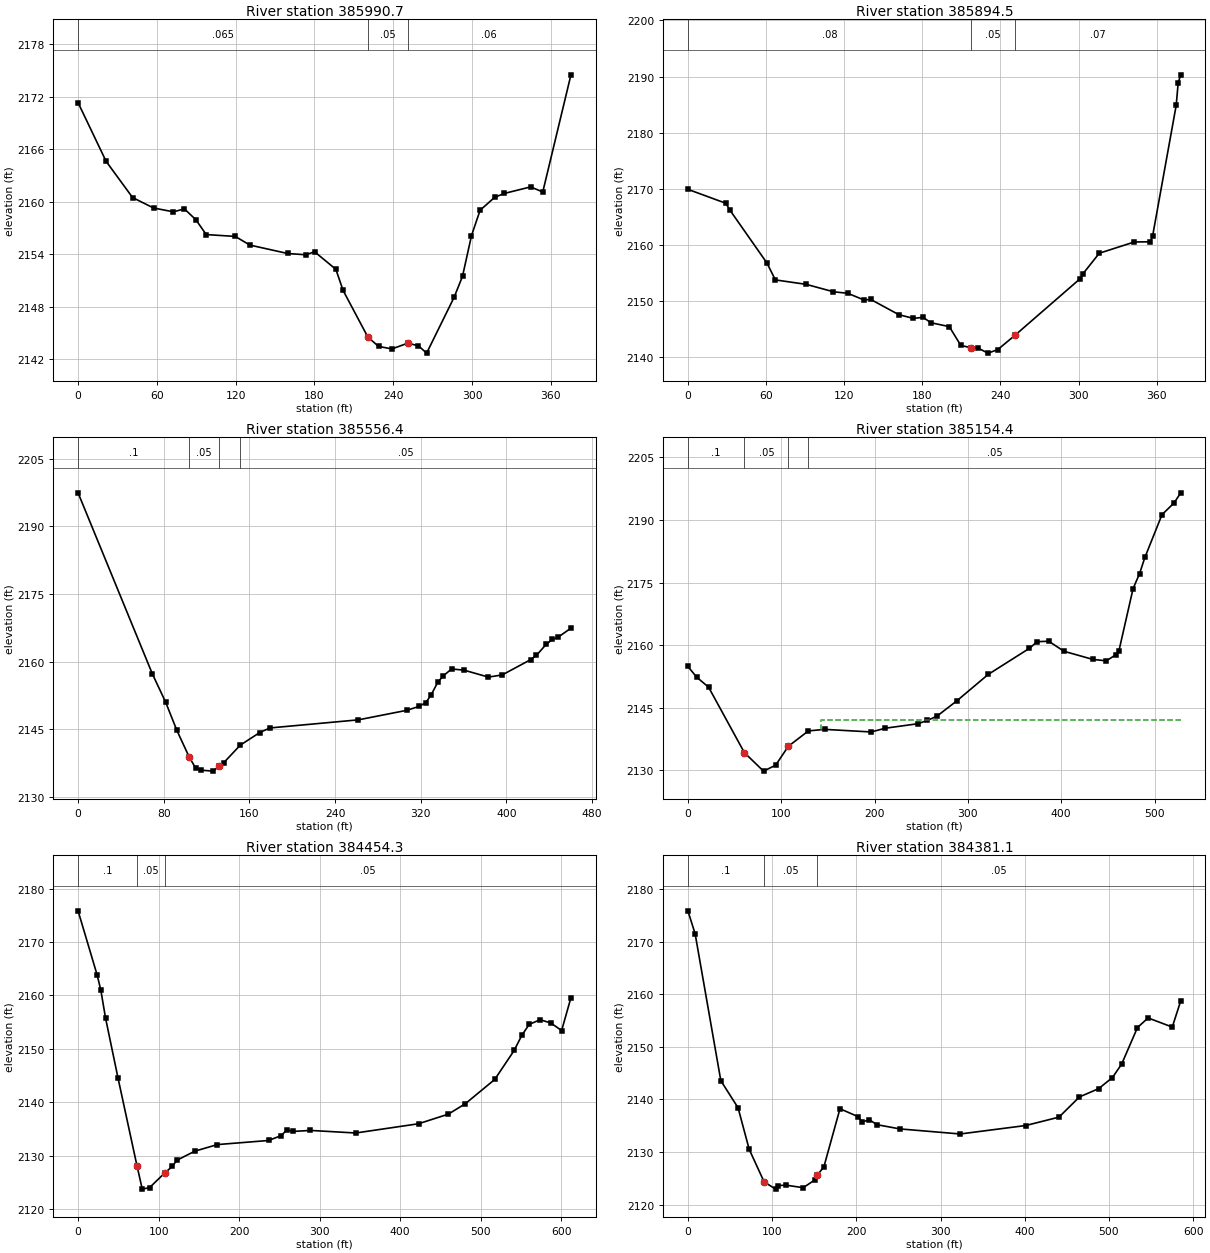
Type RM Length L Ch R = 1 ,385990.7,91.17,96.22,95.41
XS GIS Cut Line= 6
 1033086.8859691  660066.4435882 1032977.8793283  660085.5430454
 1032955.8449973  660128.4070117 1032935.7043217  660153.3814832
 1032836.6120479  660233.1386638  1032784.246237  660255.6962373
#Sta/Elev= 30
       0 2171.33   21.37 2164.62   41.54 2160.48   57.46 2159.29   72.63 2158.85
   80.94 2159.19    89.7 2157.95    97.6 2156.25  119.69 2156.04  130.84 2155.05
  159.53 2154.09   173.5 2153.94  180.08 2154.29  196.31 2152.28  201.83 2149.86
   220.7 2144.53  228.81 2143.47  239.02 2143.18  250.91 2143.83   259.1 2143.55
  265.43  2142.7  286.32 2149.07  292.75 2151.48  299.58 2156.12  306.14 2159.03
  317.25 2160.51  324.54 2160.95  344.63  2161.7  353.87 2161.12  375.32 2174.51
#Mann= 3 , 0 , 0
       0    .065       0   220.7     .05       0  250.91     .06       0
Bank Sta=220.7,250.91
Exp/Cntr=0.5,0.3

Type RM Length L Ch R = 1 ,385894.5,341.06,338.14,351.37
XS GIS Cut Line= 6
 1032954.9157401  659931.0366423 1032949.1973927  660020.9986715
  1032906.434703   660071.949969 1032871.8606213  660094.6960818
 1032818.1797878  660113.8028032 1032738.1134804   660206.606935
#Sta/Elev= 30
       0 2169.92   29.21 2167.43   31.95 2166.32   60.66 2156.81   67.16 2153.79
   90.78    2153  111.74 2151.68  122.85  2151.4  135.15 2150.22  140.39 2150.31
  161.88 2147.61  172.98 2146.94  180.67 2147.12  186.48 2146.17  200.71 2145.47
  209.56 2142.12  217.64  2141.7  222.52 2141.67  230.45 2140.75  237.88 2141.37
  251.01  2143.9  300.77 2153.92   303.5 2154.92  315.89 2158.54  342.72 2160.54
  355.18 2160.58  356.82 2161.59  374.95  2184.9  376.48 2188.94  378.45 2190.31
#Mann= 3 , 0 , 0
       0     .08       0  217.64     .05       0  251.01     .07       0
Bank Sta=217.64,251.01
Exp/Cntr=0.3,0.1

Type RM Length L Ch R = 1 ,385556.4,421.69,401.98,403.53
XS GIS Cut Line= 4
 1032807.8980282  659762.2395465  1032735.086501  659784.9931658
 1032518.9273753  659905.5872056 1032437.0144186  660014.8044509
#Sta/Elev= 30
       0 2197.4469.43997 2157.2381.87997 2150.9392.28998 2144.71  103.86 2138.77
  109.83 2136.34  114.98 2135.88  126.07 2135.67  131.75 2136.74  136.22 2137.58
  151.52 2141.44  169.61 2144.22   179.1 2145.25  261.75 2147.05  307.27 2149.18
  318.71 2150.06  324.88  2150.9  329.75 2152.58  335.87 2155.36  341.04 2156.81
  348.92 2158.35  360.69 2158.07  383.26 2156.54  396.12 2157.02  422.74 2160.42
  428.11 2161.36  437.15  2163.8  443.05  2164.9  448.23 2165.38  460.33  2167.4
#Mann= 4 ,-1 , 0
       0      .1       0  103.86     .05       0  131.75     .08       0
  151.52     .05       0
Bank Sta=103.86,131.75
Exp/Cntr=0.3,0.1

Type RM Length L Ch R = 1 ,385154.4,803.48,700.13,320.7
XS GIS Cut Line= 6
 1032564.4345533  659432.3124456 1032464.3187375  659480.0949885
 1032343.7246977  659584.7615342 1032289.1160599  659680.3266201
 1032245.8842166   659750.862752 1032204.9277685  659800.9206599
#Sta/Elev= 30
       0  2154.9    9.35 2152.35   22.17 2149.93   60.55 2134.25   81.04 2129.83
   94.01 2131.25  107.57 2135.77  129.06 2139.46  146.51 2139.83  196.45 2139.21
  211.57 2140.11  246.38 2141.18  256.69 2141.97  266.89    2143  288.49 2146.72
   321.7 2152.98  365.85 2159.23  374.27 2160.83  386.57 2160.94  402.97 2158.53
  433.83 2156.59  448.31 2156.24  458.18 2157.65  461.75 2158.56  476.98 2173.54
  483.92 2177.12  489.64 2181.01  507.96 2191.25  520.98 2194.08  528.09 2196.48
#Mann= 4 ,-1 , 0
       0      .1       0   60.55     .05       0  107.57     .08       0
  129.06     .05       0
#XS Ineff= 2 , 0
       0                   142.3       0    2142
Permanent Ineff=
       F       F
Bank Sta=60.55,107.57
Exp/Cntr=0.3,0.1

Type RM Length L Ch R = 1 ,384454.3,75.98,73.15,57.45
XS GIS Cut Line= 6
 1031881.2602973  659129.2804708 1031892.6567054  659161.3975797
 1032030.4494642  659289.8660155 1032035.6590069  659407.4490272
 1032065.3564634  659528.9385451  1032045.558149  659671.1263051
#Sta/Elev= 30
       0 2175.85   23.74 2163.81   28.32 2160.96   34.08 2155.81   49.52 2144.61
   73.22 2128.07   79.72 2123.74   88.73 2124.02  107.68 2126.77  117.21 2128.02
  122.49 2129.13  144.86 2130.84  172.91 2132.08  236.67 2132.85  252.18 2133.76
  259.44 2134.85  266.54 2134.54   288.6 2134.73   344.8 2134.25  422.75 2135.98
  459.75 2137.78  480.77 2139.72  517.36 2144.27   541.5  2149.7  550.92 2152.51
  560.17 2154.58  573.75 2155.46  587.02 2154.85  600.45 2153.44  612.02 2159.58
#Mann= 3 , 0 , 0
       0      .1       0   73.22     .05       0  107.68     .05       0
Bank Sta=73.22,107.68
Exp/Cntr=0.5,0.3

Type RM Length L Ch R = 1 ,384381.1,22.99,20.85,85.36
XS GIS Cut Line= 6
 1031827.3864449  659151.0372142 1031837.7468104   659199.730914
  1031980.719752  659316.8029417 1031983.4635139  659405.6491722
   1032020.36033   659615.331102 1032010.4611879  659663.0269877
#Sta/Elev= 30
       0 2175.86     8.6 2171.49   39.11 2143.55   59.58  2138.4   72.74 2130.52
   90.53 2124.31  104.17 2122.93  107.04  2123.6  116.43 2123.69  136.91  2123.2
  151.29 2124.74  153.73 2125.59  161.53  2127.2   180.6 2138.22   202.4 2136.69
  206.88 2135.71   215.6 2136.12   224.4 2135.19  251.86 2134.38  323.34 2133.42
   401.3 2135.03  440.66 2136.62  465.02 2140.47  487.79 2142.04  504.13 2144.15
  515.03 2146.69  533.88 2153.66  546.49 2155.49  575.21 2153.75   585.3 2158.76
#Mann= 3 , 0 , 0
       0      .1       0   90.53     .05       0  153.73     .05       0
Bank Sta=90.53,153.73
Exp/Cntr=0.5,0.3

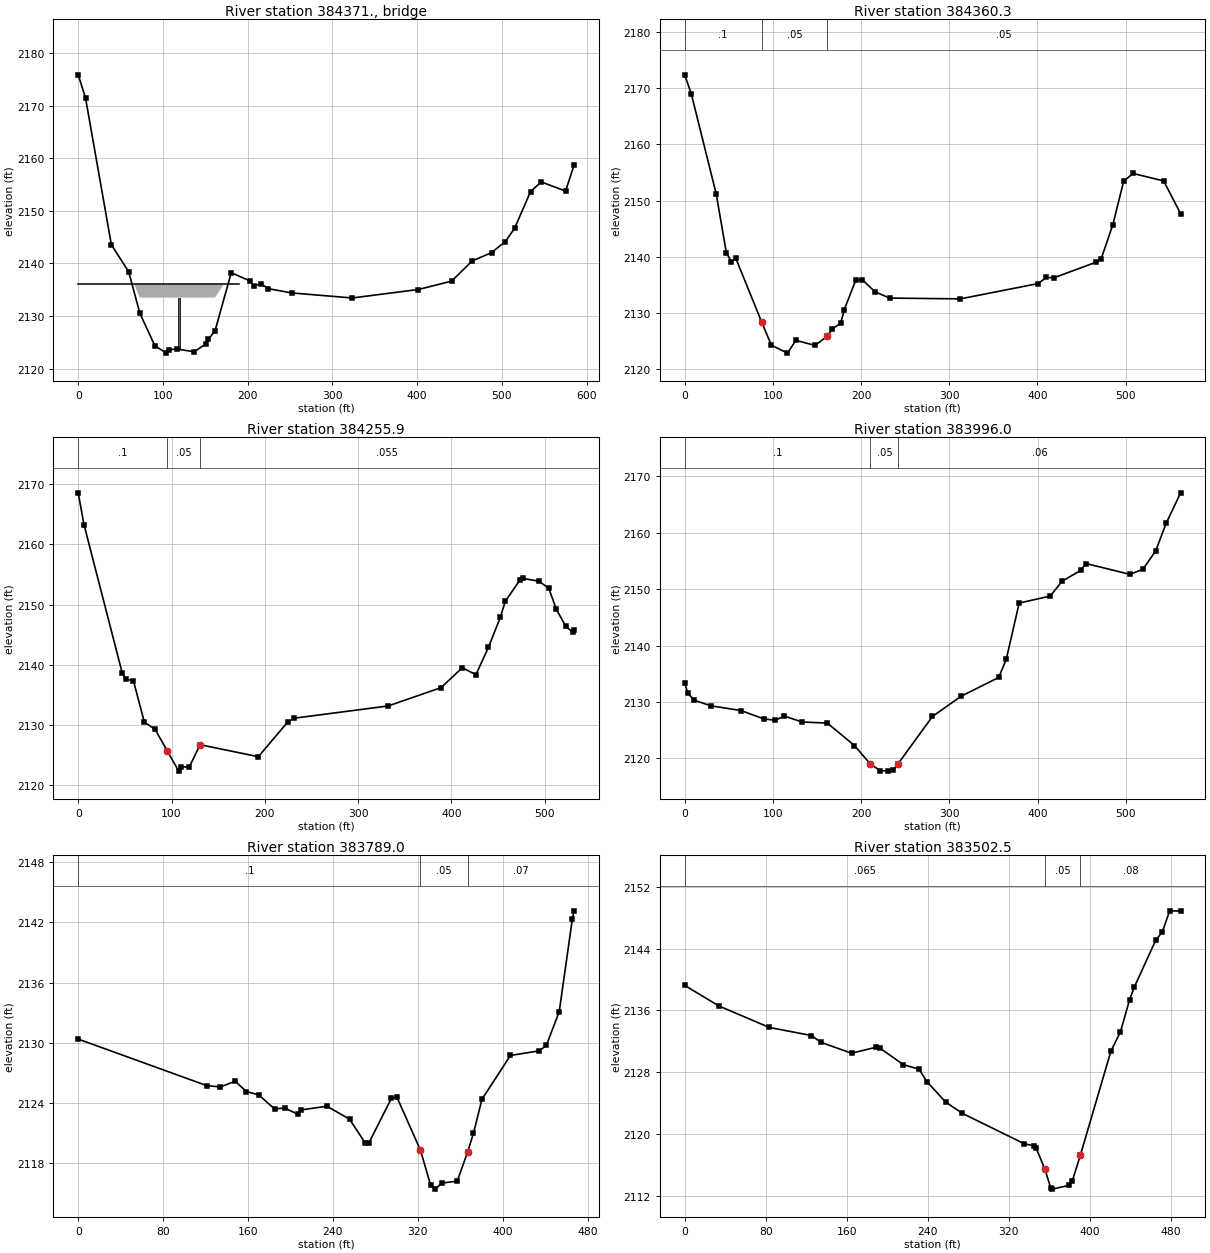
Type RM Length L Ch R = 3 ,384371. ,,,
BEGIN DESCRIPTION:
STR_150
END DESCRIPTION:
Bridge Culvert--1,0,-1,-1, 0
Deck Dist Width WeirC Skew NumUp NumDn MinLoCord MaxHiCord MaxSubmerge Is_Ogee
2,18,2.6,0, 2, 2, , , 0.95, 0, 0,0,,
       0     190
    2136    2136
  2133.5  2133.5
       0     198
    2136    2136
  2133.5  2133.5
Pier Skew, UpSta & Num, DnSta & Num=  ,119, 2 ,128, 2 , 0 , 0 , 0 ,,
       3       3
    2120  2133.5
       3       3
    2120  2133.5
BR Coef=-1 , 1 , 0 ,, 0 ,,,0.8,0,2,0,
WSPro=,,,, 1 ,,,, 0 ,,,, 0 ,,,,-1 ,-1 ,-1 , 0 , 0 , 0 , 0 , 0
BC Design=,, 0 ,, 0 ,,,,,,

Type RM Length L Ch R = 1 ,384360.3,60.11,104.36,60.13
XS GIS Cut Line= 6
 1031813.9179818  659151.0372142 1031825.3143597  659215.2714321
 1031928.9179545  659303.3344786 1031931.2679906   659412.848562
 1031899.7707093  659600.0324251 1031906.0701716   659661.227163
#Sta/Elev= 30
       0  2172.4    7.52    2169    35.8 2151.13   47.24 2140.71      53 2139.06
   57.98  2139.7   87.22 2128.36   98.25 2124.22  116.56  2122.8  126.02 2125.07
  147.78 2124.18  161.63 2125.79  167.28 2127.11  176.89 2128.11   180.8 2130.49
  193.83 2135.76  201.41 2135.89  215.52 2133.76  232.34 2132.61  312.53 2132.47
  400.52 2135.19  410.09 2136.28  418.82 2136.24   466.8 2139.03  472.06 2139.54
  485.51 2145.72  497.71 2153.44   508.4 2154.82  543.04 2153.49  562.29 2147.66
#Mann= 3 , 0 , 0
       0      .1       0   87.22     .05       0  161.63     .05       0
Bank Sta=87.22,161.63
Exp/Cntr=0.5,0.3

Type RM Length L Ch R = 1 ,384255.9,217.77,259.92,316.43
XS GIS Cut Line= 6
 1031776.6764437  659156.9677401  1031778.012442  659295.9122862
 1031818.0926018  659374.7366077 1031835.4606701   659493.641089
 1031873.6729628    659534.33808 1031860.1741409  659657.6274529
#Sta/Elev= 30
       0 2168.56    6.17 2163.29   47.15 2138.64   50.81 2137.63   59.25  2137.3
   70.84 2130.47   82.42 2129.25   95.46 2125.68  107.73 2122.32  110.52 2123.06
  118.94 2122.96   130.6 2126.71  193.03 2124.72  224.84 2130.53  231.34 2131.11
  332.25 2133.15  388.85 2136.19  411.63  2139.5  426.25 2138.34  439.72 2142.91
  452.45 2147.87   457.7 2150.54  473.71 2154.13  476.75 2154.33  493.53 2153.88
  504.29 2152.72  512.25 2149.27  522.56 2146.36   530.2 2145.36  531.53 2145.72
#Mann= 3 , 0 , 0
       0      .1       0   95.46     .05       0   130.6    .055       0
Bank Sta=95.46,130.6
Exp/Cntr=0.3,0.1

Type RM Length L Ch R = 1 ,383996.0,195.42,206.94,209.53
XS GIS Cut Line= 6
 1031654.3326726  659167.3191161 1031568.6467217  659283.7641728
 1031551.0701071  659351.8735394 1031555.4642607  659435.3624286
 1031676.3034409  659545.2162398 1031660.9239182  659644.0846819
#Sta/Elev= 30
       0 2133.42    3.48 2131.56   10.84  2130.3   29.82 2129.32   63.88 2128.48
   89.59    2127  102.57 2126.77     113 2127.49  133.31 2126.45  161.64 2126.26
   192.4 2122.28  210.44    2119  221.31 2117.86  230.84 2117.75  236.35 2117.92
  241.95 2119.09  280.68 2127.43  313.36 2131.03  355.76 2134.34   364.3 2137.53
  378.98 2147.52  414.17 2148.76  427.37 2151.36  448.48  2153.3   454.5 2154.53
  504.77  2152.6  519.42 2153.56  533.67 2156.78  545.61 2161.69  561.89 2167.05
#Mann= 3 , 0 , 0
       0      .1       0  210.44     .05       0  241.95     .06       0
Bank Sta=210.44,241.95
Exp/Cntr=0.3,0.1

Type RM Length L Ch R = 1 ,383789.0,179,286.51,351.24
XS GIS Cut Line= 6
 1031478.7472564  659062.1113487 1031350.4907267  659263.8481765
 1031341.1387086  659331.9844513 1031354.4987518  659406.8007477
 1031346.4827319  659448.2169058 1031319.7626152   659477.609019
#Sta/Elev= 30
       0 2130.38  120.94 2125.75  134.06 2125.61   147.8 2126.18  158.54 2125.15
  169.97 2124.83     185 2123.42   194.5 2123.51  207.03 2122.89  209.84 2123.32
  234.38 2123.69  255.65  2122.4  270.29 2120.05  273.76    2120  295.11 2124.48
  300.34 2124.58   322.5  2119.3  331.94 2115.86  336.21 2115.43  342.84 2116.04
  357.09 2116.22  366.88 2119.12  372.44    2121  380.37 2124.38  407.29 2128.75
  434.45 2129.21  441.11 2129.76  453.23 2133.12  465.53 2142.32  467.28 2143.16
#Mann= 3 , 0 , 0
       0      .1       0   322.5     .05       0  366.88     .07       0
#XS Ineff= 2 , 0
       0  300.34 2124.58               0
Permanent Ineff=
       F       F
Bank Sta=322.5,366.88
Exp/Cntr=0.3,0.1

Type RM Length L Ch R = 1 ,383502.5,470.06,400.58,392.39
XS GIS Cut Line= 6
 1031397.2747593  658949.8085857 1031321.0986135  658996.6471007
 1031254.2983673  659150.2877185 1031235.5942705  659170.3277833
  1031140.783281  659190.8862175 1031044.5455196  659235.7920616
#Sta/Elev= 30
       0 2139.24    33.7 2136.58   83.49  2133.8  125.11 2132.75  134.93 2131.85
  164.78 2130.46  188.72 2131.23  192.69 2131.13  215.76 2128.99  231.54 2128.38
  239.02  2126.8  257.58 2124.15  274.14 2122.68  335.47 2118.73  345.03 2118.48
  346.82 2118.24  355.66 2115.44  361.57 2112.96  362.71 2112.87  379.39 2113.35
  382.65 2113.91  390.65 2117.25  420.79 2130.72  430.21 2133.22   439.3  2137.4
     444 2139.05  464.97 2145.05  471.66  2146.2  478.86 2148.89  489.64 2148.86
#Mann= 3 , 0 , 0
       0    .065       0  355.66     .05       0  390.65     .08       0
Bank Sta=355.66,390.65
Exp/Cntr=0.3,0.1

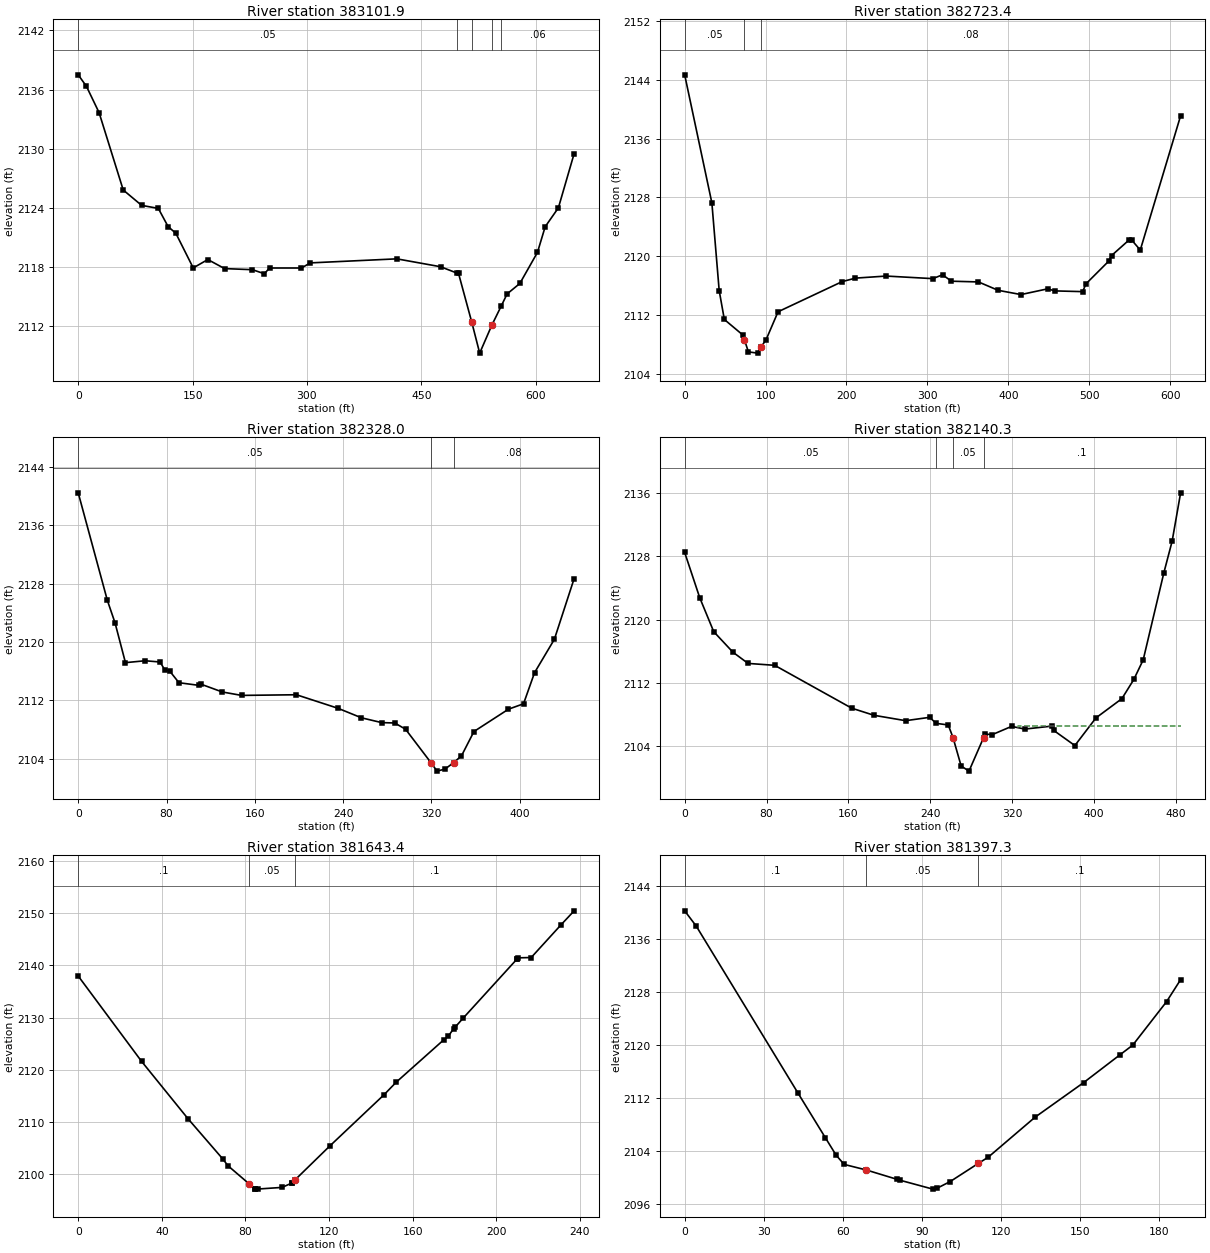
Type RM Length L Ch R = 1 ,383101.9,190.01,378.53,452.99
XS GIS Cut Line= 4
 1031405.1845083  658623.5688206 1031049.9062508  658766.1327207
   1030963.91535  658831.7573587 1030839.4547879  658931.3257781
#Sta/Elev= 30
       0 2137.4910.79999 2136.32   27.38 2133.6559.02002  2125.883.14001 2124.24
  105.06 2123.93  117.85 2122.09  128.07  2121.4  150.82 2117.89  169.98 2118.74
  191.99 2117.82  228.45 2117.71   244.1  2117.3  250.89 2117.88   292.7 2117.88
  304.41  2118.4  417.81 2118.81  475.16 2118.01  496.86 2117.36  498.76 2117.33
     516 2112.41  526.49 2109.24  542.43 2112.08  554.48 2113.98  562.44 2115.25
  579.14 2116.31  602.27 2119.47  612.37 2122.07   629.7 2123.99  650.37  2129.5
#Mann= 5 ,-1 , 0
       0     .05       0  496.86     .08       0     516     .05       0
  542.43     .08       0  554.48     .06       0
#XS Ineff= 2 , 0
       0  417.81 2118.81               0
Permanent Ineff=
       F       F
Bank Sta=516,542.43
Exp/Cntr=0.3,0.1

Type RM Length L Ch R = 1 ,382723.4,200.88,395.44,407.51
XS GIS Cut Line= 5
 1030733.0976244  658485.5307702 1030968.4411694  658585.0992198
 1031185.6813765  658499.1082888 1031237.7285261  658490.0566198
 1031298.8273447  658453.8499136
#Sta/Elev= 30
       0 2144.67   33.61 2127.24   42.64 2115.31   49.02 2111.37   71.97 2109.25
   73.93 2108.59   78.75 2106.96   90.19 2106.79   94.04 2107.57   100.6 2108.61
  115.43 2112.42  194.59 2116.52  211.11    2117   249.1 2117.28  306.67 2116.93
  318.74 2117.45   329.8 2116.58  363.15 2116.48  387.46 2115.34  415.67 2114.76
  448.65 2115.54  457.48 2115.26  491.89 2115.16  496.11 2116.23  524.16 2119.31
  527.65 2120.07  548.79 2122.14  552.32 2122.21  563.16 2120.82  613.03  2139.1
#Mann= 3 , 0 , 0
       0     .05       0   73.93     .05       0   94.04     .08       0
Bank Sta=73.93,94.04
Exp/Cntr=0.3,0.1

Type RM Length L Ch R = 1 ,382328.0,187.82,187.71,159.8
XS GIS Cut Line= 5
 1031321.6784874  658316.3830804 1031287.9689499  658301.0605826
 1031186.8403676  658291.8670779 1030979.9864355  658158.5612139
 1030917.1641582  658143.2386858
#Sta/Elev= 30
       0 2140.46    26.4 2125.72   33.37 2122.63   42.79 2117.18   60.64 2117.44
   74.18 2117.27   78.52 2116.16   82.77 2116.05   91.27 2114.43  109.21 2114.07
  110.84 2114.25  130.53 2113.16  148.02 2112.69  197.71 2112.78  235.46 2110.92
  256.61 2109.62  274.97 2108.96  286.82 2108.91   296.6 2108.05  320.05 2103.38
   325.1 2102.31  332.32 2102.59  340.18 2103.48  347.23  2104.4  358.54 2107.74
   389.8  2110.8  403.46 2111.54  413.46 2115.81   431.4 2120.38  449.33 2128.71
#Mann= 3 , 0 , 0
       0     .05       0  320.05     .05       0  340.18     .08       0
Bank Sta=320.05,340.18
Exp/Cntr=0.3,0.1

Type RM Length L Ch R = 1 ,382140.3,691.59,496.9,128.13
XS GIS Cut Line= 4
 1031371.2407269  658184.5625569   1031344.08572  658130.2525127
 1031052.1691756  658005.7919808 1030945.8119818  657999.0032064
#Sta/Elev= 30
       0 2128.4814.73001 2122.7628.39001 2118.4847.12003 2115.8961.95001 2114.47
87.95001 2114.23  163.21 2108.82  184.99 2107.92   215.9 2107.24  239.28 2107.66
  245.87  2106.9  257.56  2106.7  262.24  2105.1  270.16 2101.52  277.82 2100.87
  292.04 2105.08  293.38 2105.55  300.58 2105.48  319.47 2106.52  332.36 2106.18
  358.52 2106.55  360.75    2106  381.29  2104.1   401.9 2107.59  427.24 2110.02
  438.89 2112.44  448.07 2114.92  468.33 2125.95  476.32 2129.89  484.64 2136.01
#Mann= 4 ,-1 , 0
       0     .05       0  245.87     .08       0  262.24     .05       0
  292.04      .1       0
#XS Ineff= 2 , 0
       0                  326.09       0 2106.63
Permanent Ineff=
       F       F
Bank Sta=262.24,292.04
Exp/Cntr=0.3,0.1

Type RM Length L Ch R = 1 ,381643.4,212.43,246.08,240.05
XS GIS Cut Line= 6
 1031043.2095213  657758.1701399 1031029.8494478  657808.9383464
 1031004.4653597   657851.690533 1030979.0812413  657887.7626678
 1030955.0331515   657917.154781 1030917.6250184  657954.5629443
#Sta/Elev= 28
       0 2137.98   30.28 2121.62    52.5 2110.61    69.2 2102.86   71.63 2101.58
   81.83 2098.08   82.37  2097.9   84.65 2097.12   84.79 2097.09   86.02 2097.11
   97.51 2097.42   102.1 2098.24  102.22 2098.29  103.68 2098.85  120.39 2105.38
  146.33 2115.21  152.13 2117.61  175.04  2125.8  176.99 2126.39  179.54 2127.86
   180.4 2128.21  184.31 2129.97  209.83  2141.2  209.93 2141.24  210.58 2141.47
   216.7 2141.53  231.07 2147.85  237.25 2150.49
#Mann= 3 , 0 , 0
       0      .1       0   81.83     .05       0  103.68      .1       0
Bank Sta=81.83,103.68
Exp/Cntr=0.3,0.1

Type RM Length L Ch R = 1 ,381397.3,189.55,224.31,266.64
XS GIS Cut Line= 6
 1030859.8086106  657740.8961445 1030808.7669632  657787.0766941
 1030785.6766732  657796.7989199  1030772.308609   657807.736405
 1030743.1419619  657852.7016954  1030735.850285  657874.5766958
#Sta/Elev= 20
       0 2140.29     4.4 2137.97   42.97 2112.74    53.4 2105.96   57.45 2103.34
   60.49 2101.94   68.97 2101.09   80.67 2099.67   81.66 2099.55   94.17  2098.2
   95.59  2098.3  100.76 2099.35  111.45  2102.1  115.17 2103.03  132.98 2109.09
   151.4 2114.32  165.11  2118.5  170.01 2119.98  182.85 2126.56  188.17 2129.88
#Mann= 3 , 0 , 0
       0      .1       0   68.97     .05       0  111.45      .1       0
Bank Sta=68.97,111.45
Exp/Cntr=0.3,0.1