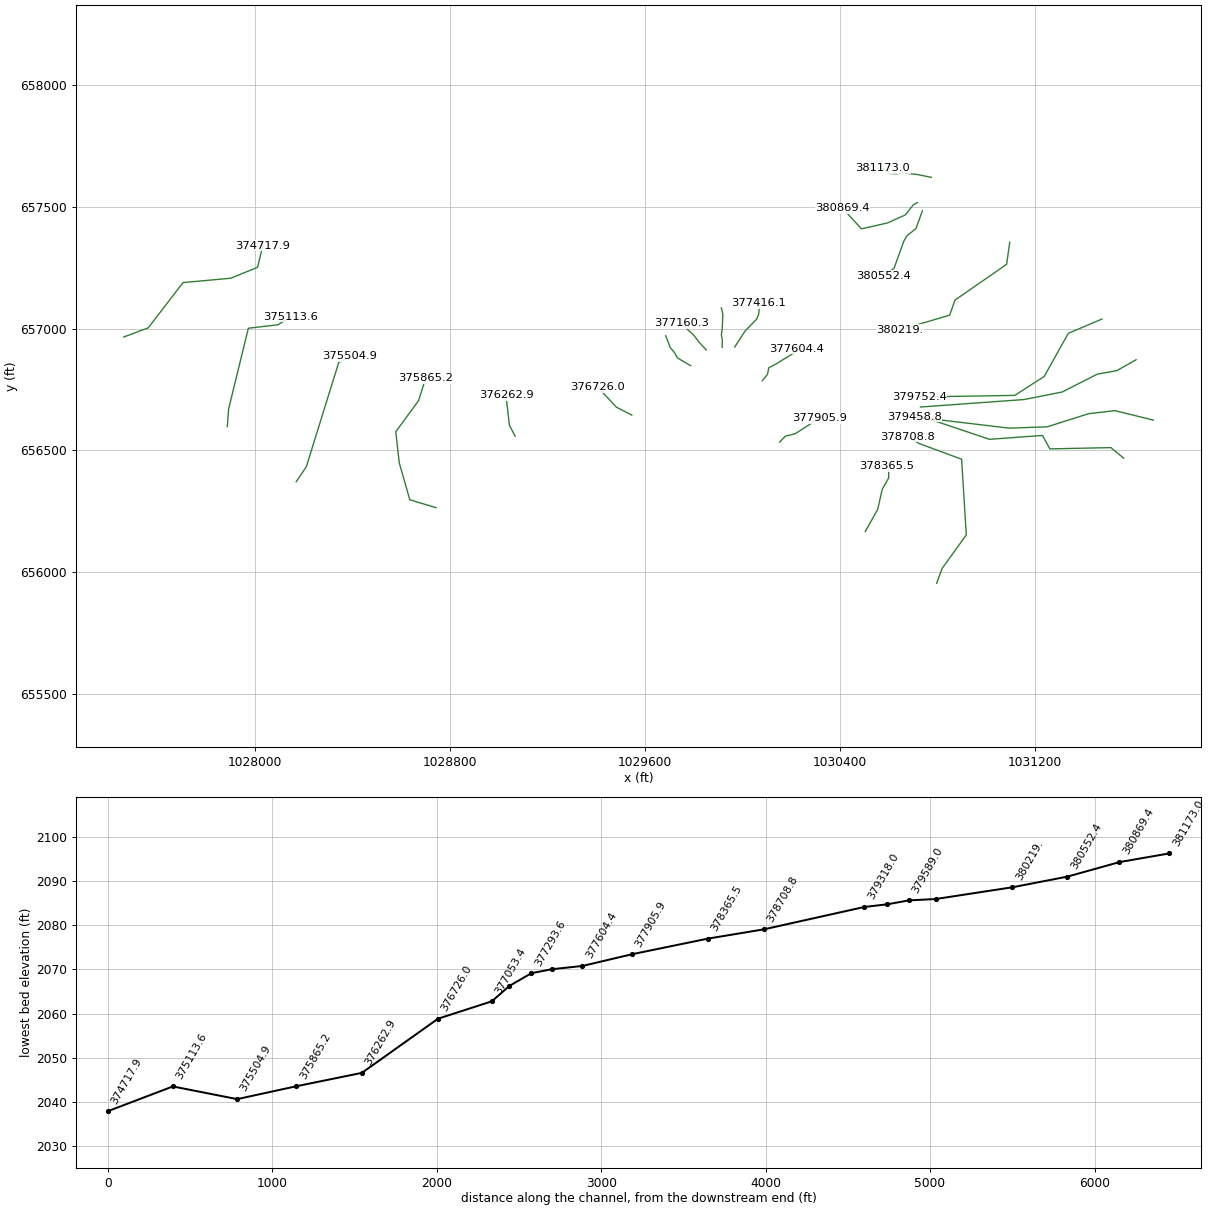
HEC-RAS study lds_broad_rvr.prj: Upper_Broad 3-06-07

--- lds_broad_rvr.g05 (geometry) --- (continued)

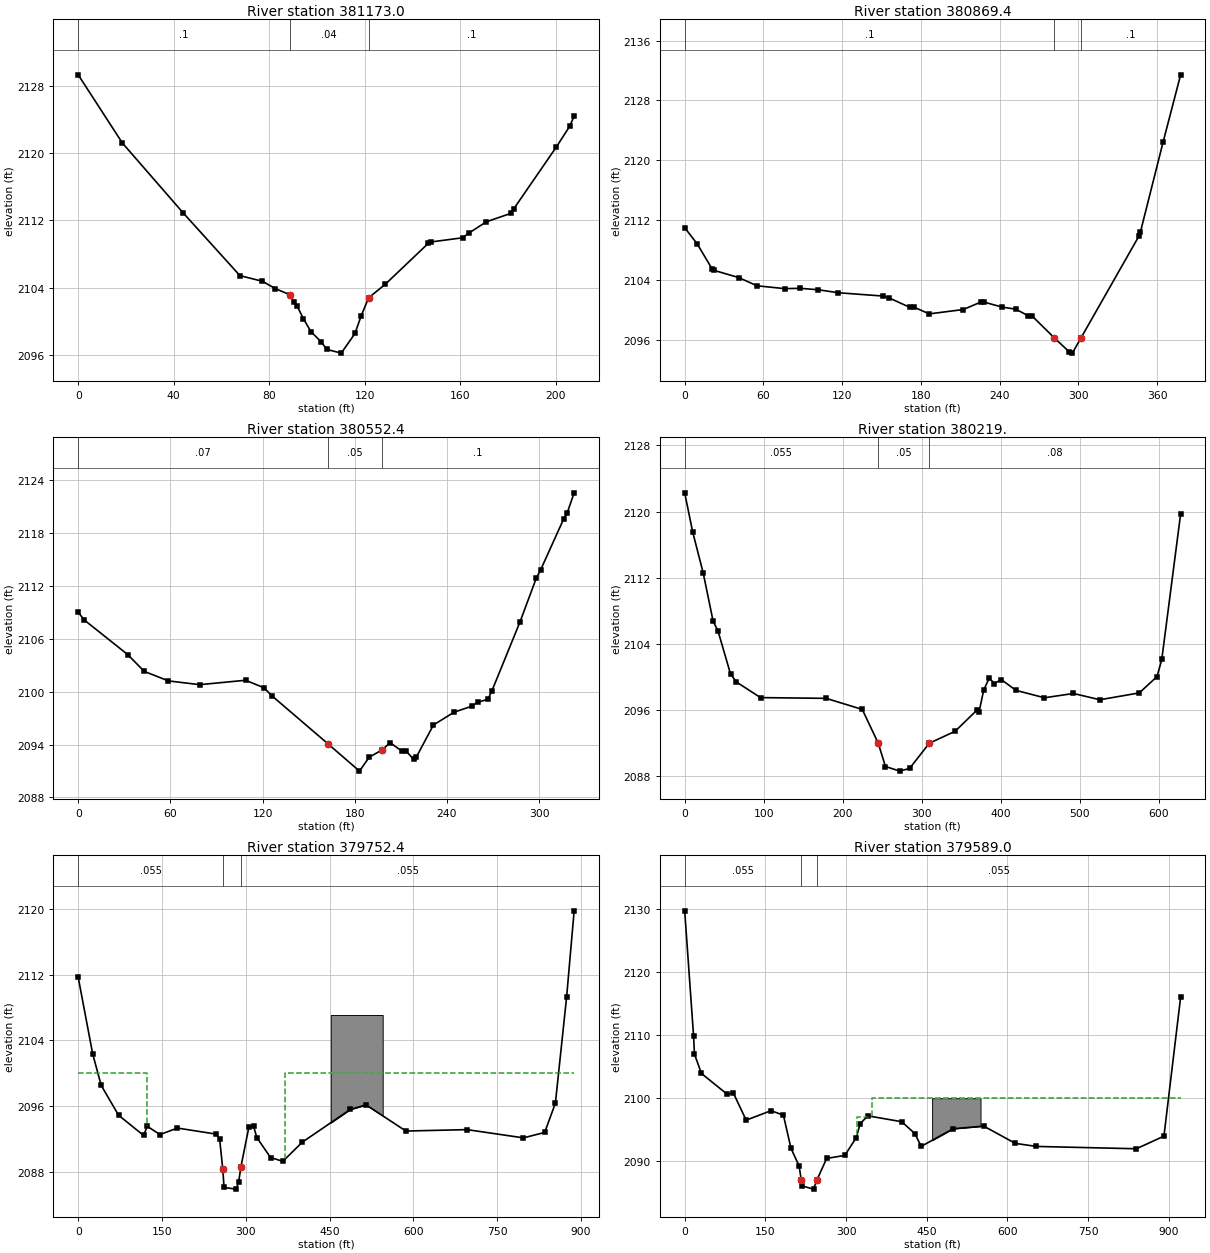
Type RM Length L Ch R = 1 ,381173.0,191.65,303.61,254.42
XS GIS Cut Line= 6
 1030774.7391881  657620.5836271 1030713.9752846  657632.7364017
 1030654.4266707  657638.8127891 1030630.1211215  657635.1669809
 1030605.8155722  657636.3822402 1030575.4336053  657657.0419813
#Sta/Elev= 28
       0 2129.27    18.5 2121.18   43.83 2112.93   67.75 2105.44   77.15 2104.77
   82.59  2103.9   88.63 2103.17   90.53 2102.29    91.8 2101.78   94.35 2100.32
   97.52 2098.79  101.65 2097.62  104.19 2096.68  110.21 2096.24  115.95 2098.57
  118.49 2100.61  121.66  2102.8  128.65 2104.41  146.63 2109.26  147.71 2109.43
  161.02 2109.93  163.64 2110.48  171.03 2111.83  181.19 2112.82   182.5 2113.37
  200.37 2120.72  205.98 2123.19  207.79 2124.37
#Mann= 3 , 0 , 0
       0      .1       0   88.63     .04       0  121.66      .1       0
Bank Sta=88.63,121.66
Exp/Cntr=0.3,0.1

Type RM Length L Ch R = 1 ,380869.4,79.73,316.98,373.71
XS GIS Cut Line= 6
 1030717.6211231  657517.2850124 1030700.6072204  657507.5628169
  1030667.794735   657466.243365 1030594.8780569  657433.4308492
 1030487.9336037  657409.1252999 1030410.1558278  657494.1947527
#Sta/Elev= 30
       0 2111.02    9.58 2108.84   20.73 2105.56   22.52 2105.31   41.26 2104.35
   55.04 2103.26   76.15 2102.88   88.04 2102.92  101.72 2102.73  117.06 2102.33
  151.01 2101.89  155.74 2101.64  171.66 2100.37  174.74  2100.4  186.28 2099.51
  212.23 2100.09  225.38 2101.07  227.82 2101.09  241.74 2100.42  252.33 2100.13
  261.74 2099.25  264.74 2099.21  281.68 2096.29  292.83 2094.46  295.33 2094.27
  301.71 2096.24   346.2 2109.94  347.19 2110.45  364.51 2122.48   377.8 2131.42
#Mann= 3 , 0 , 0
       0      .1       0  281.68     .05       0  301.71      .1       0
Bank Sta=281.68,301.71
Exp/Cntr=0.3,0.1

Type RM Length L Ch R = 1 ,380552.4,368.98,333.43,286.51
XS GIS Cut Line= 6
 1030738.2808339  657483.2572373 1030711.5447358  657410.3405895
 1030673.8711223  657379.9586226 1030661.7183476  657358.0836222
 1030621.6141853  657247.4933609 1030579.0794438  657215.8961347
#Sta/Elev= 30
       0 2109.02    3.99 2108.14   32.21 2104.22   42.97 2102.31   58.67 2101.23
   79.03  2100.8  108.91  2101.3   120.9 2100.45  126.11 2099.53  162.52 2094.09
  183.09 2090.98  189.34 2092.55  197.79 2093.39  203.03 2094.21  211.02 2093.21
  213.61 2093.21  218.34 2092.34  220.16  2092.6  231.22 2096.22  244.61 2097.67
  256.12 2098.35  260.29 2098.83  266.66 2099.13  269.27 2100.09  287.66 2107.97
  298.28 2112.95  301.08 2113.87  316.04 2119.64  318.36 2120.35  322.82 2122.59
#Mann= 3 , 0 , 0
       0     .07       0  162.52     .05       0  197.79      .1       0
Bank Sta=162.52,197.79
Exp/Cntr=0.3,0.1

Type RM Length L Ch R = 1 ,380219. ,421.28,466.51,472.78
XS GIS Cut Line= 5
 1031096.4551921  657354.2304481 1031083.7262967  657263.5369025
 1030872.1080033  657117.1543641 1030849.8324062  657055.1008631
 1030646.1697178  656994.6385195
#Sta/Elev= 30
       0 2122.27   10.12 2117.53    23.5 2112.54    35.9 2106.76   42.35 2105.49
   57.98 2100.34   65.39 2099.37   95.96 2097.48  178.83 2097.39  224.63 2096.05
  244.752091.972  253.96 2089.14     272 2088.58  284.49 2088.91  309.43 2091.96
     342  2093.4  370.24 2096.02  372.31 2095.72  378.23 2098.41  385.27 2099.84
  391.84 2099.18  400.37 2099.67  418.92 2098.36  455.03 2097.46  491.69 2097.98
  525.19 2097.22  575.01 2098.05  597.39 2100.02  603.44  2102.1  627.27 2119.71
#Mann= 3 , 0 , 0
       0    .055       0  244.75     .05       0  309.43     .08       0
Bank Sta=244.75,309.43
Exp/Cntr=0.3,0.1

Type RM Length L Ch R = 1 ,379752.4,64.2,163.4,200.2
XS GIS Cut Line= 5
 1031475.1405242  657039.1897137 1031336.7135302  656980.3184669
 1031238.0644099  656803.7047264 1031117.1396924  656725.7401063
 1030725.7254649  656719.3756587
#Sta/Elev= 30
       0 2111.6625.91998 2102.3541.14001 2098.5372.29999  2094.9  117.14 2092.44
  123.61 2093.56   146.4 2092.55  177.72 2093.34  247.62  2092.6  253.34 2091.96
  258.86 2088.34  261.17 2086.12  283.07 2085.92  287.39 2086.83  291.35 2088.63
   305.6 2093.45  313.96 2093.58  319.82 2092.19  344.43 2089.76  366.38  2089.3
  401.36 2091.63  487.14  2095.6   515.4 2096.16  586.86 2092.98  696.36 2093.15
  797.23 2092.15  835.28 2092.81  854.45 2096.36  874.62  2109.3  888.07 2119.74
#Mann= 3 ,-1 , 0
       0    .055       0  258.86     .05       0  291.35    .055       0
#XS Ineff= 2 , 0
       0  123.61    2100     370       0    2100
Permanent Ineff=
       F       F
#Block Obstruct= 1 ,-1
  452.23  545.22 2107.08
Bank Sta=258.86,291.35
Exp/Cntr=0.5,0.3

Type RM Length L Ch R = 1 ,379589.0,166.73,130.2,133.92
XS GIS Cut Line= 6
 1031615.0284626  656872.0214286 1031536.2845027  656827.5139717
 1031455.2580648  656812.6781527 1031311.4647097  656739.6402513
 1031156.2591769  656708.8273895 1030730.2172046  656678.0486837
#Sta/Elev= 30
       0 2129.67    16.5 2109.89    18.2 2106.99   31.16 2103.92   78.63 2100.66
   90.71 2100.79  114.29 2096.53  160.64 2098.03   183.6 2097.31  197.62 2092.07
  212.53 2089.32  216.93 2086.99  218.61 2086.11   239.5 2085.61  246.01 2087.09
  263.94 2090.47  297.77 2090.95  318.99 2093.77  325.96 2095.91  340.16 2097.22
  403.53 2096.28  428.23 2094.38   439.6 2092.37  498.99 2095.17  555.89 2095.59
   614.7 2092.85  653.84 2092.37  839.77    2092     891    2094     922    2116
#Mann= 3 , 0 , 0
       0    .055       0  216.93    .045       0  246.01    .055       0
#XS Ineff= 3 ,-1
       0   178.5    2097   320.5  347.67    2097  347.67     922    2100
Permanent Ineff=
       F       F       F
#Block Obstruct= 1 ,-1
     460     550    2100
Bank Sta=216.93,246.01
Exp/Cntr=0.5,0.3

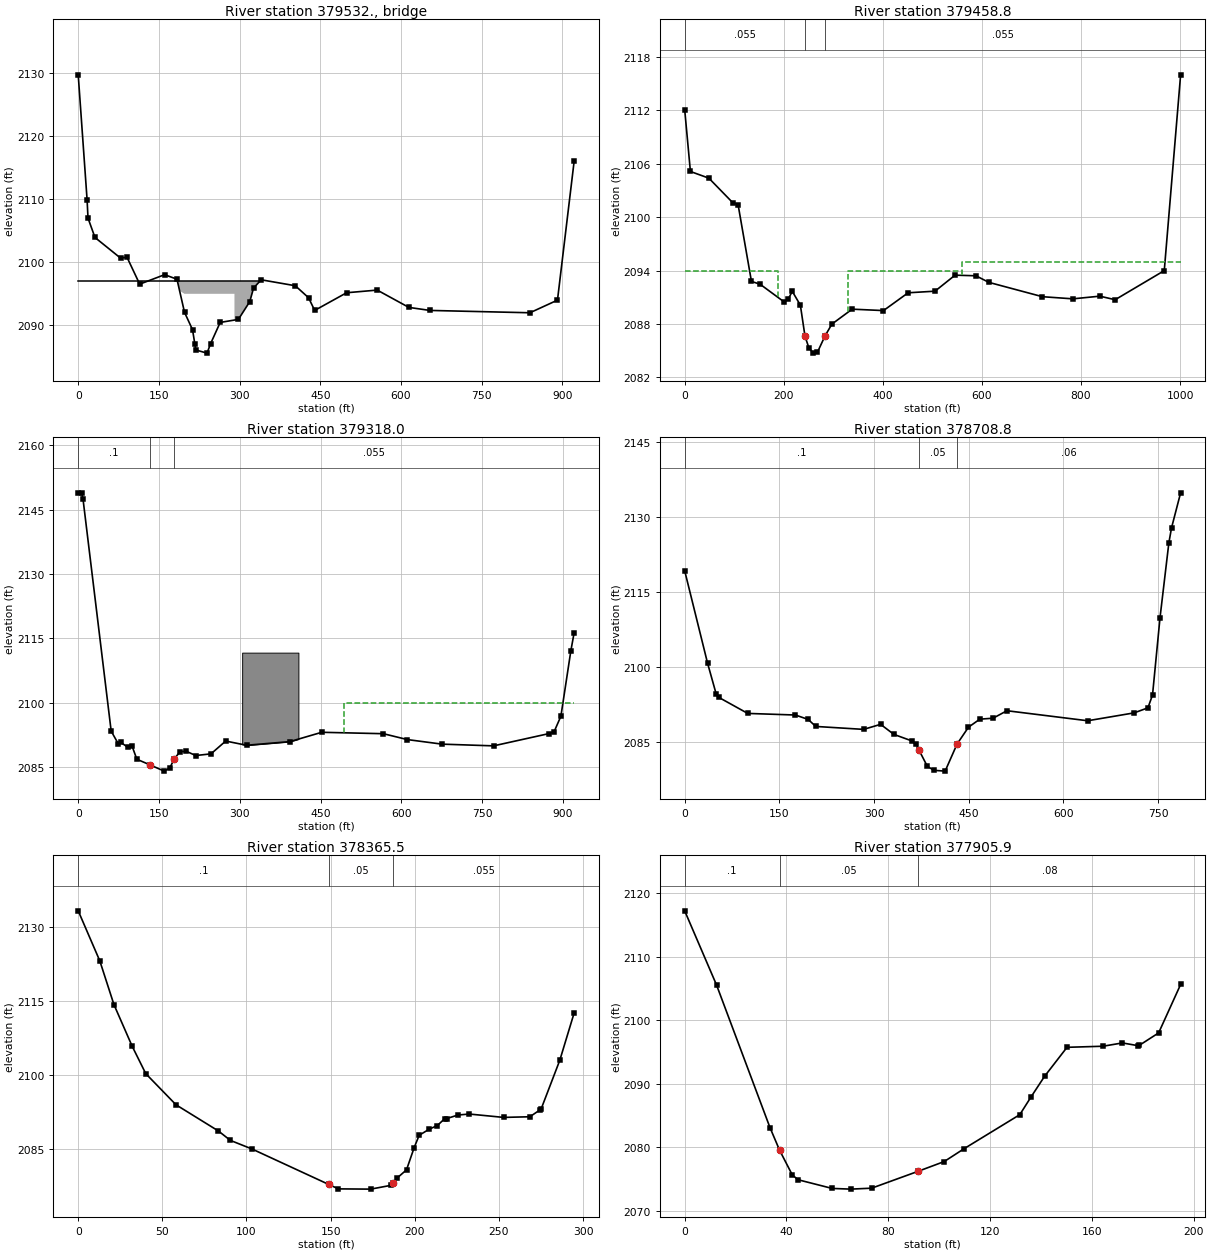
Type RM Length L Ch R = 3 ,379532. ,,,
BEGIN DESCRIPTION:
STR_146
END DESCRIPTION:
Bridge Culvert--1,0,-1,-1, 0
Deck Dist Width WeirC Skew NumUp NumDn MinLoCord MaxHiCord MaxSubmerge Is_Ogee
50,12,2.6,0, 6, 8, , , 0.95, 0, 0,0,,
       0   188.5   188.5   290.5   290.5  340.16
    2097    2097    2097    2097    2097    2097
                    2095    2095
     100  207.87  207.87  309.87  309.87     407     527     550
    2097    2097    2097    2097    2097    2096    2094    2093
                    2095    2095
BR Coef=-1 , 1 , 0 ,, 0 ,,,0.8,-1,2,0,
WSPro=,,,, 1 ,,,, 0 ,,,, 0 ,,,,-1 ,-1 ,-1 , 0 , 0 , 0 , 0 , 0
BC Design=,, 0 ,, 0 ,,,,,,

Type RM Length L Ch R = 1 ,379458.8,150.31,140.82,71.36
XS GIS Cut Line= 6
 1031685.7839466  656624.3773104 1031528.2959661  656663.1787087
 1031419.8803379  656650.6253072 1031250.9802099  656596.9880898
 1031094.6334533   656591.282001  1030704.235397  656637.8296105
#Sta/Elev= 30
       0  2112.1   11.55 2105.14   48.81 2104.39   97.23 2101.62  107.77 2101.42
  134.75 2092.79  152.27 2092.47  200.84 2090.48  208.96  2090.8   217.2 2091.67
  233.51 2090.12  242.82 2086.64  250.44 2085.36   259.3 2084.73  267.87 2084.82
  283.16 2086.65   297.1 2087.99  338.01 2089.67  401.29 2089.51  451.02 2091.51
  505.26 2091.69  545.73 2093.49  587.88 2093.42  613.98 2092.68  722.09 2091.07
  783.49 2090.83  837.97 2091.13  868.85 2090.73     968    2094    1001    2116
#Mann= 3 , 0 , 0
       0    .055       0  242.82    .045       0  283.16    .055       0
#XS Ineff= 3 ,-1
       0  187.65    2094  330.17  559.97    2094  559.97    1001    2095
Permanent Ineff=
       F       F       F
Bank Sta=242.82,283.16
Exp/Cntr=0.5,0.3

Type RM Length L Ch R = 1 ,379318.0,808.34,609.12,390.26
XS GIS Cut Line= 6
 1031563.9654157  656468.2038379 1031511.5238743  656511.4680982
 1031261.1155936  656506.2239592 1031230.9616959   656561.287555
 1031013.3293672  656545.5550774 1030709.1684876  656647.8160756
#Sta/Elev= 30
       0 2148.84    6.15 2148.89    8.87 2147.49   61.21 2093.43    74.3 2090.51
   79.14 2090.79   91.71 2089.71   99.83 2090.01  108.84 2086.89  133.69 2085.55
  159.72 2084.12  170.21 2084.88  178.26 2086.97   189.3 2088.65  200.75 2088.73
  218.26 2087.75  246.57 2088.14  273.91 2091.12  312.63 2090.14   393.1 2090.99
  452.27 2093.16  566.69 2092.83  611.29 2091.46  675.72  2090.4  771.31    2090
  873.69 2092.84  883.63 2093.25  896.39  2096.9  914.86 2112.12     921 2116.35
#Mann= 3 , 0 , 0
       0      .1       0  133.69     .05       0  178.26    .055       0
#XS Ineff= 2 , 0
       0                  494.44       0    2100
Permanent Ineff=
       F       F
#Block Obstruct= 1 ,-1
  304.46  408.92  2111.7
Bank Sta=133.69,178.26
Exp/Cntr=0.3,0.1

Type RM Length L Ch R = 1 ,378708.8,395.71,343.33,318.9
XS GIS Cut Line= 6
 1030796.6009311  655954.8171367 1030819.0063476  656015.6319206
 1030918.2304385  656153.2653185 1030899.0257699  656463.7406733
 1030726.1838129  656527.7562051 1030678.1721716   656556.563208
#Sta/Elev= 30
       0 2119.25   36.21 2100.74   49.97 2094.51    54.3 2093.84   99.92 2090.64
  175.49 2090.32  195.79 2089.43  207.64 2088.03  283.49 2087.44  310.48 2088.45
  331.58 2086.43  359.72 2085.14  367.15 2084.41  371.07 2083.34  384.48 2080.04
  395.03 2079.23  412.72 2079.07  431.61  2084.5  449.71 2087.88  467.71 2089.49
  488.66 2089.68  510.65 2091.18  638.57 2089.17  712.21 2090.75  734.06 2091.76
  741.34 2094.34  753.24 2109.87  767.23 2124.85  771.46 2127.85  785.86 2134.87
#Mann= 3 , 0 , 0
       0      .1       0  371.07     .05       0  431.61     .06       0
Bank Sta=371.07,431.61
Exp/Cntr=0.3,0.1

Type RM Length L Ch R = 1 ,378365.5,501.97,459.67,418.95
XS GIS Cut Line= 6
 1030503.7322168  656167.1114049 1030554.7738945  656258.2572449
 1030573.0030564  656339.6808592 1030599.7391849  656387.0766985
 1030599.7391849  656417.4586351 1030591.2322184   656435.687797
#Sta/Elev= 30
       0 2133.25   12.85 2123.11   21.22 2114.29   32.07 2105.85   40.15 2100.31
   58.12 2094.01   83.32 2088.71   90.41 2086.81  103.39 2085.05  148.86  2077.9
  154.62    2077  173.82 2076.95  185.58  2077.7  187.07 2078.27  189.53  2079.2
  195.09 2080.85  199.66 2085.37  202.61 2087.84  208.59 2089.08   213.4 2089.81
  217.87 2091.23  218.96 2091.22  225.62 2091.94  232.39 2092.14  252.78 2091.46
  268.38 2091.59  274.59 2093.02   275.2 2093.26  286.18 2103.02  294.71  2112.6
#Mann= 3 , 0 , 0
       0      .1       0  148.86     .05       0  187.07    .055       0
Bank Sta=148.86,187.07
Exp/Cntr=0.3,0.1

Type RM Length L Ch R = 1 ,377905.9,296.77,301.43,298.37
XS GIS Cut Line= 6
  1030152.516951   656534.125314  1030175.607241  656558.4308633
 1030215.7114033   656568.153089 1030276.4752765  656607.0419618
 1030291.0586303  656619.1947365 1030316.5794389  656632.5628007
#Sta/Elev= 22
       0 2117.27   12.52 2105.59   33.52 2083.13   37.31 2079.55   42.28 2075.68
   44.54 2074.91   57.95 2073.54   65.27 2073.43   73.49 2073.58   91.76 2076.24
  101.99 2077.77   109.9 2079.82  131.71 2085.16  136.09 2087.93  141.45  2091.2
  150.27 2095.77   164.4 2095.94  172.04 2096.46  178.14 2096.03   178.6 2096.06
  186.28 2098.04  194.92 2105.67
#Mann= 3 , 0 , 0
       0      .1       0   37.31     .05       0   91.76     .08       0
Bank Sta=37.31,91.76
Exp/Cntr=0.3,0.1

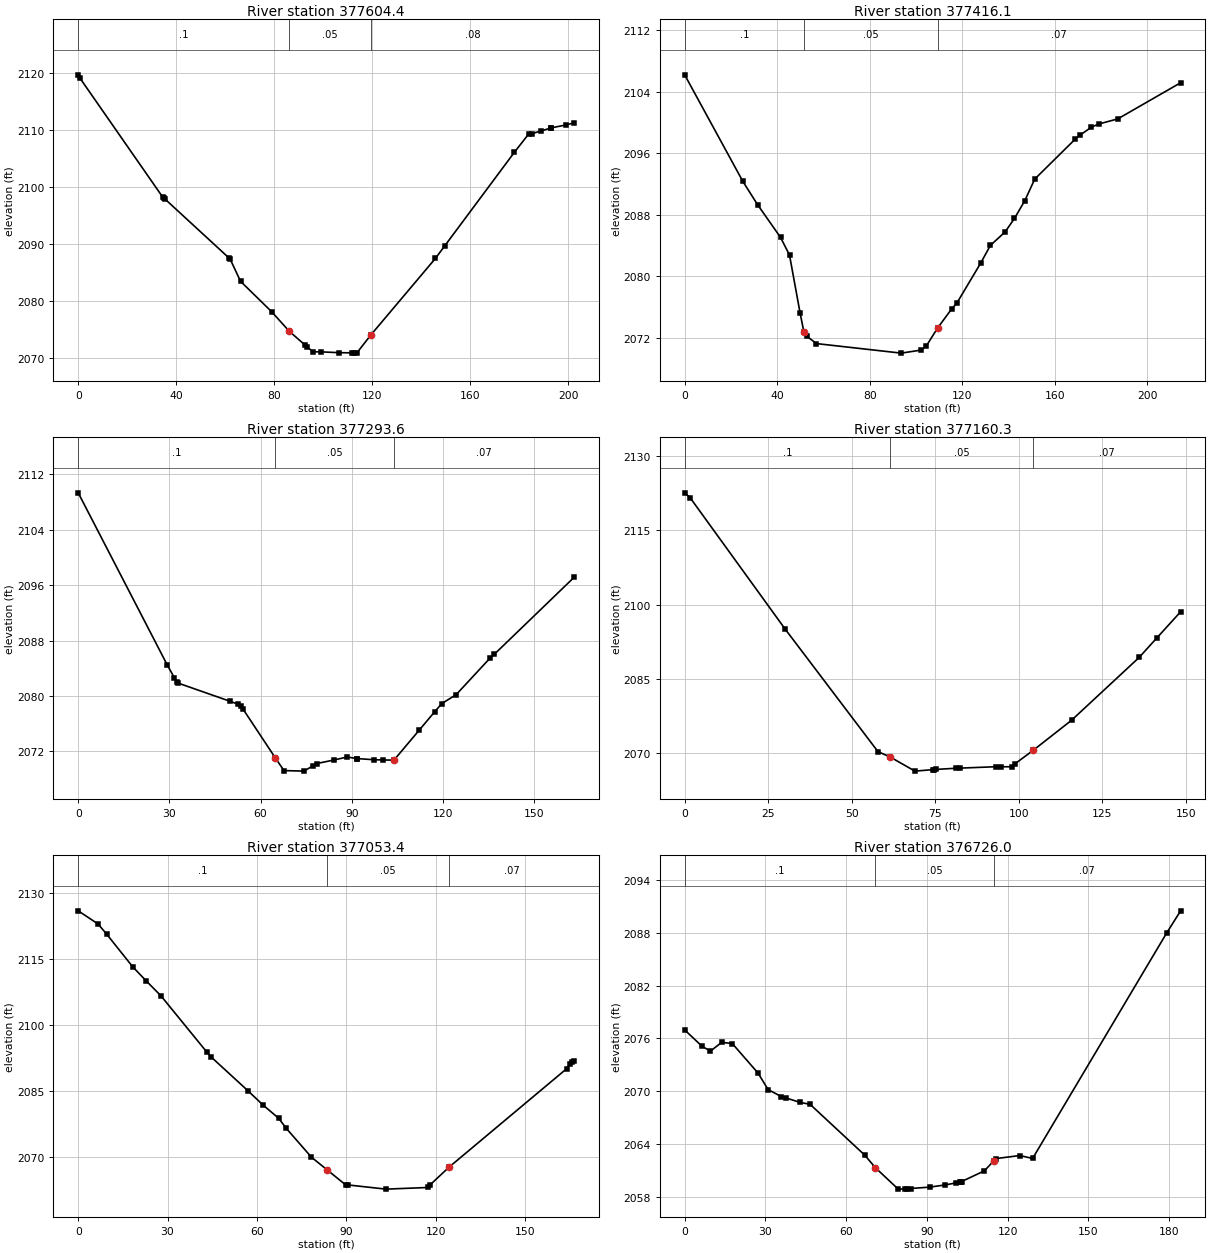
Type RM Length L Ch R = 1 ,377604.4,174.4,188.28,198.09
XS GIS Cut Line= 6
 1030080.8155625  656785.6878035 1030102.6905629  656812.4239017
 1030107.5516606  656839.1600301 1030135.5030483  656853.7433536
 1030216.9266626  656903.5697417 1030219.3572418   656916.937806
#Sta/Elev= 29
       0 2119.63     .55 2119.15   34.54 2098.12   34.84 2097.97   35.31 2097.86
   61.72  2087.4   62.05 2087.22   66.24 2083.38   78.89 2078.06   86.19 2074.58
   92.38 2072.26   93.25 2071.93   95.78 2071.02   99.24    2071  106.37 2070.86
  111.83 2070.83  112.49 2070.81  113.61 2070.78  119.45    2074  145.72  2087.4
  149.62 2089.66  177.99 2106.06  183.82 2109.27  185.23 2109.33  188.74 2109.76
  192.79 2110.29  192.96 2110.32  199.09 2110.84  202.33 2111.21
#Mann= 3 , 0 , 0
       0      .1       0   86.19     .05       0  119.45     .08       0
Bank Sta=86.19,119.45
Exp/Cntr=0.3,0.1

Type RM Length L Ch R = 1 ,377416.1,82.99,122.53,142.91
XS GIS Cut Line= 6
  1029967.794722  656924.2294828 1030010.3294635  656989.8544841
 1030057.7252725  657038.4655826 1030066.2322389  657059.1252935
 1030068.6627878   657083.430873 1030063.8016598  657104.0905838
#Sta/Elev= 27
       0 2106.22   25.14 2092.36   31.54 2089.32   41.42 2085.08    45.3 2082.79
   49.87 2075.26   51.56 2072.73   52.75 2072.23   56.96 2071.27   93.57 2070.03
  102.28 2070.43  104.34 2070.92  109.34 2073.31  115.51 2075.83  117.57 2076.51
  127.91 2081.73  132.12 2084.04   138.5  2085.8  142.51 2087.54  147.02 2089.87
  151.28 2092.66  168.68 2097.83  170.95  2098.4  175.77 2099.41   178.9 2099.82
  187.17 2100.49  214.33 2105.19
#Mann= 3 , 0 , 0
       0      .1       0   51.56     .05       0  109.34     .07       0
Bank Sta=51.56,109.34
Exp/Cntr=0.3,0.1

Type RM Length L Ch R = 1 ,377293.6,105.97,133.26,161.47
XS GIS Cut Line= 6
 1029916.7530746  656923.0141933 1029916.7530746  656954.6114194
 1029913.1072361  656975.2711303 1029916.7530746  656999.5766796
 1029919.1836234  657059.1252935 1029913.1072361  657084.6461323
#Sta/Elev= 28
       0 2109.34   29.31 2084.46    31.6 2082.65   32.56 2081.94   32.68 2081.88
    50.1  2079.2   52.58  2078.8   53.46  2078.6   54.27 2078.07   64.79 2071.09
    67.7 2069.21    74.3 2069.13   77.18 2069.89   78.54 2070.23   84.19 2070.74
   88.49 2071.17   91.78 2070.94   91.89 2070.94   97.19 2070.78  100.31 2070.74
   103.9 2070.72  112.19 2075.04  117.36 2077.74  119.65 2078.89  124.36 2080.18
  135.41 2085.41  136.96 2086.03  163.19 2097.14
#Mann= 3 , 0 , 0
       0      .1       0   64.79     .05       0   103.9     .07       0
Bank Sta=64.79,103.9
Exp/Cntr=0.3,0.1

Type RM Length L Ch R = 1 ,377160.3,114.95,106.93,95.32
XS GIS Cut Line= 6
 1029851.1280733  656912.0766779  1029821.961396  656943.6739041
 1029798.8711061   656974.055871 1029774.5655568  656995.9308714
 1029755.1211053  657015.3752926 1029751.4752971    657021.45168
#Sta/Elev= 20
       0 2122.62    1.63 2121.63   30.05 2095.05   57.84 2070.23   61.56 2069.11
   68.92 2066.27   74.44 2066.58   74.51 2066.58   75.27 2066.62   81.17 2066.85
   82.47 2066.88   93.08 2067.16   94.65 2067.16   97.83 2067.15   98.96  2067.8
   104.3 2070.47  115.82 2076.58  136.02 2089.28  141.37 2093.27  148.45 2098.53
#Mann= 3 , 0 , 0
       0      .1       0   61.56     .05       0   104.3     .07       0
Bank Sta=61.56,104.3
Exp/Cntr=0.3,0.1

Type RM Length L Ch R = 1 ,377053.4,319.56,327.43,341.87
XS GIS Cut Line= 6
 1029786.7183314  656847.6669663 1029733.2461049  656879.2641925
 1029719.8780709  656902.3544824 1029701.6489089  656924.2294828
 1029696.7877809  656940.0280959 1029684.6350063  656970.4100325
#Sta/Elev= 24
       0 2125.88    6.63 2122.91    9.51 2120.63   18.29  2113.2   22.81 2110.01
   27.78 2106.61   43.12 2093.91   44.63 2092.75   57.02 2085.07   62.11 2081.82
    67.3 2078.86   69.79 2076.63   78.31 2070.03   83.55 2067.17    89.9  2063.7
   90.61 2063.73  103.33 2062.78  117.38 2063.15  118.19 2063.76  124.51 2067.75
  164.06  2090.1  165.14 2091.15  165.74 2091.64  166.55 2091.84
#Mann= 3 , 0 , 0
       0      .1       0   83.55     .05       0  124.51     .07       0
Bank Sta=83.55,124.51
Exp/Cntr=0.3,0.1

Type RM Length L Ch R = 1 ,376726.0,510.53,463.05,440.68
XS GIS Cut Line= 3
 1029545.5972651  656644.8846522 1029482.5819689  656677.2925154
 1029405.1632015  656760.1126034
#Sta/Elev= 30
       0 2076.956.459991 2075.099.569992 2074.5413.76999 2075.54   17.69  2075.4
27.25999 2072.04   30.98 2070.1735.87999 2069.37   37.55 2069.22   42.97  2068.7
   46.58 2068.49   66.88 2062.7170.85999 2061.2779.32999 2058.84   82.02 2058.86
82.71999 2058.8883.89999 2058.91   91.12 2059.07   96.81 2059.32  100.82 2059.55
  102.31  2059.6  102.73 2059.68  102.86  2059.7  111.33 2060.92  114.79 2062.05
  115.77 2062.32  124.47 2062.66  129.25 2062.33  179.01 2087.96  184.23  2090.5
#Mann= 3 , 0 , 0
       0      .1       070.85999     .05       0  114.79     .07       0
Bank Sta=70.85999,114.79
Exp/Cntr=0.3,0.1

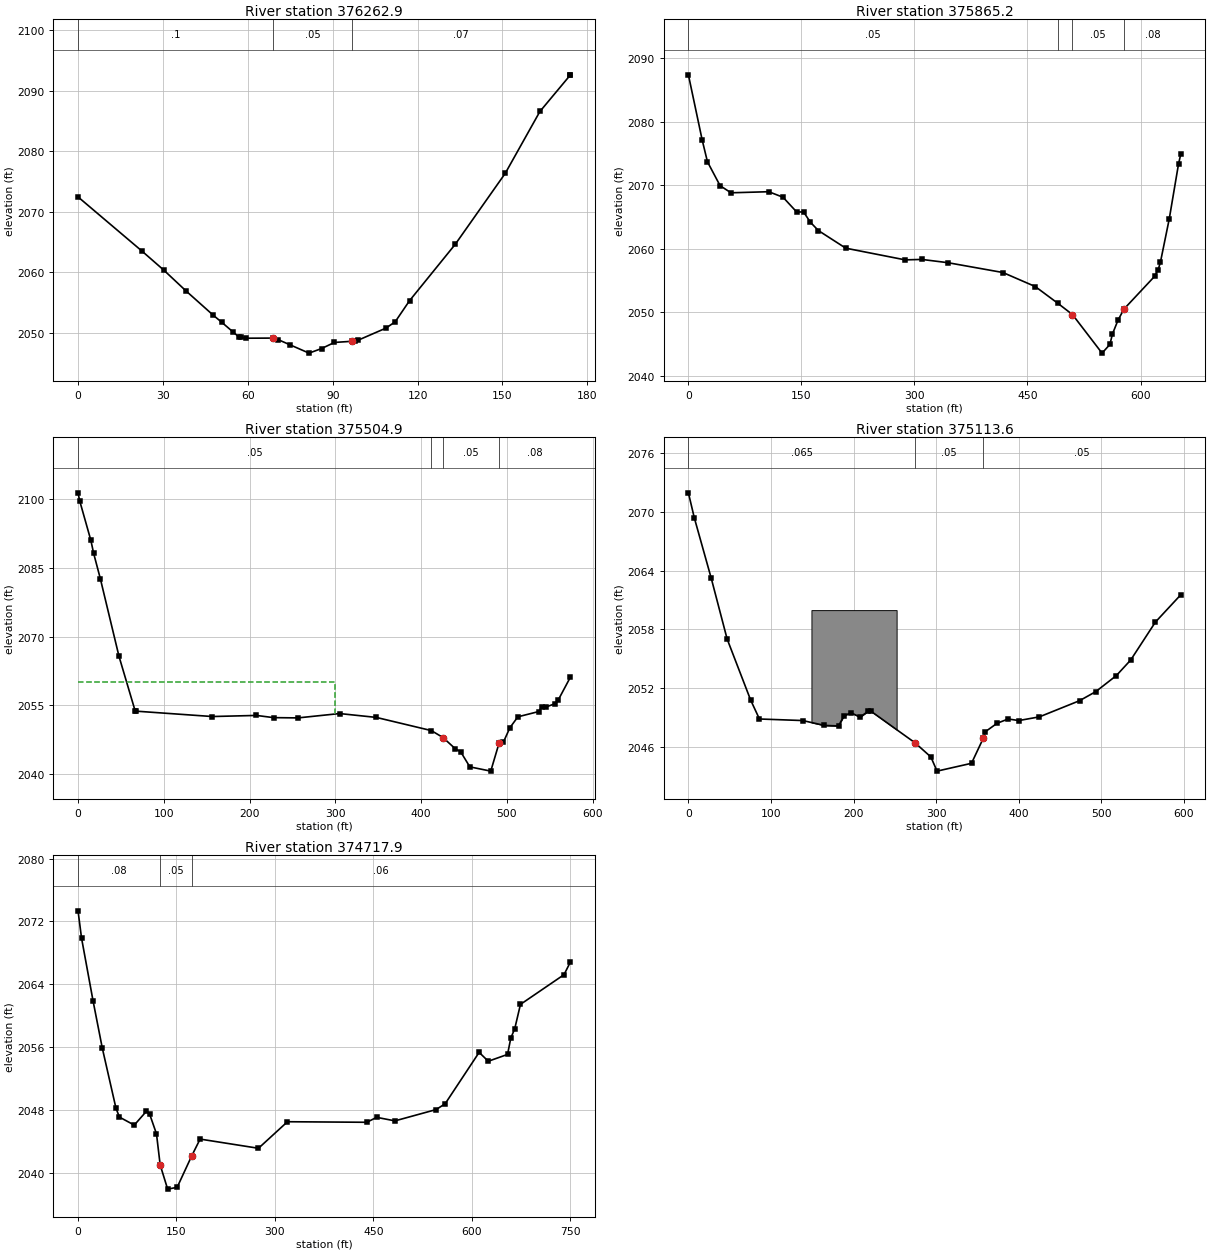
Type RM Length L Ch R = 1 ,376262.9,452.49,397.7,364.7
XS GIS Cut Line= 4
 1029066.6810383  656558.4636738  1029043.275356   656603.474578
 1029036.0736053  656666.4898742 1029028.8718546  656725.9043101
#Sta/Elev= 27
       0 2072.45    22.6 2063.48   30.33 2060.32   38.15 2056.89   47.75 2052.88
   50.73 2051.72   54.86 2050.06   56.77  2049.3   57.54 2049.18   59.41 2049.06
   68.99 2049.08   70.64 2048.84   74.89 2047.97   81.63 2046.59   86.07 2047.35
   90.61 2048.36   96.84 2048.55   98.02  2048.6   98.77 2048.69  108.81 2050.73
  112.07 2051.77  117.15 2055.27  133.33 2064.62  150.97 2076.35  163.22 2086.59
  173.85 2092.56  174.01 2092.66
#Mann= 3 , 0 , 0
       0      .1       0   68.99     .05       0   96.84     .07       0
Bank Sta=68.99,96.84
Exp/Cntr=0.3,0.1

Type RM Length L Ch R = 1 ,375865.2,333.12,360.33,364.57
XS GIS Cut Line= 6
 1028742.6023766   656264.992445 1028634.5761459  656297.4003082
 1028591.3656718   656448.637013 1028576.9621703  656576.4680354
 1028670.5848995  656704.2990579 1028699.3918722   656796.121357
#Sta/Elev= 30
       0 2087.3818.35004 2077.0925.29004 2073.69   42.06 2069.9356.54004 2068.81
  106.63 2068.98  125.57 2068.11  143.69 2065.79  152.87 2065.79  161.92 2064.17
  172.57 2062.86  208.85 2060.09  287.67 2058.25  309.71 2058.32  344.19 2057.81
  417.36 2056.26  460.34 2054.05  490.21 2051.42   509.7 2049.64  548.93 2043.57
  559.43 2044.94  562.59 2046.53  569.99 2048.72  577.92 2050.49  618.62 2055.65
   623.4  2056.7  626.44  2057.9  638.13  2064.7  650.42 2073.33  653.45 2074.92
#Mann= 4 ,-1 , 0
       0     .05       0  490.21     .08       0   509.7     .05       0
  577.92     .08       0
Bank Sta=509.7,577.92
Exp/Cntr=0.3,0.1

Type RM Length L Ch R = 1 ,375504.9,383.61,391.3,447.48
XS GIS Cut Line= 4
 1028168.2629602  656371.2182153 1028209.6730345  656432.4330814
 1028342.9053473  656860.9370833 1028387.9162818  656886.1431957
#Sta/Elev= 30
       0 2101.411.859985 2099.7114.96997 2091.0218.23999 2088.1725.95996  2082.7
47.73999 2065.7366.53998 2053.8467.09998 2053.75  156.48 2052.57  208.09 2052.81
     228 2052.33  256.48 2052.27  304.99 2053.22  347.72 2052.38  412.05  2049.5
  425.72 2047.97  440.06 2045.51   446.2 2044.88  456.92 2041.58  481.32 2040.65
     491 2046.77  496.04 2046.98  503.71 2050.15  512.98 2052.51  537.31 2053.66
  540.72 2054.68  545.74 2054.65  556.05 2055.36  559.75 2056.09  574.23 2061.18
#Mann= 4 ,-1 , 0
       0     .05       0  412.05     .08       0  425.72     .05       0
     491     .08       0
#XS Ineff= 2 , 0
       0     300    2060               0
Permanent Ineff=
       F       F
Bank Sta=425.72,491
Exp/Cntr=0.3,0.1

Type RM Length L Ch R = 1 ,375113.6,507.11,395.69,344.09
XS GIS Cut Line= 5
 1027885.5943727  656598.0732876 1027890.9956631  656670.0907647
 1027972.0153512  657001.3711771 1028094.4450531  657015.7746483
 1028144.8572779  657048.1825418
#Sta/Elev= 30
       0 2071.97    7.08 2069.44   27.66 2063.24   46.91 2057.03   75.38 2050.79
   86.04 2048.85  138.57 2048.69  164.75 2048.19  181.85 2048.14  188.44 2049.18
  196.99 2049.49  207.86 2049.04  217.78 2049.64  221.52 2049.62  274.61 2046.41
   293.7 2044.97  301.19 2043.52  342.94 2044.32   357.1 2046.86  359.56 2047.54
  373.89 2048.41  387.31 2048.85  400.26 2048.69  425.27 2049.07  473.81 2050.72
  493.54 2051.65  518.42 2053.29   535.8 2054.88  565.74 2058.76  596.47 2061.55
#Mann= 3 , 0 , 0
       0    .065       0  274.61     .05       0   357.1     .05       0
#XS Ineff= 2 , 0
       0  217.78 2049.64               0
Permanent Ineff=
       F       F
#Block Obstruct= 1 ,-1
  149.04  252.23 2059.98
Bank Sta=274.61,357.1
Exp/Cntr=0.3,0.1

Type RM Length L Ch R = 1 ,374717.9,445,383.1,136
XS GIS Cut Line= 6
  1027460.691231  656965.3624235  1027561.515711  657003.1716073
 1027703.7502349  657188.6166053 1027899.9978439  657206.6209973
 1028009.8245047  657251.6319015 1028031.4297569  657339.8533101
#Sta/Elev= 30
       0 2073.34    5.32 2069.88   22.88 2061.88   36.96 2055.87   57.87 2048.19
   63.11 2047.08   85.71 2046.06  103.95  2047.8  108.95  2047.5  119.55 2044.95
  125.17 2040.99  136.57 2037.91  151.05 2038.14  173.42 2042.17  186.03 2044.28
  274.97 2043.11  319.18 2046.49  440.16 2046.42  455.02 2047.05  482.98  2046.6
  545.77 2048.04  559.51 2048.78  611.27 2055.32  625.24 2054.19  654.58 2055.06
  659.59 2057.16  665.48 2058.31  674.25 2061.43  740.61 2065.21  750.42 2066.83
#Mann= 3 , 0 , 0
       0     .08       0  125.17     .05       0  173.42     .06       0
#XS Ineff= 2 , 0
       0                  186.03       0 2044.28
Permanent Ineff=
       F       F
Bank Sta=125.17,173.42
Exp/Cntr=0.3,0.1