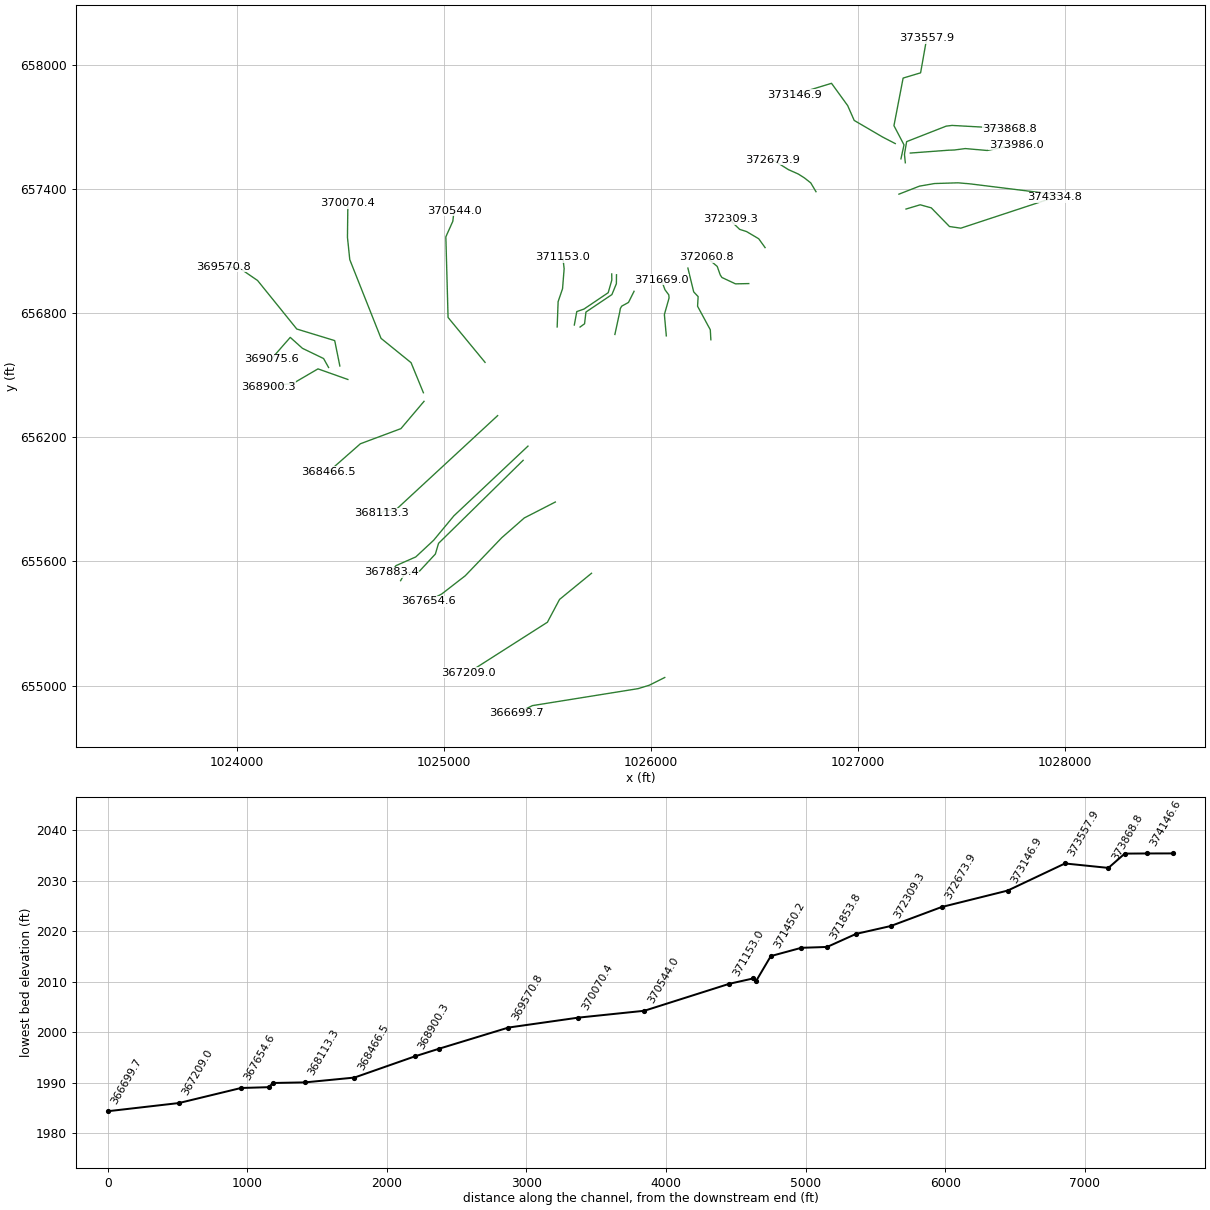
HEC-RAS study lds_broad_rvr.prj: Upper_Broad 3-06-07

--- lds_broad_rvr.g05 (geometry) --- (continued)

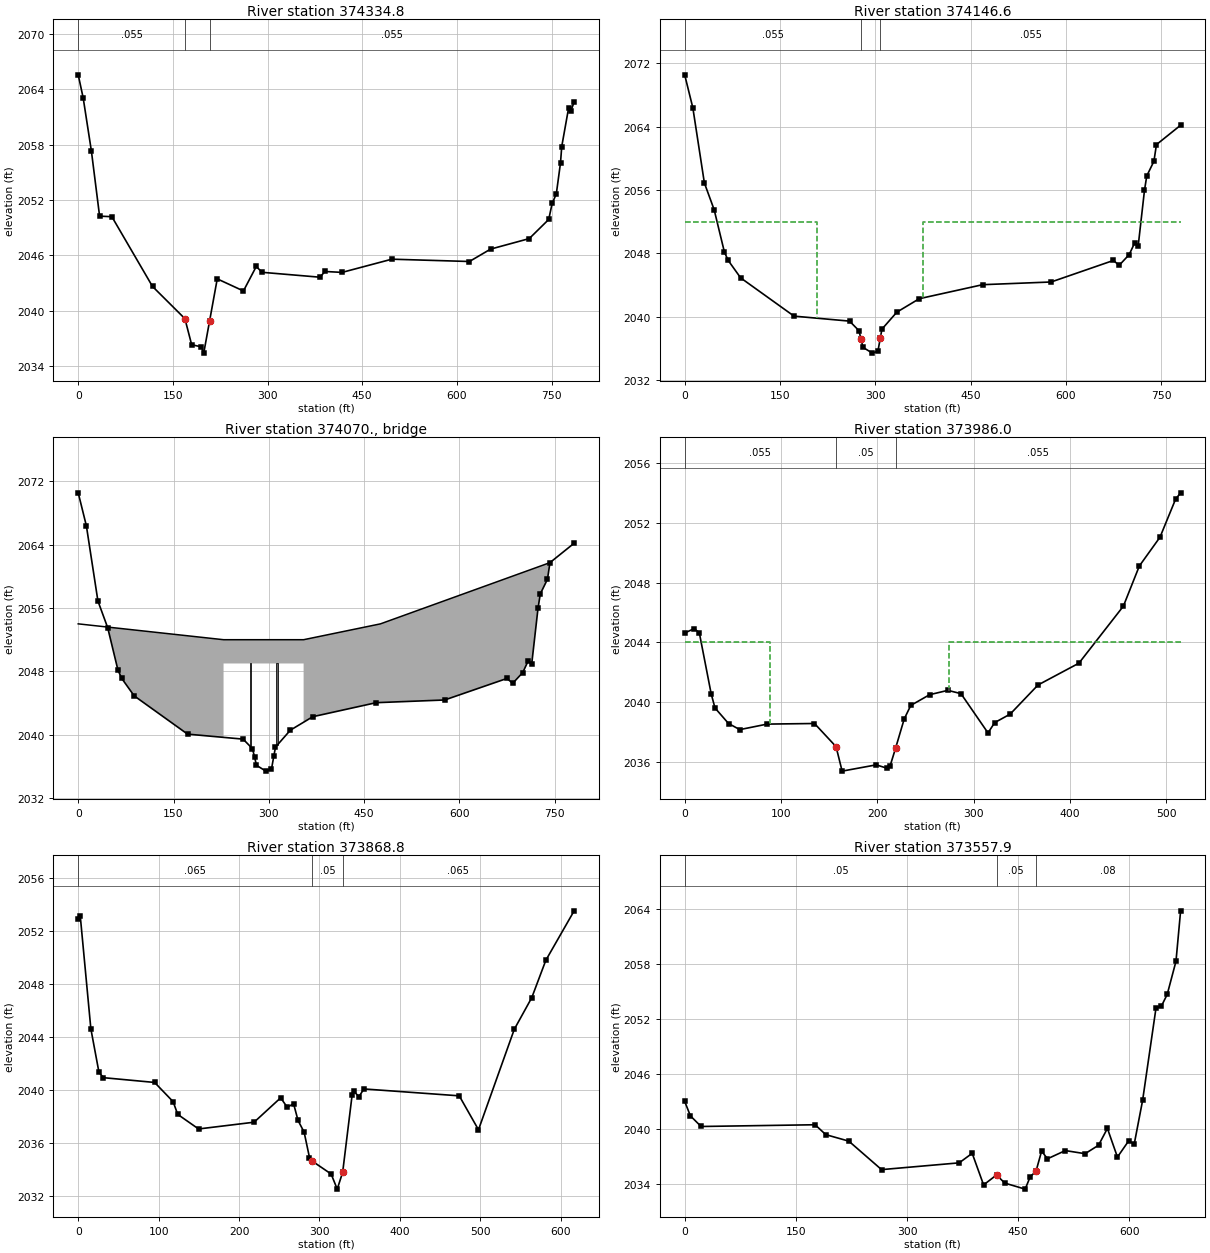
Type RM Length L Ch R = 1 ,374334.8,94,188.2,204.7
XS GIS Cut Line= 6
 1027232.7546536  657302.2603002 1027301.2276899  657322.8022081
  1027354.864877  657307.9663891 1027442.7385973  657217.8102211
 1027497.5170384  657209.8217148 1027950.8638765  657359.1242656
#Sta/Elev= 30
       0 2065.55    7.87 2063.05   20.91 2057.29   33.88 2050.25   53.32 2050.19
  117.72 2042.64  169.06 2039.15  179.77 2036.33  195.13  2036.1  198.91 2035.42
  208.28 2038.94  220.32 2043.46  261.82 2042.15  282.15  2044.8  291.33 2044.17
  383.01 2043.64  391.04 2044.26  418.12 2044.16  496.95 2045.59  619.94 2045.34
  653.39 2046.68  714.73 2047.82  745.56 2049.89  751.04 2051.63  757.63 2052.66
  764.26 2056.02   766.2 2057.78   777.1 2061.96   780.6 2061.64  785.89  2062.6
#Mann= 3 , 0 , 0
       0    .055       0  169.06     .05       0  208.28    .055       0
Bank Sta=169.06,208.28
Exp/Cntr=0.5,0.3

Type RM Length L Ch R = 1 ,374146.6,168,160.6,169
XS GIS Cut Line= 6
 1027198.5181506  657374.1569778 1027297.8040487  657412.9583458
 1027370.8419198  657425.5117474  1027483.822413  657428.9353886
 1027540.6479986   657424.108978 1027967.1100622  657371.3089124
#Sta/Elev= 30
       0 2070.54   12.86 2066.37      31 2056.89    46.4 2053.51   62.54 2048.16
    68.5 2047.11   88.09 2044.91   172.1 2040.08  259.47 2039.45  274.09 2038.26
  277.65 2037.18  280.46 2036.15  295.27 2035.41  304.13 2035.66  307.85  2037.3
  310.45 2038.44  333.87 2040.58  369.16 2042.28  468.96 2044.05  576.71 2044.39
  674.79 2047.11  683.74 2046.49  699.59 2047.85  707.96 2049.29  713.71 2048.93
  723.64 2055.97  727.23 2057.78  738.49 2059.63  742.45 2061.73   780.5 2064.18
#Mann= 3 , 0 , 0
       0    .055       0  277.65     .05       0  307.85    .055       0
#XS Ineff= 2 , 0
       0  208.75    2052  374.75       0    2052
Permanent Ineff=
       F       F
Bank Sta=277.65,307.85
Exp/Cntr=0.5,0.3

Type RM Length L Ch R = 3 ,374070. ,,,
BEGIN DESCRIPTION:
STR_149
END DESCRIPTION:
Bridge Culvert--1,0,-1,-1, 0
Deck Dist Width WeirC Skew NumUp NumDn MinLoCord MaxHiCord MaxSubmerge Is_Ogee
120,30,2.6,0, 7, 7, , , 0.95, 0, 0,0,,
       0  228.75  228.75  354.75  354.75  475.64  742.45
    2054    2052    2052    2052    2052    2054 2061.73
                    2049    2049
       0   118.7   118.7   244.7   244.7  362.88  514.19
    2054    2052    2052    2052    2052    2054 2053.99
                    2049    2049
Pier Skew, UpSta & Num, DnSta & Num=  ,270.75, 2 ,160.7, 2 , 0 , 0 , 0 ,,
       2       2
    2030    2049
       2       2
    2030    2049
Pier Skew, UpSta & Num, DnSta & Num=  ,312.75, 2 ,202.7, 2 , 0 , 0 , 0 ,,
       2       2
    2030    2049
       2       2
    2030    2049
BR Coef=-1 , 1 , 0 ,, 0 ,,,0.8,0,2,0,
WSPro=,,,, 1 ,,,, 0 ,,,, 0 ,,,,-1 ,-1 ,-1 , 0 , 0 , 0 , 0 , 0
BC Design=,, 0 ,, 0 ,,,,,,

Type RM Length L Ch R = 1 ,373986.0,72,117.2,112
XS GIS Cut Line= 6
 1027253.2965615  657572.7287437 1027437.0325387  657586.4233691
 1027466.7041766  657587.5645627 1027519.2001701  657594.4118754
 1027624.5865489  657585.2168573 1027764.0328775  657612.2938334
#Sta/Elev= 30
       0 2044.63    9.69 2044.92   15.15 2044.66   27.53 2040.55   31.46 2039.61
   45.49 2038.57   57.21 2038.16   85.57 2038.53  134.73 2038.57  157.09 2037.02
  163.42 2035.38  198.79  2035.8  209.74 2035.58   213.3 2035.75  218.922036.924
  227.83 2038.87  234.64 2039.78  254.24  2040.5  273.19 2040.79  286.73 2040.57
   314.8 2037.94  321.77 2038.63  337.83  2039.2  366.73 2041.15  409.16 2042.61
  455.31 2046.43  471.88 2049.12  493.32 2051.05  509.53  2053.6  514.72 2054.02
#Mann= 3 , 0 , 0
       0    .055       0  157.09     .05       0  218.92    .055       0
#XS Ineff= 2 , 0
       0    88.7    2044   274.7       0    2044
Permanent Ineff=
       F       F
Bank Sta=157.09,218.92
Exp/Cntr=0.5,0.3

Type RM Length L Ch R = 1 ,373868.8,121.83,311.07,480.7
XS GIS Cut Line= 6
 1027229.3410008  657525.7759974 1027225.2230424  657566.9555204
 1027235.7051155  657627.9760964 1027426.7615847  657702.8275036
 1027455.2919989  657706.2511448 1027734.2482189  657690.8169884
#Sta/Elev= 30
       0 2052.96    2.56 2053.15   15.72 2044.65   25.79 2041.37   31.34 2040.96
   95.03  2040.6  118.02 2039.15  123.76 2038.19   149.7 2037.09  218.74  2037.6
  251.79 2039.44  260.06 2038.72  267.82    2039  273.41 2037.73  280.96 2036.85
  287.65 2034.93  291.38 2034.65  314.56 2033.69  322.14 2032.55  328.89 2033.82
  340.63 2039.64  342.62 2039.93  349.21 2039.53  355.29 2040.11  473.89 2039.59
  497.82 2037.03  542.34 2044.61   564.1    2047   581.6 2049.82   616.8 2053.55
#Mann= 3 , 0 , 0
       0    .065       0  291.38     .05       0  328.89    .065       0
Bank Sta=291.38,328.89
Exp/Cntr=0.3,0.1

Type RM Length L Ch R = 1 ,373557.9,127.65,410.93,509.09
XS GIS Cut Line= 6
 1027208.2165252  657544.6952389 1027222.9857243  657612.2116255
 1027174.4583167  657705.0466609 1027218.7659445  657935.0243291
 1027303.1614202  657960.3429779 1027332.6998488  658127.0240696
#Sta/Elev= 30
       0 2043.01 7.72998 2041.4322.15997 2040.27  175.98 2040.46  190.34 2039.38
  221.45 2038.67  265.61 2035.56  370.34  2036.3  387.87 2037.34  403.26 2033.89
  420.77 2034.98  431.76 2034.09  459.33 2033.43  466.24  2034.8  473.92 2035.37
  481.55 2037.59  489.39 2036.74   513.5 2037.64  540.18  2037.3  558.32 2038.22
  570.29 2040.06  583.82 2036.93  598.91 2038.69  606.49 2038.36   617.8 2043.13
  635.85 2053.21  642.91 2053.38  650.96 2054.69   662.8 2058.31  669.06 2063.82
#Mann= 3 , 0 , 0
       0     .05       0  420.77     .05       0  473.92     .08       0
#XS Ineff= 4 ,-1
     210  387.87 2037.34     395  420.77 2034.98  481.55  558.89 2037.59
  570.29     640 2040.06
Permanent Ineff=
       T       F       F       F
Bank Sta=420.77,473.92
Exp/Cntr=0.3,0.1

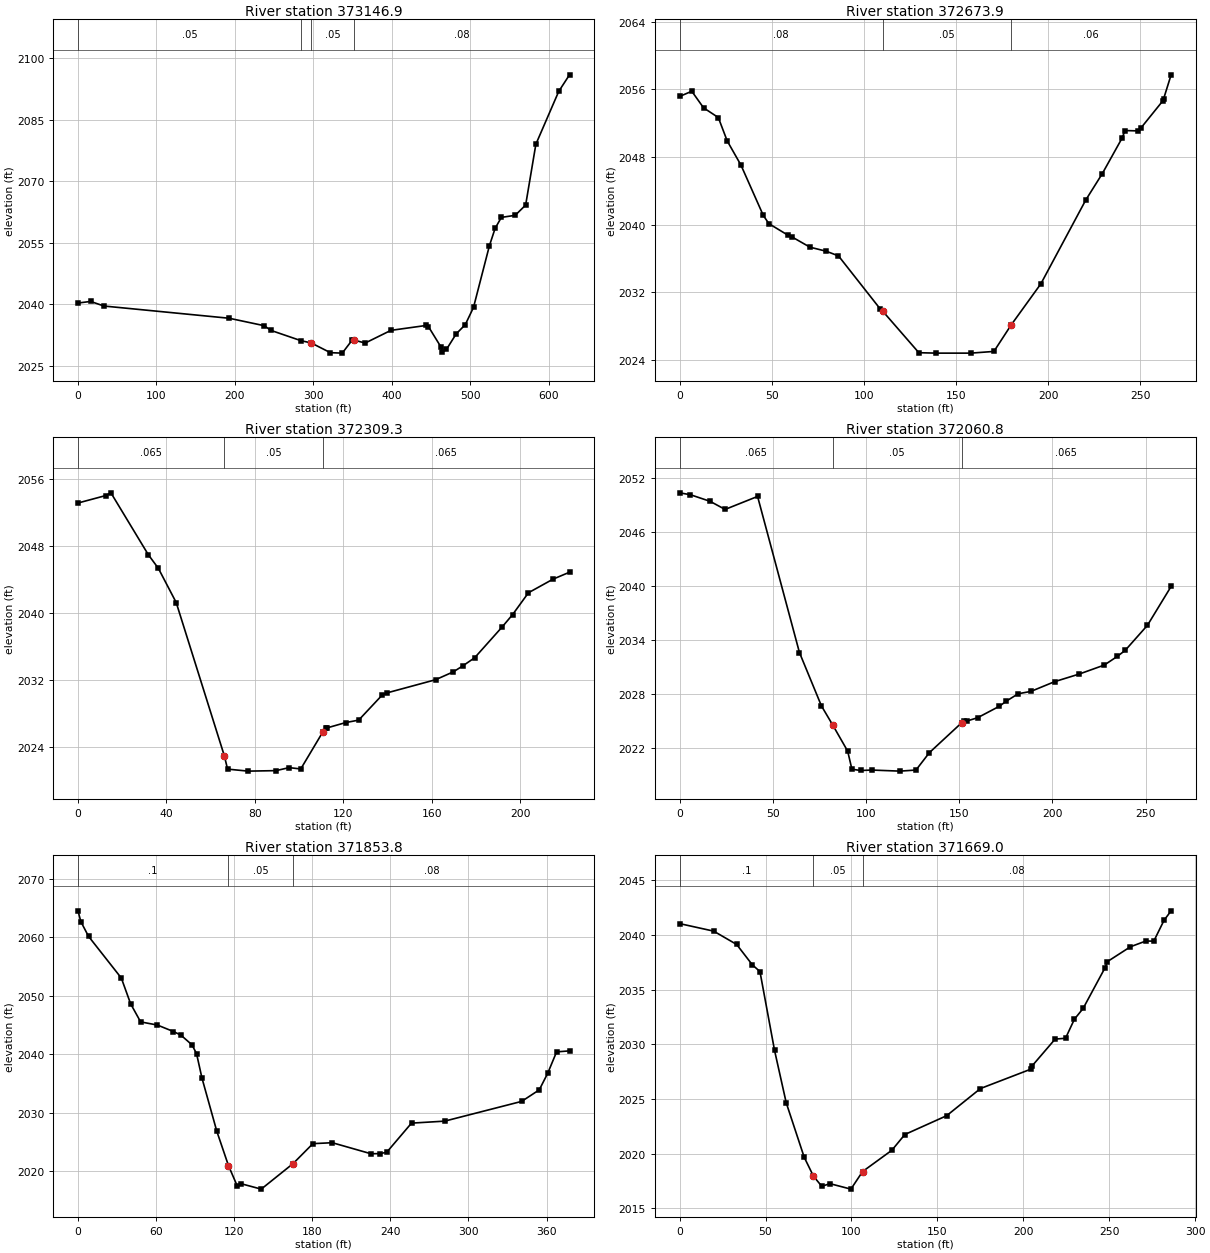
Type RM Length L Ch R = 1 ,373146.9,428.53,472.99,488.71
XS GIS Cut Line= 6
 1027180.7879865   657618.541265 1027119.6012394  657650.1895836
 1026982.4585762  657730.3652794  1026950.810288  657802.1014458
 1026872.7444518  657909.7057106 1026693.4040508  657854.8486333
#Sta/Elev= 30
       0 2040.2716.09003 2040.6633.14001 2039.54  192.82 2036.56  237.36 2034.75
  245.87 2033.61  284.35 2031.09  297.28 2030.55  321.79 2028.17  336.89 2028.06
  349.56 2031.24  351.79 2031.24  366.15 2030.52  398.96 2033.61  444.08 2034.81
  446.69 2034.55  463.01 2029.47  464.64 2028.31  469.76 2028.97  482.24 2032.77
  493.75    2035  504.24 2039.21  524.58 2054.28  531.82 2058.49  539.77 2061.15
  557.38 2061.65  570.71 2064.15  583.74 2078.97  612.92 2091.87  626.64  2095.9
#Mann= 4 ,-1 , 0
       0     .05       0  284.35     .08       0  297.28     .05       0
  351.79     .08       0
#XS Ineff= 2 , 0
       0                  444.08       0 2034.81
Permanent Ineff=
       F       F
Bank Sta=297.28,351.79
Exp/Cntr=0.3,0.1

Type RM Length L Ch R = 1 ,372673.9,371.64,364.59,371.31
XS GIS Cut Line= 6
 1026797.7954606  657385.9391815 1026772.3961477  657428.7169446
 1026741.6496333  657452.7794421 1026712.2399041   657471.494738
 1026664.1149093  657492.8836044 1026587.9169705  657541.0086295
#Sta/Elev= 30
       0 2055.16    6.61 2055.78      13 2053.82   21.01 2052.67   25.82 2049.91
   33.31 2047.04   45.43 2041.09   48.46 2040.12      59 2038.73   61.16 2038.53
   70.73 2037.34   79.57 2036.86   86.22 2036.31  108.71 2030.08  110.32 2029.75
  129.84 2024.86  139.29 2024.81  158.06 2024.81  170.58 2025.01  179.96 2028.15
  196.06 2033.01  220.43 2042.92  229.35 2046.02  240.06 2050.21  241.76 2051.13
  248.78 2051.09  250.42 2051.45  262.08  2054.6  262.71 2054.91  266.74 2057.72
#Mann= 3 , 0 , 0
       0     .08       0  110.32     .05       0  179.96     .06       0
Bank Sta=110.32,179.96
Exp/Cntr=0.3,0.1

Type RM Length L Ch R = 1 ,372309.3,249.18,248.54,208.07
XS GIS Cut Line= 6
 1026551.8232244  657115.9044479   1026521.07671  657158.6822413
 1026462.2572517  657193.4391719 1026428.8371063  657204.1336051
 1026395.4169912  657236.2169653 1026386.0593432  657252.2586302
#Sta/Elev= 28
       0 2053.17   12.51 2054.06   14.89 2054.39   31.78 2046.99   36.36 2045.34
   44.42 2041.25   66.19 2022.89   67.66 2021.29   76.96 2021.05   89.62 2021.11
   95.49 2021.47  100.76 2021.31  110.83 2025.78  112.21 2026.18   112.8 2026.24
  121.13 2026.87  126.96 2027.16  137.69 2030.19  139.72 2030.42  161.74    2032
  169.82 2032.95  174.07 2033.66  179.42 2034.63  191.79  2038.3  196.55 2039.79
  203.76 2042.42  214.89 2044.05  222.33 2044.88
#Mann= 3 , 0 , 0
       0    .065       0   66.19     .05       0  110.83    .065       0
Bank Sta=66.19,110.83
Exp/Cntr=0.3,0.1

Type RM Length L Ch R = 1 ,372060.8,235.44,207.03,155.83
XS GIS Cut Line= 6
 1026472.9517152  656942.1197343 1026408.7850251  656940.7829188
 1026343.2815498  656971.5294634 1026335.2607174  656983.5607121
 1026320.5558679  657025.0016597 1026268.4204568  657069.1162686
#Sta/Elev= 30
       0 2050.35    5.81 2050.14   16.33 2049.41   24.41 2048.51   41.83 2049.95
   64.29 2032.64   76.09 2026.72   82.12 2024.61   90.15 2021.71   92.43  2019.7
   97.19 2019.56     103 2019.61  118.22 2019.49   126.8 2019.61     134 2021.54
  151.35 2024.86  152.53 2025.08  154.34 2025.06  159.84 2025.41   171.6 2026.69
  175.17 2027.24  181.64 2028.07  188.45 2028.33  201.16 2029.41  214.44 2030.26
   227.8 2031.25  234.78 2032.21  239.03 2032.88  250.96 2035.66  263.66 2039.97
#Mann= 3 , 0 , 0
       0    .065       0   82.12     .05       0  151.35    .065       0
Bank Sta=82.12,151.35
Exp/Cntr=0.3,0.1

Type RM Length L Ch R = 1 ,371853.8,195.38,184.79,124.41
XS GIS Cut Line= 6
 1026289.8093535  656670.7482154 1026287.1357225  656718.8732102
 1026225.6426635  656832.5016804 1026228.3162945  656879.2898597
 1026206.9273978  656902.0155719 1026178.8544841  657016.9808272
#Sta/Elev= 30
       0 2064.52    2.18 2062.68    8.08 2060.16   33.29 2053.02   40.42 2048.62
   48.12 2045.52   60.99 2044.98   73.34 2043.87    79.1 2043.25   87.54  2041.6
   91.07  2040.1   95.23 2035.92  106.67 2026.79  115.59 2020.94  122.44  2017.4
  125.55 2017.82  140.77 2016.91   165.3 2021.29  180.46 2024.69  195.36 2024.85
  225.13 2022.96  232.36 2022.99  237.23 2023.23  256.22  2028.2  281.67 2028.54
  340.85 2031.92  354.36 2033.89  360.88 2036.74  367.68 2040.39  377.61 2040.56
#Mann= 3 , 0 , 0
       0      .1       0  115.59     .05       0   165.3     .08       0
#XS Ineff= 2 , 0
       0                  195.36       0 2024.85
Permanent Ineff=
       F       F
Bank Sta=115.59,165.3
Exp/Cntr=0.3,0.1

Type RM Length L Ch R = 1 ,371669.0,228.39,218.82,187.22
XS GIS Cut Line= 6
 1026074.5836317  656689.4634811  1026065.226014   656792.397518
 1026087.9516959  656872.6058427 1026086.6149107  656887.3106922
 1026067.8996148  656912.7100051 1026050.5211343  656960.8349999
#Sta/Elev= 30
       0 2041.05   19.84 2040.36   33.21 2039.14   42.32 2037.28   46.76 2036.66
   55.26 2029.44   62.06 2024.64   72.51 2019.66   77.89 2017.93   82.73    2017
   87.52 2017.24   99.69 2016.74  106.49 2018.35  123.53  2020.3  131.08 2021.74
  155.39 2023.46  175.09 2025.95  204.52 2027.73   205.3 2028.05  218.56 2030.48
  224.59 2030.55  229.77  2032.3  234.82 2033.28  247.67 2037.03  248.96 2037.57
  262.37 2038.93  271.42 2039.46  275.95 2039.44  281.91 2041.35  286.04 2042.22
#Mann= 3 , 0 , 0
       0      .1       0   77.89     .05       0  106.49     .08       0
Bank Sta=77.89,106.49
Exp/Cntr=0.3,0.1

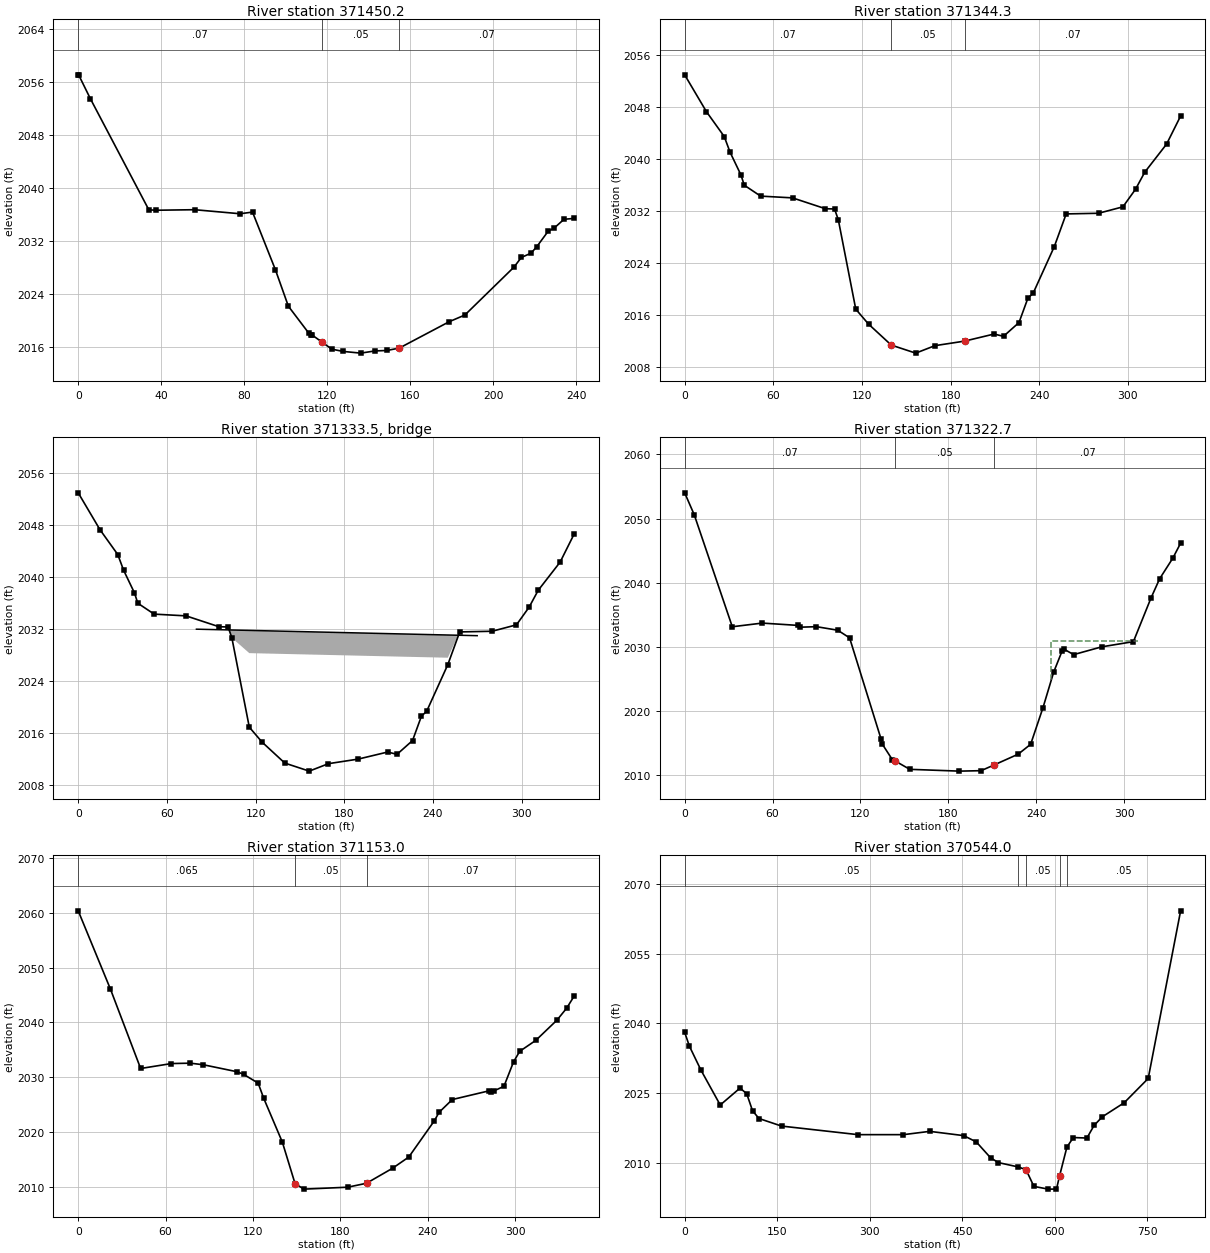
Type RM Length L Ch R = 1 ,371450.2,148.31,105.89,91.13
XS GIS Cut Line= 6
 1025826.1234283  656696.2863373 1025850.0438781  656806.9184895
 1025852.2864326  656821.1212537 1025859.0140657  656833.0814937
 1025891.9047031  656851.0218387 1025918.8152053  656904.8428734
#Sta/Elev= 30
       0 2057.15     .32 2057.07    5.83 2053.56   34.03 2036.75   37.59 2036.69
    56.1 2036.77   77.96 2036.16   83.98 2036.41   94.99 2027.71  101.25 2022.19
  110.96 2018.17  112.21 2017.77  112.63 2017.85  117.65 2016.72  122.17  2015.7
  127.57 2015.36  136.11  2015.1  142.95 2015.43  148.67  2015.5  154.68 2015.86
  178.76 2019.85   186.3 2020.86  209.96  2028.1   213.5 2029.56  218.17  2030.2
   220.9 2031.17  226.49 2033.55  229.14 2033.95  234.05 2035.32  238.94 2035.46
#Mann= 3 , 0 , 0
       0     .07       0  117.65     .05       0  154.68     .07       0
Bank Sta=117.65,154.68
Exp/Cntr=0.5,0.3

Type RM Length L Ch R = 1 ,371344.3,16.13,21.57,17.89
XS GIS Cut Line= 6
 1025657.9326607  656732.1670271 1025679.6105863  656747.8648478
 1025686.3382194   656804.675935  1025811.810186  656889.0385397
 1025833.3396774  656941.6105663 1025833.8403703  656984.6695795
#Sta/Elev= 30
       0    2053   14.74 2047.32   26.76  2043.5   30.72 2041.08   38.06 2037.59
   40.33    2036   51.39 2034.32   72.99 2034.05   95.23 2032.38  101.42 2032.34
  103.98 2030.67  115.78 2016.91  124.42 2014.61   139.8 2011.38  156.35 2010.14
  169.36 2011.29  189.42 2011.99  209.39 2013.08  215.76 2012.73  226.25 2014.85
  232.31 2018.63  235.75 2019.33  250.14 2026.55  258.18 2031.58  280.07 2031.68
  296.57 2032.67  305.11 2035.38  311.33    2038  326.12 2042.33  335.62 2046.66
#Mann= 3 , 0 , 0
       0     .07       0   139.8     .05       0  189.42     .07       0
Bank Sta=139.8,189.42
Exp/Cntr=0.5,0.3

Type RM Length L Ch R = 3 ,371333.5,,,
BEGIN DESCRIPTION:
STR_147
END DESCRIPTION:
Bridge Culvert--1,0,-1,-1, 0
Deck Dist Width WeirC Skew NumUp NumDn MinLoCord MaxHiCord MaxSubmerge Is_Ogee
4.5,12,2.6,0, 2, 2, 2031, , 0.95, 0, 0,0,,
      80     270
    2032    2031
  2028.5  2027.5
      50     309
    2032    2031
  2028.5  2027.5
BR Coef=-1 , 1 , 0 ,, 0 ,,,0.8,0,2,0,
WSPro=,,,, 1 ,,,, 0 ,,,, 0 ,,,,-1 ,-1 ,-1 , 0 , 0 , 0 , 0 , 0
BC Design=,, 0 ,, 0 ,,,,,,

Type RM Length L Ch R = 1 ,371322.7,139.27,169.74,232.9
XS GIS Cut Line= 6
 1025630.0611199  656741.8368287 1025642.0775978  656806.9260262
 1025676.6205338  656818.8786992 1025793.7854842  656898.0508906
 1025811.3094931  656959.1346055 1025810.8088304   656988.675062
#Sta/Elev= 30
       0 2054.02    6.53  2050.6    32.5 2033.16   52.93 2033.73   77.35 2033.37
   78.96 2033.09   89.95 2033.17  104.47 2032.62  112.56 2031.43  134.07 2015.65
  134.66 2014.96  141.67 2012.48  143.59 2012.26  153.66 2010.95  187.49 2010.67
  202.31 2010.74   211.4 2011.65  227.64 2013.31  236.15 2014.85  244.61 2020.58
  251.87 2026.09  257.57 2029.35  259.11 2029.64  265.53 2028.82  284.67 2030.03
  306.29 2030.84  318.28 2037.63  324.22 2040.64  333.21 2043.85  338.52 2046.18
#Mann= 3 , 0 , 0
       0     .07       0  143.59     .05       0   211.4     .07       0
#XS Ineff= 1 ,-1
  250.28  309.64    2031
Permanent Ineff=
       F
Bank Sta=143.59,211.4
Exp/Cntr=0.5,0.3

Type RM Length L Ch R = 1 ,371153.0,548.38,608.93,597.08
XS GIS Cut Line= 5
 1025547.2765362  656732.5939267 1025551.8604701  656854.8317598
 1025573.2520909  656917.4786342 1025580.8919403  657013.7409127
 1025574.7800487  657068.7479376
#Sta/Elev= 30
       0 2060.35   22.15 2046.06   42.85 2031.61   64.01 2032.51   76.98 2032.58
   85.91 2032.29  109.16 2031.01  113.59 2030.53   123.5 2028.95  127.38 2026.15
  140.12 2018.19  148.85 2010.62  154.93 2009.62  184.98 2009.97   197.9 2010.69
  215.81 2013.43  226.91 2015.47  244.55 2022.11  247.67 2023.61  256.78 2025.95
  282.04 2027.54  283.29 2027.37  285.09 2027.49  292.25 2028.37   298.8  2032.8
  303.06 2034.74  314.12 2036.74  328.64 2040.43   335.3 2042.61  340.43 2044.81
#Mann= 3 , 0 , 0
       0    .065       0  148.85     .05       0   197.9     .07       0
Bank Sta=148.85,197.9
Exp/Cntr=0.3,0.1

Type RM Length L Ch R = 1 ,370544.0,441.22,473.63,487.56
XS GIS Cut Line= 5
 1025198.8987722  656561.4609905 1025020.1259564  656778.4331141
 1025009.4301611  657168.0661619 1025043.0455652  657242.9368195
 1025049.1574569  657293.3599106
#Sta/Elev= 30
       0 2038.067.800049 2035.0526.21002 2029.9757.62006 2022.4189.73004 2026.06
  100.55 2024.84  110.01 2021.16120.4301  2019.5  156.97 2017.87  281.02 2016.02
  354.49 2016.02  397.18 2016.73  452.28 2015.81  472.66 2014.45  495.65 2011.05
  508.34    2010     541 2009.05  553.26 2008.46565.9901 2004.87589.1801 2004.28
  602.59 2004.29  607.57 2007.12  619.53 2013.36  629.97  2015.4  651.92 2015.29
  663.48    2018  676.87 2019.87  712.25 2022.89751.2401 2028.13  803.78 2064.26
#Mann= 5 ,-1 , 0
       0     .05       0     541     .08       0  553.26     .05       0
  607.57     .08       0  619.53     .05       0
Bank Sta=553.26,607.57
Exp/Cntr=0.3,0.1

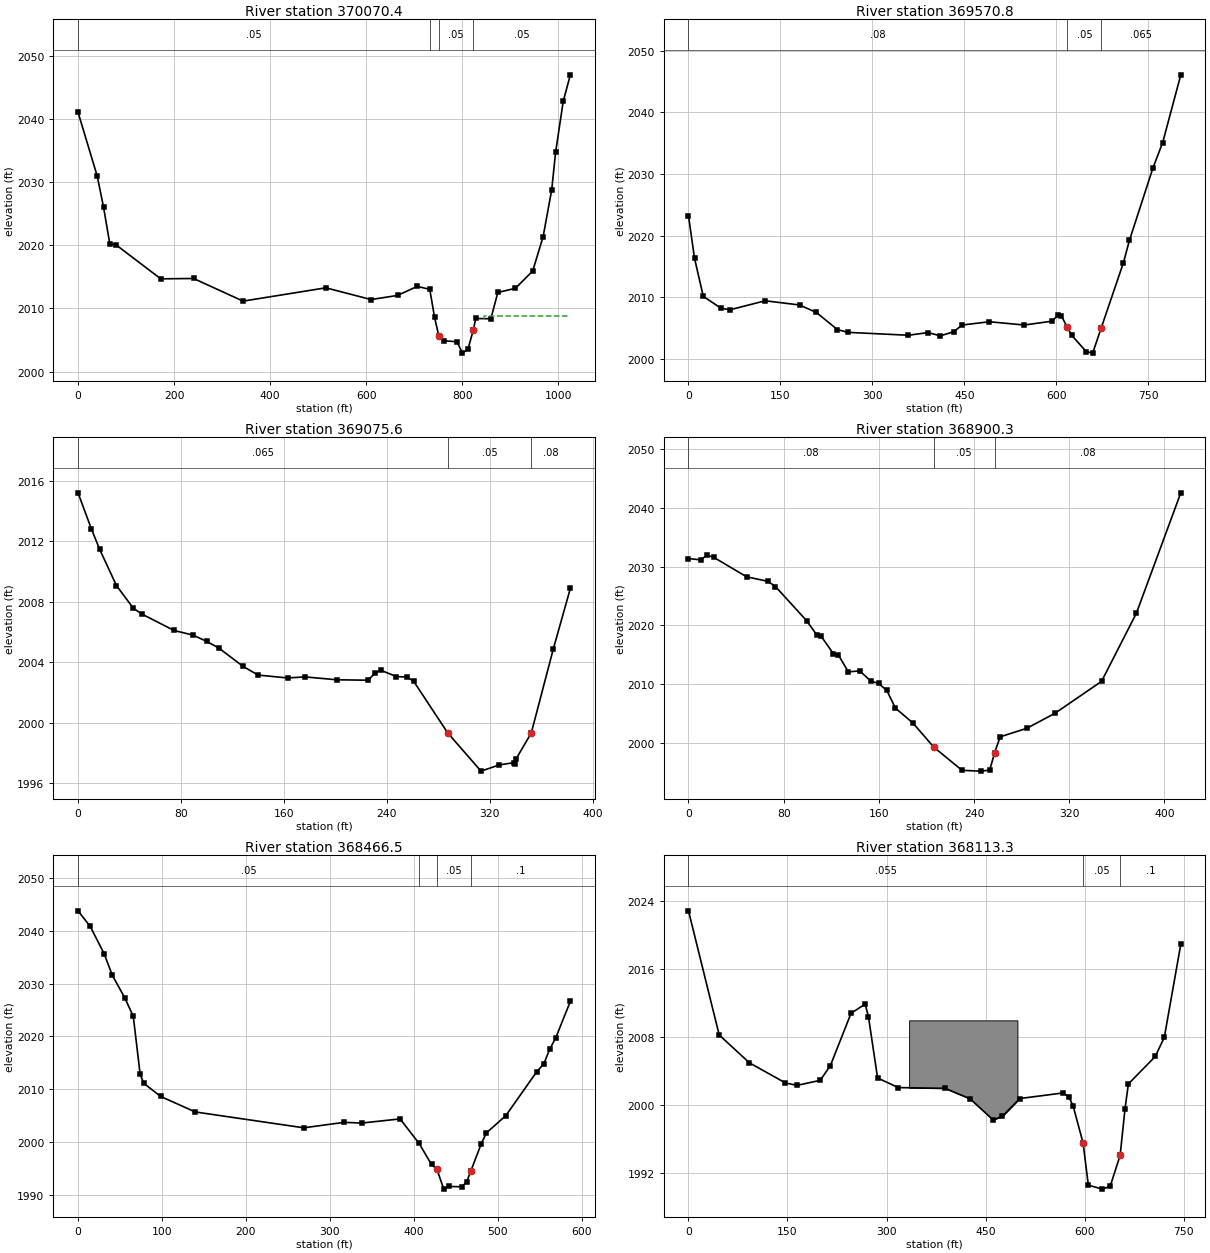
Type RM Length L Ch R = 1 ,370070.4,456.46,499.62,611.98
XS GIS Cut Line= 6
 1024900.9440993   656414.775621 1024841.3531405  656559.9330025
 1024696.1957591  656677.5869017 1024545.2236267  657057.7472227
 1024534.0448453   657165.808988 1024536.0632351  657329.6094763
#Sta/Elev= 30
       0 2041.09      40 2030.9653.10999 2026.0766.22998 2020.2278.72998  2020.1
  172.37 2014.69  240.57 2014.75  343.81 2011.16  516.28 2013.27  610.23 2011.41
  665.48 2012.06  706.64  2013.5  732.67 2013.02742.5699 2008.64  751.34 2005.68
  762.92 2004.88  789.38 2004.72  800.78 2002.92   812.2 2003.53  823.44 2006.61
  828.39 2008.41  859.87 2008.36  874.41 2012.53  911.02 2013.19  946.97 2015.92
  968.72 2021.35  986.75 2028.83  994.76 2034.74 1010.65 2042.82 1025.48 2047.02
#Mann= 4 ,-1 , 0
       0     .05       0  732.67     .08       0  751.34     .05       0
  823.44     .05       0
#XS Ineff= 2 , 0
       0                  846.03       0 2008.79
Permanent Ineff=
       F       F
Bank Sta=751.34,823.44
Exp/Cntr=0.3,0.1

Type RM Length L Ch R = 1 ,369570.8,122.89,495.14,576.87
XS GIS Cut Line= 6
 1024497.2479438   656543.988074  1024472.406167  656666.6443922
 1024289.1980028  656722.5384202 1024099.7794246  656956.9827339
 1024011.2805495  657017.5345799 1023933.6499971  657023.7450241
#Sta/Elev= 30
       0 2023.249.820007 2016.3524.14001 2010.17   53.06 2008.24   67.56 2007.99
  125.14 2009.45  181.21 2008.77  208.69 2007.55  242.95 2004.78  259.85 2004.33
  358.86 2003.86  390.69 2004.29  410.99 2003.77   432.6 2004.42   446.5 2005.52
  490.87 2006.05  547.71 2005.52  592.35 2006.13  603.22  2007.1  608.12 2007.04
  618.09 2005.15  625.09 2003.87  648.79 2001.22  659.41 2000.96  673.56  2005.1
  709.58 2015.63  719.46 2019.27  757.66 2030.97  773.62 2035.11   803.2  2046.1
#Mann= 3 , 0 , 0
       0     .08       0  618.09     .05       0  673.56    .065       0
#XS Ineff= 2 , 0
   803.2  199.98  2007.1           803.2
Permanent Ineff=
       F       F
Bank Sta=618.09,673.56
Exp/Cntr=0.3,0.1

Type RM Length L Ch R = 1 ,369075.6,69.55,175.31,151.75
XS GIS Cut Line= 5
 1024442.7716678   656536.719764 1024418.7297224   656579.995284
 1024316.5514163  656629.2812676 1024257.6486303    656682.17359
 1024165.0870964  656576.3889755
#Sta/Elev= 30
       0 2015.19   10.31 2012.82   16.77 2011.46   29.86 2009.06      43 2007.56
   49.51 2007.18   74.64 2006.09   89.47 2005.78   99.92 2005.37  109.42 2004.93
  128.35 2003.71  139.99 2003.14  162.95 2002.95  176.32 2003.02  201.13 2002.83
  225.59  2002.8  231.03  2003.3  235.62 2003.45  247.53 2003.04  255.71 2003.01
  260.82 2002.74  287.33 1999.32  313.25 1996.79  327.42  1997.2  338.75 1997.35
  339.59 1997.28  340.37 1997.58  352.31 1999.31  369.45 2004.87  382.68 2008.87
#Mann= 3 , 0 , 0
       0    .065       0  287.33     .05       0  352.31     .08       0
Bank Sta=287.33,352.31
Exp/Cntr=0.3,0.1

Type RM Length L Ch R = 1 ,368900.3,423.87,433.79,462.21
XS GIS Cut Line= 4
 1024536.0632351    656478.77841 1024391.6703622  656530.0145897
 1024272.1192964  656460.1470774 1024151.0156043  656444.6209669
#Sta/Elev= 30
       0 2031.36   10.57 2031.13   15.29 2031.95   21.09 2031.58   48.86 2028.26
   66.75 2027.49   73.07 2026.61   99.25 2020.81  107.89 2018.37  111.34 2018.21
  121.83 2015.19  125.77 2015.05  134.36 2012.12  143.96 2012.28  153.21 2010.55
  159.74 2010.16  166.66 2008.97  173.95 2005.95  188.55 2003.45  206.14 1999.34
  229.94 1995.39  245.91 1995.26  253.17 1995.43  257.31 1998.39  261.99 2001.09
  284.35 2002.53  307.98 2005.08  347.16  2010.5  376.46 2022.08  413.78 2042.52
#Mann= 3 , 0 , 0
       0     .08       0  206.14     .05       0  257.31     .08       0
Bank Sta=206.14,257.31
Exp/Cntr=0.3,0.1

Type RM Length L Ch R = 1 ,368466.5,357.6,353.23,339.84
XS GIS Cut Line= 4
 1024904.0321595  656373.2008284 1024792.2441337  656241.2288439
 1024596.6150811  656168.2561095  1024442.906542  656033.1789332
#Sta/Elev= 30
       0 2043.8114.52002 2040.8531.08002 2035.6940.91998 2031.5655.48999 2027.38
65.82001  2023.873.97003 2012.83   78.28 2011.13   98.37 2008.63  139.56 2005.69
  268.92 2002.68  316.93 2003.72  337.73 2003.58  383.56 2004.37   406.3 1999.71
  421.01 1995.73  427.48 1994.81   435.6 1991.06  442.03 1991.57  457.06  1991.5
  462.84 1992.42   467.7 1994.44  480.23 1999.64  486.42 2001.73  509.44 2004.97
   546.2 2013.27  554.86 2014.84   561.9 2017.61  568.79 2019.67  586.38 2026.64
#Mann= 4 ,-1 , 0
       0     .05       0   406.3     .08       0  427.48     .05       0
   467.7      .1       0
Bank Sta=427.48,467.7
Exp/Cntr=0.3,0.1

Type RM Length L Ch R = 1 ,368113.3,219.7,229.95,250.97
XS GIS Cut Line= 6
 1025259.6377954  656304.1490381 1024772.9092826  655854.0074578
 1024758.7255872  655848.3339978 1024724.6847363  655846.9156101
 1024710.5010409  655844.0788952 1024696.3173758  655831.3135572
#Sta/Elev= 30
       0 2022.86   46.54 2008.25   92.37 2004.97  146.88 2002.61  164.28 2002.32
  199.54 2002.91  214.95 2004.64   246.3 2010.81  267.71 2011.88   272.7 2010.38
  286.48 2003.19  317.93 2002.06  388.82 2001.97  426.69 2000.74   461.4 1998.26
  475.39 1998.67   501.8 2000.77  567.73 2001.43  576.62 2000.93  582.89 1999.85
  597.83 1995.54  605.76 1990.58  627.07 1990.11  638.85 1990.44  653.96 1994.08
  661.39 1999.59  666.46 2002.49  707.18 2005.72  720.91 2007.98  745.87 2018.93
#Mann= 3 , 0 , 0
       0    .055       0  597.83     .05       0  653.96      .1       0
#Block Obstruct= 1 ,-1
  334.27  498.34 2009.97
Bank Sta=597.83,653.96
Exp/Cntr=0.5,0.3

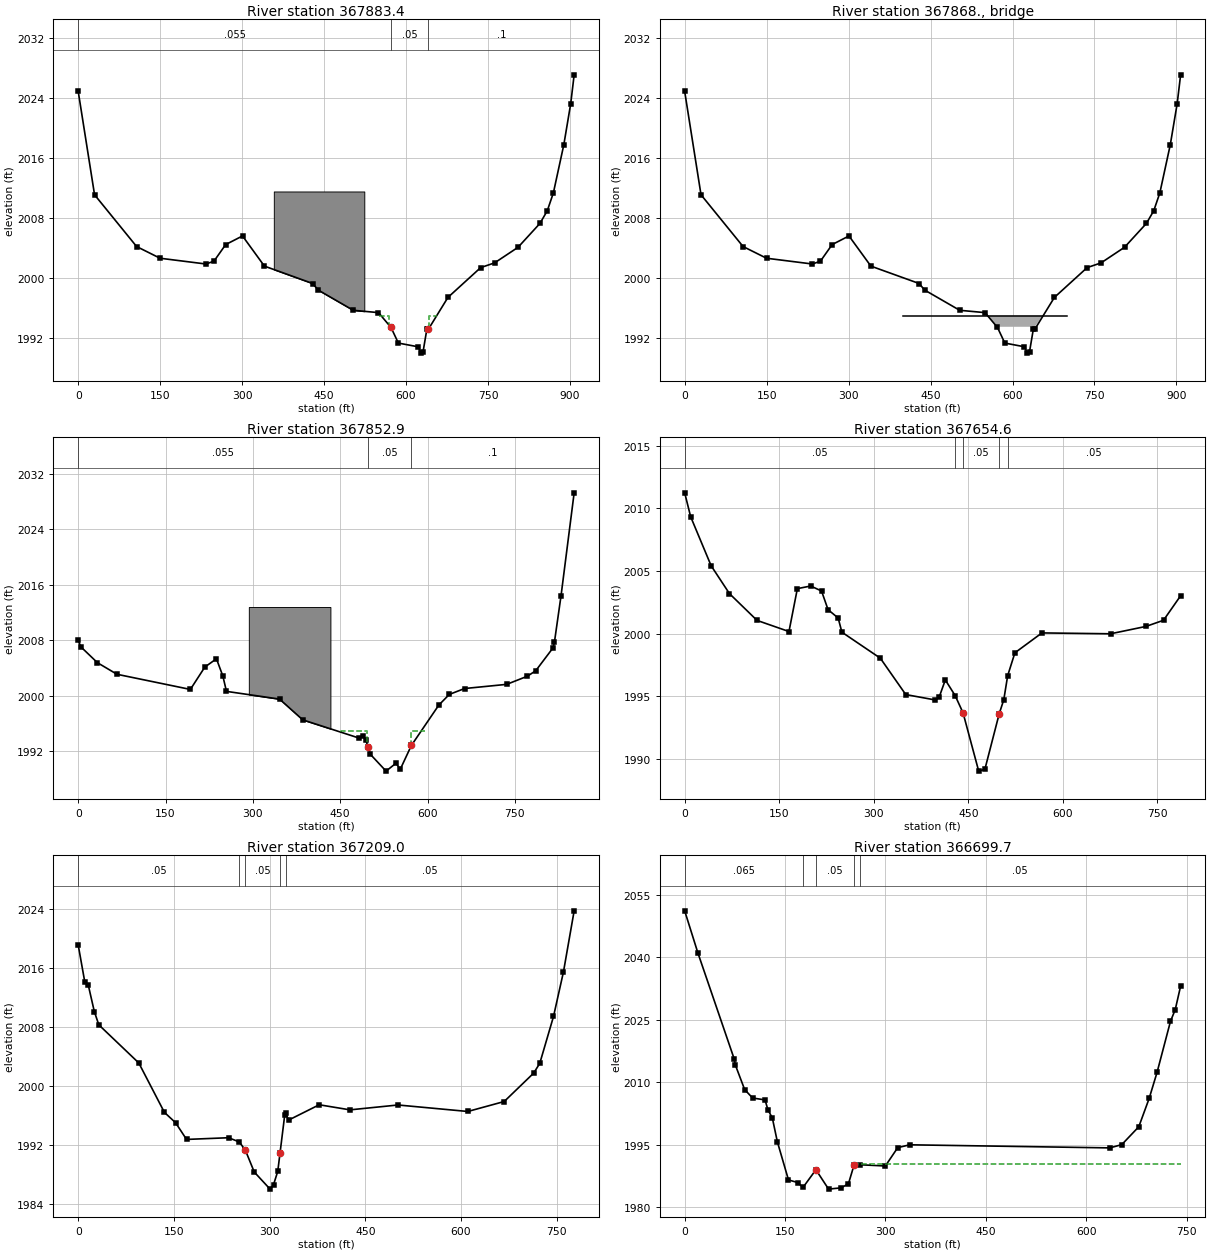
Type RM Length L Ch R = 1 ,367883.4,43.65,30.51,56.92
XS GIS Cut Line= 6
 1025406.1723699  656156.7616028   1025048.28471  655819.9825885
 1024950.4173207  655701.9660183 1024864.0637187  655621.3693554
 1024768.1152889  655579.1520342 1024745.0876839  655546.5295711
#Sta/Elev= 30
       0 2024.8829.90002  2011.1  106.86  2004.2   149.8 2002.64  233.78 2001.87
  248.47 2002.25  269.87 2004.46  300.68 2005.61  340.77 2001.59  429.11 1999.27
  439.13  1998.4  503.36  1995.7  549.55 1995.39  572.47 1993.41  585.92 1991.33
  621.65 1990.84  627.34 1989.99  631.18  1990.2  638.03 1993.16  640.97 1993.19
  676.67 1997.42  736.52 2001.39  762.01 2002.02  804.96  2004.1     845 2007.28
  858.45 2008.97   869.6 2011.35  888.77 2017.79  901.35 2023.26  907.63 2027.09
#Mann= 3 , 0 , 0
       0    .055       0  572.47     .05       0  640.97      .1       0
#XS Ineff= 2 ,-1
  549.89  568.37    1995   642.7  657.43    1995
Permanent Ineff=
       T       T
#Block Obstruct= 1 ,-1
  357.96  523.57 2011.54
Bank Sta=572.47,640.97
Exp/Cntr=0.5,0.3

Type RM Length L Ch R = 3 ,367868. ,,,
BEGIN DESCRIPTION:
Private_1
END DESCRIPTION:
Bridge Culvert--1,0,-1,-1, 0
Deck Dist Width WeirC Skew NumUp NumDn MinLoCord MaxHiCord MaxSubmerge Is_Ogee
7,16,2.6,0, 2, 2, 1994, , 0.95, 0, 0,0,,
     400     700
    1995    1995
  1993.5  1993.5
     400     700
    1995    1995
  1993.5  1993.5
BR Coef=-1 , 1 , 0 ,, 0 ,,,0.8,0,2,0,
WSPro=,,,, 1 ,,,, 0 ,,,, 0 ,,,,-1 ,-1 ,-1 , 0 , 0 , 0 , 0 , 0
BC Design=,, 0 ,, 0 ,,,,,,

Type RM Length L Ch R = 1 ,367852.9,197.68,198.25,169.86
XS GIS Cut Line= 6
 1025382.8568862  656088.1584748 1024974.1165721  655687.0940291
 1024958.7648355  655635.2818497 1024882.9655562  655553.7256919
 1024811.0042566  655542.2118743 1024790.8550757  655506.7109568
#Sta/Elev= 30
       0 2007.994.409973 2007.0632.98999 2004.7766.59998  2003.1  192.62 2000.92
  217.47 2004.14   237.4 2005.33  248.43 2002.84   254.6 2000.64  345.74 1999.53
  385.61 1996.54  482.65 1993.91  488.39 1994.22  494.17 1993.66  497.48 1992.63
  501.75 1991.58  528.72 1989.16  545.75  1990.3553.0599 1989.42   572.2 1992.86
  619.43 1998.68   637.3  2000.2  663.49 2001.05   735.9 2001.65  771.29 2002.82
  785.65  2003.6  815.41  2006.9  817.79 2007.69  829.24 2014.43  851.72 2029.22
#Mann= 3 , 0 , 0
       0    .055       0  497.48     .05       0   572.2      .1       0
#XS Ineff= 2 ,-1
  451.22  496.67    1995  572.06  595.34    1995
Permanent Ineff=
       T       T
#Block Obstruct= 1 ,-1
  292.99  433.12 2012.78
Bank Sta=497.48,572.2
Exp/Cntr=0.5,0.3

Type RM Length L Ch R = 1 ,367654.6,428.3,445.59,420.41
XS GIS Cut Line= 6
 1025538.2933636   655886.666757  1025388.613795  655809.9080132
  1025279.232588  655713.9595834 1025103.3891373  655530.6194205
 1024989.9196649  655442.6805634 1024923.2563509  655407.2213552
#Sta/Elev= 30
       0 2011.25    9.48 2009.34   41.98 2005.42   71.09 2003.19  114.84 2001.05
   165.5 2000.16  178.81 2003.59  200.01  2003.8  217.19  2003.4  227.52 2001.91
  243.57 2001.24  249.46 2000.11  310.44 1998.03  350.84 1995.12  397.63 1994.69
  403.67 1994.89  413.61 1996.29  429.19 1995.04  441.74 1993.66  466.59    1989
   476.4 1989.15  499.04 1993.57  506.44 1994.72  512.55 1996.63  524.01 1998.46
  566.91 2000.05  675.77 1999.98  732.06 2000.57  759.85 2001.06     787 2003.02
#Mann= 5 ,-1 , 0
       0     .05       0  429.19     .08       0  441.74     .05       0
  499.04     .08       0  512.55     .05       0
Bank Sta=441.74,499.04
Exp/Cntr=0.3,0.1

Type RM Length L Ch R = 1 ,367209.0,588.58,509.29,399.04
XS GIS Cut Line= 4
  1025713.299935  655542.5173387 1025558.6955243  655416.0228291
  1025500.133253  655305.9257542 1025118.3071944  655062.3067019
#Sta/Elev= 30
       0 2019.1210.35004 2014.0915.65002 2013.74   25.25  2010.132.29004  2008.3
94.95001 2003.13  135.11 1996.43  152.57 1995.03  169.81 1992.76  235.58 1992.99
  252.54 1992.42  262.12 1991.28  275.94 1988.34  300.75 1986.02  306.22 1986.64
  312.77 1988.43   316.4 1990.95  323.69 1996.06  325.03 1996.29  329.97 1995.39
  377.78 1997.46  426.01 1996.77  501.26 1997.43   610.7 1996.55  667.73  1997.9
   713.9 2001.75  723.47 2003.07  745.01 2009.43  760.63 2015.48  777.39 2023.76
#Mann= 5 ,-1 , 0
       0     .05       0  252.54     .08       0  262.12     .05       0
   316.4     .08       0  325.03     .05       0
Bank Sta=262.12,316.4
Exp/Cntr=0.3,0.1

Type RM Length L Ch R = 1 ,366699.7,561.8,544.41,532.69
XS GIS Cut Line= 5
 1026067.0160622  655038.8817692 1025992.0563562  655001.4019313
 1025938.1790532  654985.0044965 1025427.5160159  654903.0172925
 1025352.5563099  654865.5374546
#Sta/Elev= 30
       0 2051.1419.66998 2041.0873.84998 2015.6975.65002  2014.289.65002 2008.26
  101.58 2006.25  120.04  2005.8  124.49  2003.4     131 2001.46  138.48 1995.77
  155.13  1986.6  169.11 1985.98  176.79  1984.8  196.12 1989.05  215.05  1984.4
   233.8 1984.71  244.71 1985.68  253.24 1990.24  261.45 1990.25   299.9 1989.95
  318.38 1994.35  336.27 1995.03  635.27 1994.29  653.17 1995.07  678.62 1999.36
  694.09 2006.14  705.94 2012.41  725.97 2024.64  733.08 2027.44  741.13  2033.1
#Mann= 5 ,-1 , 0
       0    .065       0  176.79     .08       0  196.12     .05       0
  253.24     .08       0  261.45     .05       0
#XS Ineff= 2 , 0
       0  196.12 1989.05  253.55       0 1990.34
Permanent Ineff=
       F       F
Bank Sta=196.12,253.24
Exp/Cntr=0.3,0.1