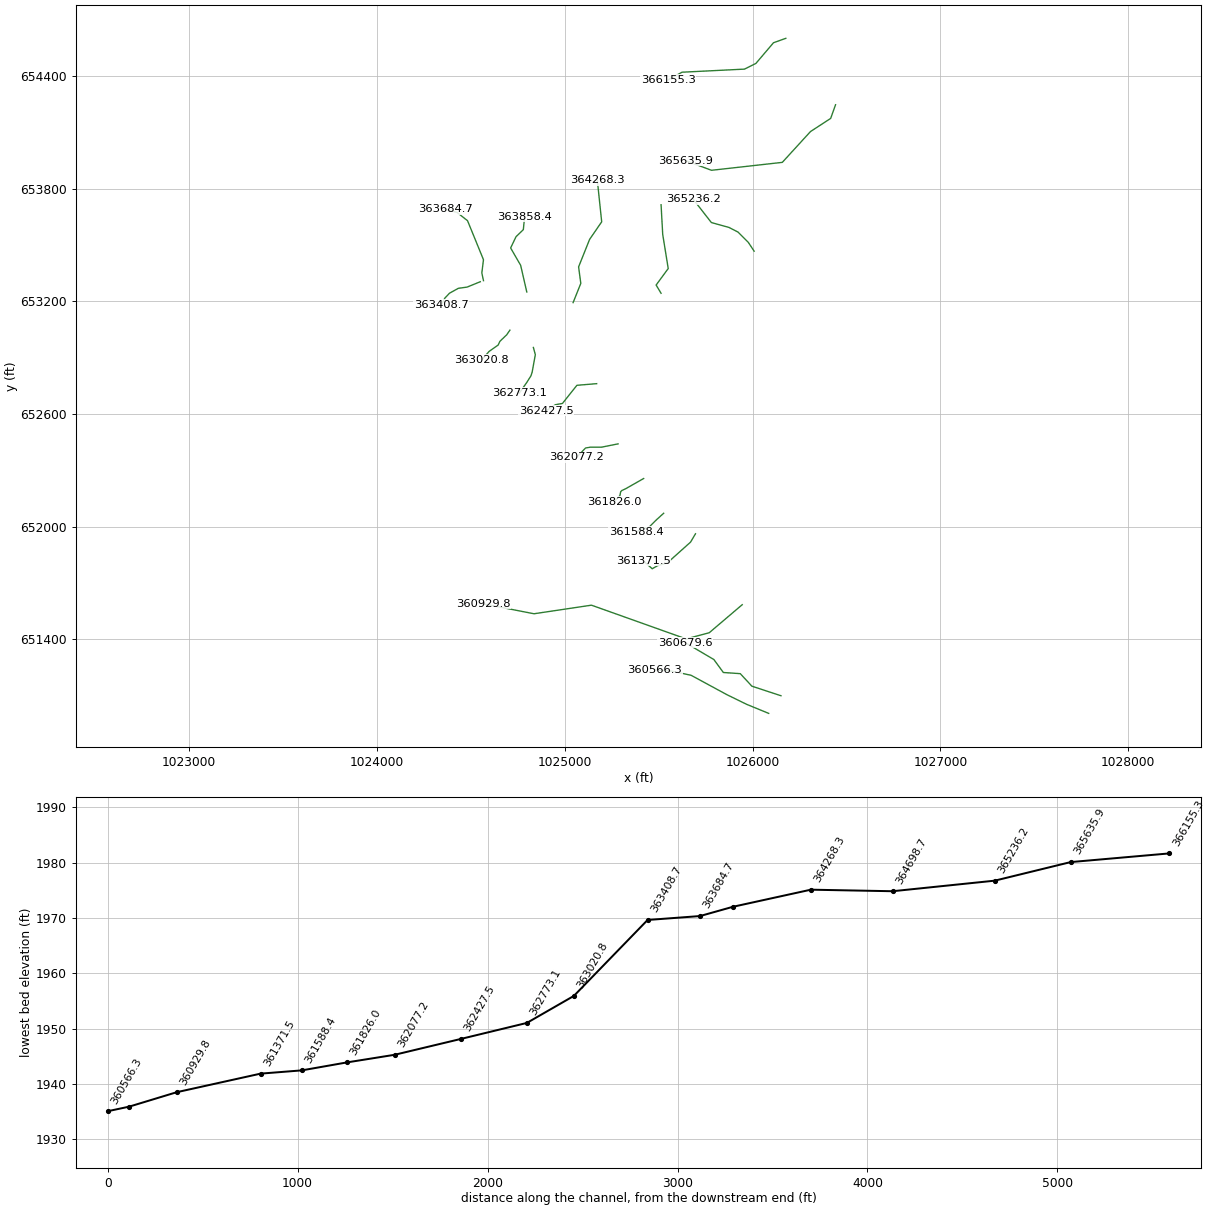
HEC-RAS study lds_broad_rvr.prj: Upper_Broad 3-06-07

--- lds_broad_rvr.g05 (geometry) --- (continued)

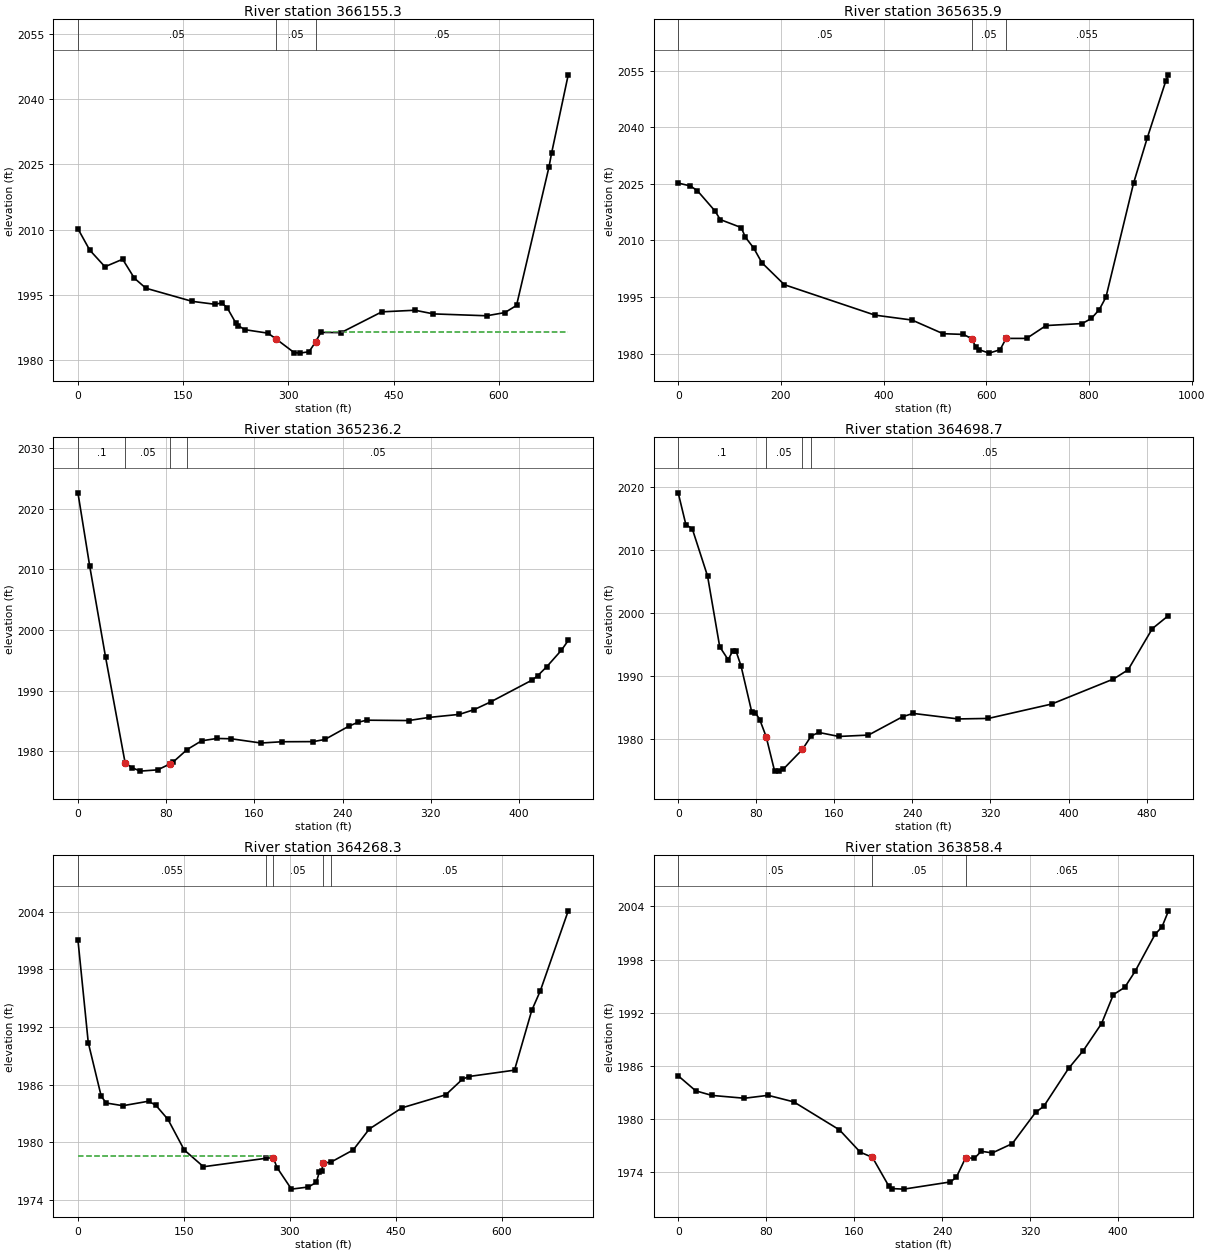
Type RM Length L Ch R = 1 ,366155.3,571.38,519.44,541.6
XS GIS Cut Line= 6
 1026177.1131371  654600.8359689 1026111.5233981  654577.4110664
  1026017.823758  654467.3139915 1025956.9189873  654436.8615911
 1025624.2852633  654420.4641563 1025551.6680565  654380.6418191
#Sta/Elev= 30
       0 2010.2116.80005 2005.3238.48004  2001.563.72003 2003.2280.42004 1998.87
96.85004 1996.57  162.75 1993.56  195.54 1992.88  204.88 1993.21  212.62 1992.09
   224.9 1988.61  228.77 1987.97  237.36 1987.07  270.79 1986.26  282.73 1984.88
  308.06  1981.8  316.16 1981.68  329.25    1982  338.62 1984.24  346.12 1986.44
  374.96 1986.39     433 1991.15  480.26 1991.52  506.54 1990.68  582.32 1990.25
608.3101 1990.98  624.91 1992.62  671.08 2024.32  674.83 2027.53  698.59 2045.53
#Mann= 3 , 0 , 0
       0     .05       0  282.73     .05       0  338.62     .05       0
#XS Ineff= 2 , 0
       0                  351.77       0 1986.45
Permanent Ineff=
       F       F
Bank Sta=282.73,338.62
Exp/Cntr=0.3,0.1

Type RM Length L Ch R = 1 ,365635.9,769.5,399.69,269.19
XS GIS Cut Line= 6
 1026441.8146228  654247.1198114  1026416.047221  654174.5026047
 1026308.2926454   654104.227867  1026158.373203  653940.2534892
 1025781.2321734  653898.0886527 1025643.0251974  653949.6234563
#Sta/Elev= 30
       0 2025.1923.83997 2024.4237.58002 2023.1371.53998 2017.8181.98999 2015.51
  122.75 2013.39  130.86 2010.83  146.95 2007.99  163.02 2004.07  206.71 1998.25
  383.28 1990.18  455.37 1988.88  515.79 1985.26  555.62 1985.07  571.94 1983.92
  579.39 1981.77  585.23 1981.06  605.46 1980.11  626.86 1981.01  638.67 1984.01
  678.53 1984.01  716.45 1987.42  786.76 1987.95  804.62 1989.29  820.02 1991.63
  833.08 1994.95  886.75 2025.12  913.46 2037.13  949.72  2052.3  954.87 2053.88
#Mann= 3 , 0 , 0
       0     .05       0  571.94     .05       0  638.67    .055       0
Bank Sta=571.94,638.67
Exp/Cntr=0.3,0.1

Type RM Length L Ch R = 1 ,365236.2,642.11,537.54,234.33
XS GIS Cut Line= 6
 1026008.4299397  653467.4558736 1025977.1799478  653514.3308615
 1025922.4924317  653569.0183776 1025874.3153456  653593.7579697
 1025780.5653396  653619.7996297 1025684.2111978  653743.4975295
#Sta/Elev= 30
       0 2022.59   10.73 2010.46      25 1995.59   42.79 1978.11    48.8 1977.34
   56.41 1976.75    72.3 1976.96   83.18 1977.91    86.4 1978.26   98.98  1980.3
   112.1 1981.74  125.94 1982.13  139.07 1982.08  165.93 1981.38  185.14 1981.59
  213.26 1981.61  223.87 1981.96  245.41 1984.13  253.57 1984.77  261.72 1985.14
   299.9 1985.08  318.07 1985.59  345.92  1986.1   359.3 1986.88  374.12 1988.14
  412.05 1991.77  416.93 1992.47  425.17 1993.96  438.42 1996.67  444.59 1998.27
#Mann= 4 ,-1 , 0
       0      .1       0   42.79     .05       0   83.18     .08       0
   98.98     .05       0
Bank Sta=42.79,83.18
Exp/Cntr=0.3,0.1

Type RM Length L Ch R = 1 ,364698.7,417.19,430.31,339.54
XS GIS Cut Line= 5
 1025512.7241263  653243.0696089 1025486.3710997  653286.9913199
 1025550.7896193   653374.834742 1025521.5084685  653556.3778043
 1025512.7241263  653714.4959338
#Sta/Elev= 30
       0 2019.15    7.93 2014.05   14.34 2013.47    30.1 2005.89   42.55 1994.64
   51.22 1992.58   56.01 1994.01   59.39 1993.89   64.41 1991.58   75.36 1984.26
   78.96 1984.17   83.53 1983.06   90.08 1980.35   98.72  1974.9  103.26 1974.84
  107.73 1975.16  127.31 1978.29  136.31 1980.44     144    1981   164.6 1980.36
  194.96 1980.58  230.07 1983.51  240.68 1984.03  286.87 1983.15  317.83 1983.23
  382.65 1985.52  445.96  1989.5  461.01 1990.97  485.85 1997.53   502.4 1999.61
#Mann= 4 ,-1 , 0
       0      .1       0   90.08     .05       0  127.31     .08       0
  136.31     .05       0
#XS Ineff= 2 , 0
       0                     144       0    1981
Permanent Ineff=
       F       F
Bank Sta=90.08,127.31
Exp/Cntr=0.3,0.1

Type RM Length L Ch R = 1 ,364268.3,320.84,409.94,538.59
XS GIS Cut Line= 6
 1025044.2259256  653193.2916798 1025085.2195125  653295.7756621
 1025073.5070764  653383.6190842 1025132.0693477  653530.0247776
  1025196.487837  653623.7244178 1025173.0629346  653846.2610367
#Sta/Elev= 30
       0 2001.06   14.62 1990.37   32.98 1984.78   40.16 1984.08    63.6  1983.8
  100.08 1984.27  110.38 1983.84  127.53 1982.37  150.44  1979.2  177.73 1977.45
  266.22 1978.33   276.5  1978.4  281.91 1977.36  302.29 1975.12  326.15 1975.34
  337.42 1975.82  341.93 1976.94  344.95 1976.99  347.28 1977.84  357.99 1977.92
  389.77  1979.2  412.55 1981.38  458.79 1983.58  520.86 1984.94  544.41 1986.56
  553.67 1986.84  618.09  1987.5  642.53 1993.72  654.67 1995.76  694.16 2004.08
#Mann= 5 ,-1 , 0
       0    .055       0  266.22     .08       0   276.5     .05       0
  347.28     .08       0  357.99     .05       0
#XS Ineff= 2 , 0
       0   274.4 1978.53               0
Permanent Ineff=
       F       F
Bank Sta=276.5,347.28
Exp/Cntr=0.3,0.1

Type RM Length L Ch R = 1 ,363858.4,211.09,173.65,317.82
XS GIS Cut Line= 6
 1024797.4924497  653250.0079677 1024764.9403597  653391.9350295
 1024711.5549417  653484.3829677 1024740.2007676  653544.2787856
 1024779.2632575  653582.0392076 1024785.7736876  653649.7475537
#Sta/Elev= 30
       0 1984.85   15.92 1983.15   30.65 1982.63   60.28 1982.31   81.76 1982.64
  105.09  1981.9  146.68 1978.73  165.56 1976.21  176.64 1975.62  191.26 1972.43
  194.51 1972.09  205.19 1972.03  247.38 1972.84  252.83 1973.35  261.43 1975.59
  269.25  1975.5   275.5 1976.31  285.71 1976.13  303.84 1977.18  324.93  1980.7
  332.51 1981.41  354.95 1985.68  368.33 1987.69  384.99 1990.76  395.72 1994.03
  406.13 1994.86  415.55 1996.68  433.65 2000.85  439.97  2001.7  445.85 2003.51
#Mann= 3 , 0 , 0
       0     .05       0  176.64     .05       0  261.43    .065       0
Bank Sta=176.64,261.43
Exp/Cntr=0.3,0.1

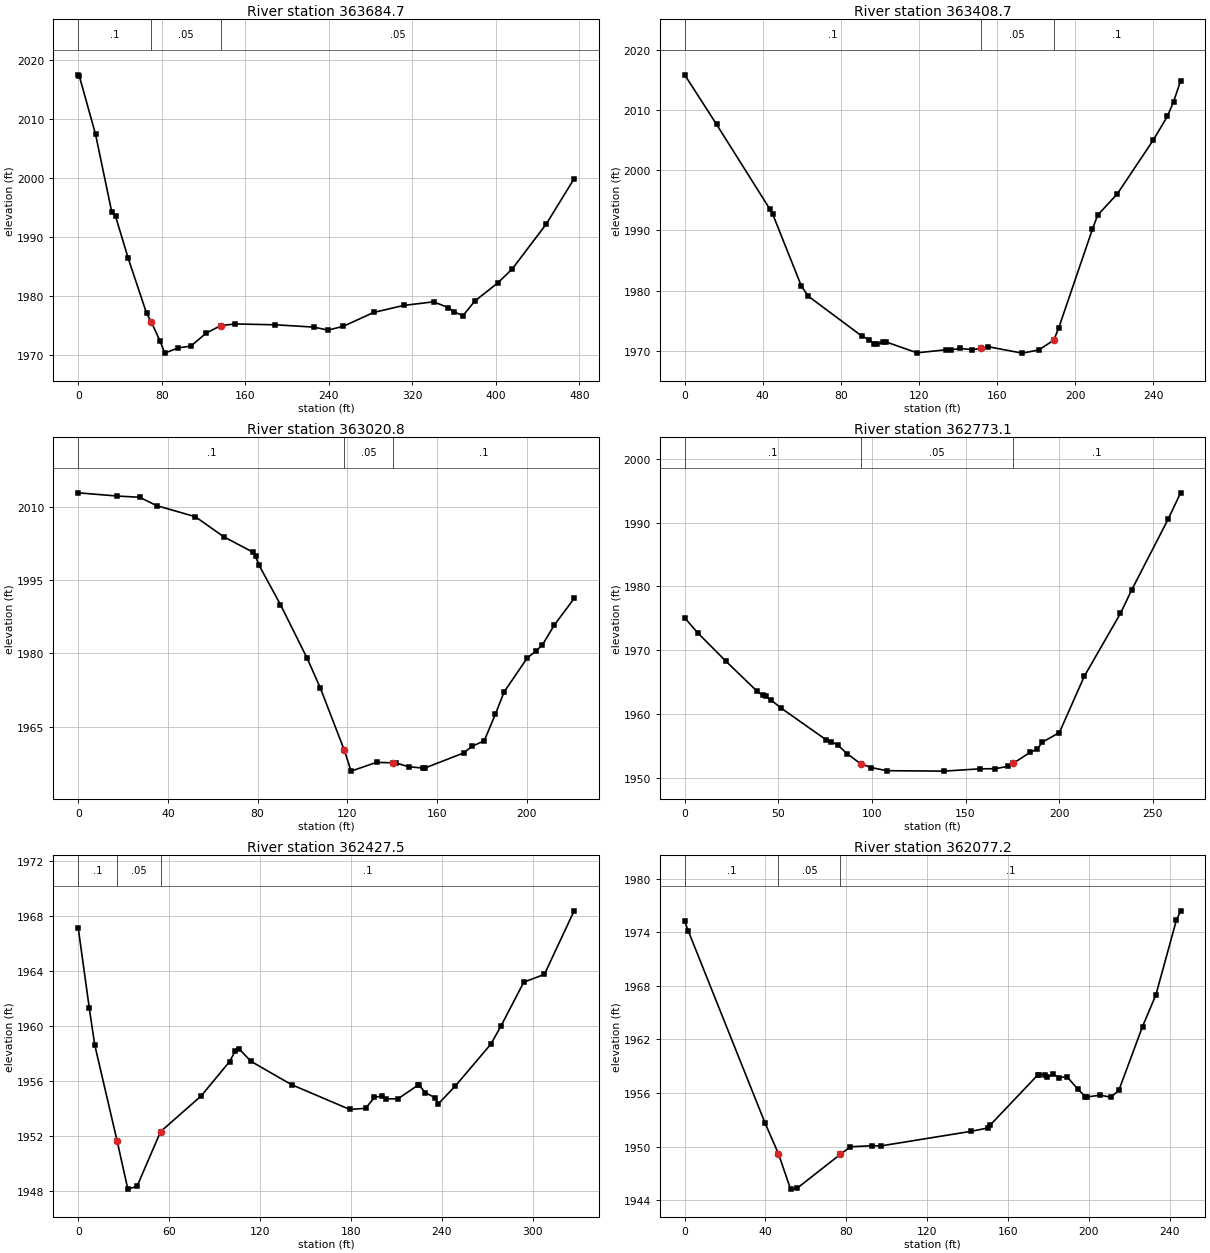
Type RM Length L Ch R = 1 ,363684.7,128.83,276.08,539.82
XS GIS Cut Line= 6
 1024566.9433826  653310.4162224 1024558.1590404  653351.4098396
 1024566.9433826   653421.684547 1024482.0280847  653629.5806358
 1024426.3939375  653673.5023469 1024361.9754179  653691.0710313
#Sta/Elev= 30
       0 2017.49     .89 2017.37   16.56 2007.45   32.17 1994.22   35.79 1993.51
   47.94 1986.38    65.5 1977.08   69.97 1975.64   78.55 1972.32   82.93 1970.35
   95.56 1971.23  107.83 1971.54  122.42 1973.71  136.39 1975.01  150.43 1975.29
  188.77 1975.15   225.4 1974.76  239.25 1974.25  253.98  1974.9  282.96 1977.24
  311.72 1978.43  340.39 1979.04  354.37 1978.06  360.16  1977.3  368.59 1976.72
   379.9 1979.18  401.59 1982.21  415.51 1984.57   448.2  1992.2  474.97  1999.9
#Mann= 3 , 0 , 0
       0      .1       0   69.97     .05       0  136.39     .05       0
#XS Ineff= 2 , 0
       0                  340.39       0 1979.04
Permanent Ineff=
       F       F
Bank Sta=69.97,136.39
Exp/Cntr=0.3,0.1

Type RM Length L Ch R = 1 ,363408.7,385.45,387.88,396.77
XS GIS Cut Line= 6
 1024550.0965895  653304.6954536 1024479.7841076  653276.0496276
 1024432.9090895  653269.5391975 1024386.0341016  653243.4975376
 1024361.2945095  653217.4558776 1024343.0653475  653182.2996216
#Sta/Elev= 30
       0 2015.81   16.37 2007.57   43.61 1993.54   45.15 1992.65   59.74 1980.79
   63.26  1979.1   90.78 1972.46   94.44 1971.88   97.02 1971.23   98.72 1971.14
  101.54 1971.48  103.02 1971.51     119 1969.69  134.02  1970.2  136.35 1970.18
  141.07 1970.41  147.37 1970.21  151.68 1970.42  155.34 1970.71  172.88 1969.64
  181.26 1970.15  189.05 1971.78  191.55 1973.78  208.84 1990.18  211.51 1992.52
  221.64 1996.08  240.07 2005.01  247.23 2008.91  250.41 2011.34  254.03 2014.82
#Mann= 3 , 0 , 0
       0      .1       0  151.68     .05       0  189.05      .1       0
Bank Sta=151.68,189.05
Exp/Cntr=0.3,0.1

Type RM Length L Ch R = 1 ,363020.8,220.57,247.72,267.99
XS GIS Cut Line= 6
 1024707.6486775  653046.8829596 1024690.7216137  653022.1433675
 1024654.2632595  652986.9871114 1024645.1486937  652967.4558816
 1024596.9716076  652933.6016934 1024557.9090875  652889.3308715
#Sta/Elev= 30
       0 2012.83   17.51 2012.17   27.42 2011.92   34.96 2010.22   52.26 2007.94
    64.9 2003.86   77.89  2000.7   79.16 1999.82   80.63 1998.06   90.22 1989.97
  102.18 1978.96  108.05 1972.88  118.76 1960.14  121.73 1955.91  133.08  1957.7
  140.61 1957.61   141.7 1957.58  147.53  1956.8  153.76 1956.54  154.91 1956.59
  171.99 1959.63  175.63 1960.98  181.12  1962.1  186.08 1967.51  190.03 1972.12
  200.29 1979.02  204.36 1980.53   207.1 1981.72  212.32 1985.73  221.26 1991.23
#Mann= 3 , 0 , 0
       0      .1       0  118.76     .05       0  140.61      .1       0
Bank Sta=118.76,140.61
Exp/Cntr=0.3,0.1

Type RM Length L Ch R = 1 ,362773.1,389.51,345.59,236.88
XS GIS Cut Line= 6
 1024832.6486755  652954.4350517 1024843.0653395  652916.6746296
 1024826.1382757  652822.9246235 1024819.6278456  652803.3933635
 1024797.4924497  652768.2371377 1024758.4299296  652712.2475537
#Sta/Elev= 29
       0 1975.07    6.93 1972.73   22.01 1968.27    38.6 1963.58   41.68 1962.89
    43.2 1962.77   46.31 1962.13   51.66 1960.88   75.34 1955.98   78.42 1955.63
    81.7 1955.12   86.74 1953.77   93.93 1952.18   99.62 1951.58  107.85 1951.09
  138.39 1951.02  157.74 1951.38  165.88  1951.4  172.65 1951.77  175.38 1952.22
  184.43 1953.96  188.19 1954.43  191.07 1955.57  200.14 1957.07  213.45  1965.9
  232.78 1975.78  238.78 1979.46  258.21 1990.54   264.9 1994.69
#Mann= 3 , 0 , 0
       0      .1       0   93.93     .05       0  175.38      .1       0
Bank Sta=93.93,175.38
Exp/Cntr=0.3,0.1

Type RM Length L Ch R = 1 ,362427.5,362.33,350.26,303.3
XS GIS Cut Line= 5
   1025169.76881  652761.7609104 1025064.3567035  652752.9765681
 1024987.4937167  652656.3488341  1024950.160285   652649.760585
 1024899.6503249   652616.819279
#Sta/Elev= 30
       0 1967.137.329987 1961.27   10.91 1958.6225.63998 1951.6632.76999 1948.14
   38.87 1948.3554.38998 1952.3281.17999 1954.9199.96999 1957.41   103.8  1958.2
  106.48  1958.3  114.14 1957.42  140.85 1955.73  179.31 1953.93  189.71 1954.01
  195.62  1954.8  200.29 1954.91  203.38 1954.69  211.21 1954.71  224.44  1955.7
  225.08 1955.69  229.25 1955.15  235.79 1954.77   237.8 1954.34  248.98 1955.63
  272.44 1958.67     279 1959.96  294.22 1963.18   307.8 1963.74  327.46 1968.36
#Mann= 3 , 0 , 0
       0      .1       025.63998     .05       054.38998      .1       0
#XS Ineff= 2 , 0
       0                  106.48       0  1958.3
Permanent Ineff=
       F       F
Bank Sta=25.63998,54.38998
Exp/Cntr=0.3,0.1

Type RM Length L Ch R = 1 ,362077.2,248.92,251.19,313.58
XS GIS Cut Line= 5
 1025283.9652285  652441.1324651 1025196.1218366  652423.5637807
 1025136.8275343  652423.5637807 1025110.4745077  652419.1716247
 1025062.1606406  652368.6616646
#Sta/Elev= 30
       0 1975.211.710007 1974.18   39.77 1952.6646.40001 1949.23   52.41 1945.26
55.76001 1945.38   77.11 1949.1682.07001    195092.96001 1950.12      97 1950.09
  141.91 1951.73  150.37 1952.11  151.21 1952.42  174.74 1958.02  175.59 1958.08
  178.26 1958.05  179.52  1957.8  182.42  1958.1  185.52 1957.74  189.16 1957.85
  194.66 1956.43  198.39 1955.62  199.14 1955.57  205.61 1955.77  210.95 1955.54
  214.91 1956.31  226.63 1963.45  233.25 1966.99  243.38 1975.33  245.49 1976.39
#Mann= 3 , 0 , 0
       0      .1       046.40001     .05       0   77.11      .1       0
#XS Ineff= 2 , 0
       0                  182.42       0  1958.1
Permanent Ineff=
       F       F
Bank Sta=46.40001,77.11
Exp/Cntr=0.3,0.1

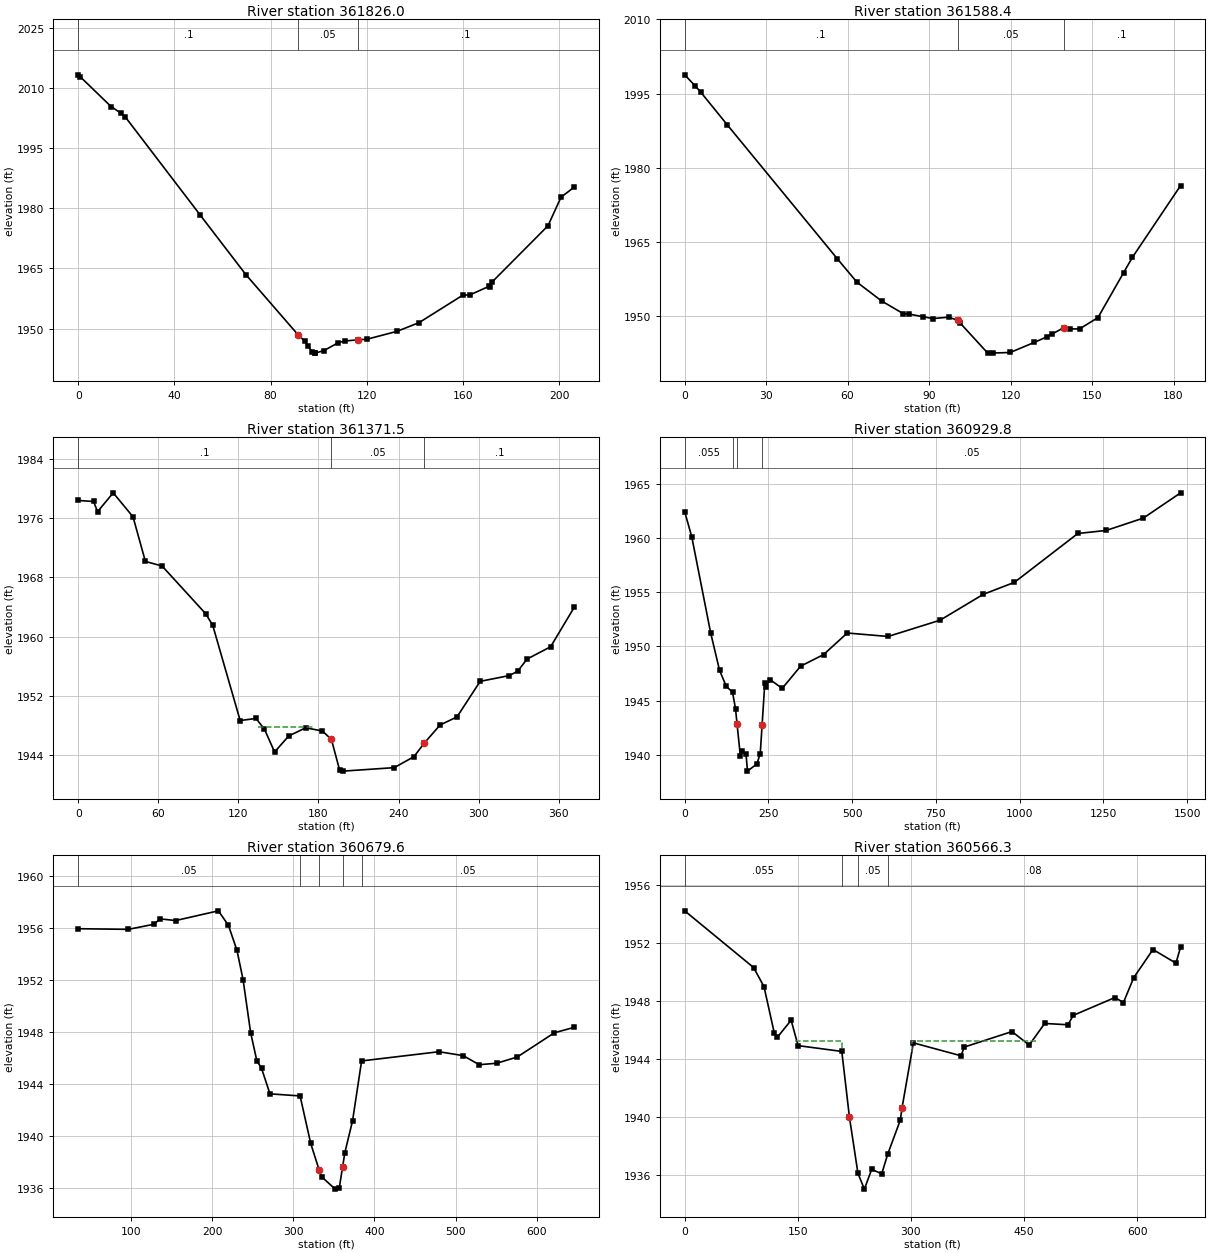
Type RM Length L Ch R = 1 ,361826.0,240.67,237.65,219.7
XS GIS Cut Line= 6
 1025419.8882737  652256.5183836 1025323.5341016  652201.8308674
 1025304.0028416  652192.7163016 1025297.4924417  652186.2058715
 1025293.5861776  652165.3725435 1025263.6382535  652134.1225516
#Sta/Elev= 28
       0 2013.29     .84 2012.81   13.64 2005.39   17.71 2003.75   19.65 2002.73
   50.77 1978.29   69.76 1963.44   91.58 1948.36    94.2 1946.88   95.65 1945.63
   97.41  1944.1   98.45 1943.88   98.53 1943.89  102.11 1944.49  108.23  1946.5
  110.81 1946.91  116.21 1947.18  120.29 1947.38  132.58 1949.31  141.78 1951.49
  159.87  1958.3  162.98 1958.43  170.81 1960.52  171.12 1960.34  172.16 1961.63
  195.38 1975.64   200.8 1982.75  206.27 1985.28
#Mann= 3 , 0 , 0
       0      .1       0   91.58     .05       0  116.21      .1       0
Bank Sta=91.58,116.21
Exp/Cntr=0.3,0.1

Type RM Length L Ch R = 1 ,361588.4,260.55,216.89,226.87
XS GIS Cut Line= 6
 1025526.6591097  652071.6225375 1025484.9924236  652033.8621154
 1025445.9299336  651994.7996255 1025429.0028395  651992.1954595
 1025415.9820096  651992.1954595 1025380.8257535  651971.3621315
#Sta/Elev= 27
       0 1998.79    3.86 1996.55    6.01 1995.22   15.66 1988.68   56.23 1961.53
   63.42 1956.81   72.49 1953.01   80.46 1950.44   82.58 1950.35   87.59 1949.83
   91.44 1949.44   97.19 1949.72   100.5  1949.1  101.43 1948.54   111.6 1942.44
  113.61 1942.46  119.87 1942.57  128.73 1944.61  133.25 1945.71   135.3 1946.32
  139.55 1947.57  141.75 1947.35  145.39 1947.34  152.18 1949.63  161.63 1958.74
  164.84 1961.81  182.62 1976.37
#Mann= 3 , 0 , 0
       0      .1       0   100.5     .05       0  139.55      .1       0
Bank Sta=100.5,139.55
Exp/Cntr=0.3,0.1

Type RM Length L Ch R = 1 ,361371.5,474.25,441.69,435.23
XS GIS Cut Line= 6
 1025695.9299296  651962.2475354 1025669.8882697  651917.9767135
 1025546.1903396  651807.2996134 1025495.4090875  651792.9767155
 1025465.4611937  651776.0496214 1025417.2841077  651819.0183755
#Sta/Elev= 30
       0 1978.39   11.53 1978.25   14.47 1976.87   26.21 1979.42   41.06 1976.18
   50.32 1970.16   62.83 1969.54   95.65 1963.07   100.8 1961.52  121.32 1948.68
  133.19 1948.96  139.51 1947.52  147.11 1944.43  157.74  1946.6  170.37  1947.7
  182.86 1947.27  189.67 1946.14  195.82    1942  198.45 1941.85  236.73 1942.32
  251.49  1943.8  259.39 1945.66   271.1 1948.08  283.77 1949.17  301.12 1953.97
  322.98 1954.75  329.22 1955.34  336.27 1956.98   353.9 1958.64  371.53 1963.95
#Mann= 3 , 0 , 0
       0      .1       0  189.67     .05       0  259.39      .1       0
#XS Ineff= 2 ,-1
     110  133.19 1948.96     135  174.81 1947.74
Permanent Ineff=
       F       F
Bank Sta=189.67,259.39
Exp/Cntr=0.3,0.1

Type RM Length L Ch R = 1 ,360929.8,445.21,250.16,91.7
XS GIS Cut Line= 6
 1025944.9869268  651584.6592056 1025769.3000826  651435.3253881
 1025646.3193219  651402.3841123 1025141.9874678  651582.0266785
 1024835.9638363  651536.3453083 1024565.8453512  651589.0513616
#Sta/Elev= 30
       0 1962.42   21.17  1960.1   77.38 1951.27  103.97  1947.8  123.84 1946.33
  142.89 1945.76  151.83 1944.23  156.39 1942.82  166.38 1939.85  172.34 1940.31
  183.22 1940.06  187.46 1938.49  215.46 1939.15  225.54  1940.1  231.17 1942.75
  239.17 1946.61   242.4 1946.28  255.08 1946.93  291.14 1946.12  346.06 1948.17
  414.69 1949.24  485.35 1951.23  607.05 1950.91  762.41 1952.41  891.58  1954.8
  984.26  1955.9 1173.76 1960.41 1258.36 1960.69 1369.27 1961.83 1480.54 1964.16
#Mann= 4 ,-1 , 0
       0    .055       0  142.89     .08       0  156.39     .05       0
  231.17     .05       0
#XS Ineff= 2 , 0
       0                  255.08       0 1946.93
Permanent Ineff=
       F       F
Bank Sta=156.39,231.17
Exp/Cntr=0.3,0.1

Type RM Length L Ch R = 1 ,360679.6,116.72,113.29,147.43
XS GIS Cut Line= 6
 1026151.3442065  651099.7138084 1025996.3890355   651150.589195
 1025934.6241398  651217.2953078 1025844.4473896  651223.4717914
 1025793.8001641  651292.6484674 1025640.6232215  651382.8252176
#Sta/Elev= 30
   34.81 1955.97   96.52 1955.92  127.91 1956.31   135.8 1956.73  154.88  1956.6
  207.63 1957.35  220.01 1956.23  230.57 1954.29  238.08 1952.03  247.36 1947.96
  255.03 1945.78  260.81  1945.2   271.2 1943.23  308.33 1943.07  321.42 1939.41
  331.86 1937.35  334.76 1936.84  351.62 1935.88  356.55 1935.93  360.72 1937.58
  363.54  1938.7  373.05 1941.16  384.19 1945.77  479.52 1946.48  509.36 1946.18
  529.17 1945.48  550.65 1945.59  575.99 1946.07   621.8 1947.94  646.22 1948.36
#Mann= 5 ,-1 , 0
   34.81     .05       0  308.33     .08       0  331.86     .05       0
  360.72     .08       0  384.19     .05       0
Bank Sta=331.86,360.72
Exp/Cntr=0.5,0.3

Type RM Length L Ch R = 1 ,360566.3,28.34,25.73,34.01
XS GIS Cut Line= 6
 1026085.7685272  651005.8024752 1025968.2434787  651054.1004213
 1025862.7929622  651105.6182445  1025672.740966  651208.6482006
 1025568.9759521  651230.8835716 1025478.7991716  651238.2953518
#Sta/Elev= 30
       0 1954.25   91.31 1950.34  105.16 1949.02  118.79 1945.82  122.84 1945.53
  141.12  1946.7  150.36 1944.95   208.3 1944.55  218.44 1940.01  229.71 1936.14
  238.24 1935.05  247.88 1936.41  261.27 1936.11  269.29 1937.48  285.86 1939.81
  288.17 1940.66  303.21 1945.14  366.36 1944.25  370.65 1944.85  433.92 1945.92
  456.78 1944.99   477.3 1946.48   508.1 1946.39  515.24 1947.04  570.55 1948.27
  581.68 1947.92  595.23 1949.63  620.84 1951.58  651.32 1950.64   657.5 1951.76
#Mann= 4 ,-1 , 0
       0    .055       0   208.3     .08       0  229.71     .05       0
  269.29     .08       0
#XS Ineff= 3 ,-1
                          146.67  207.98 1945.25  301.11  465.63 1945.25
Permanent Ineff=
       F       T       T
Bank Sta=218.44,288.17
Exp/Cntr=0.5,0.3

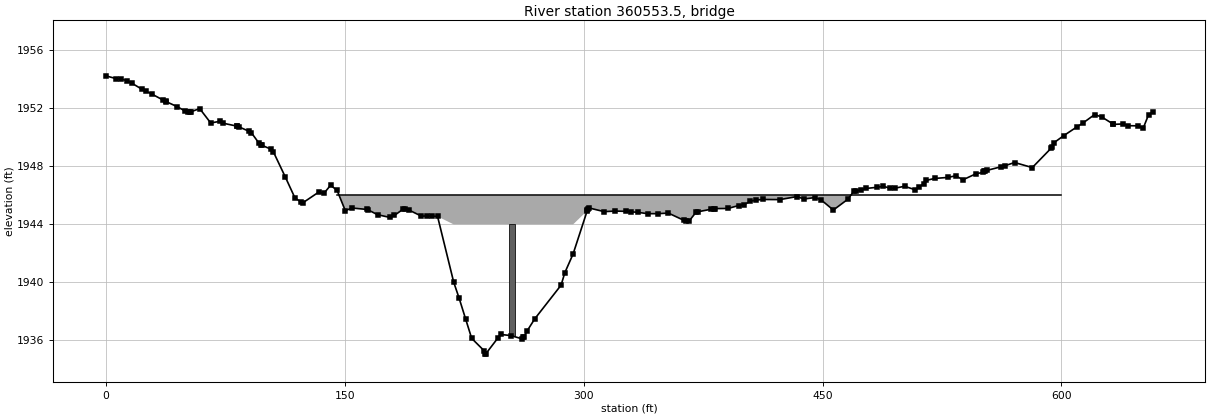
Type RM Length L Ch R = 3 ,360553.5,,,
BEGIN DESCRIPTION:
STR_142
END DESCRIPTION:
Bridge Culvert--1,0,-1,-1, 0
Deck Dist Width WeirC Skew NumUp NumDn MinLoCord MaxHiCord MaxSubmerge Is_Ogee
1,24,2.6,0, 2, 2, , , 0.95, 0, 0,0,,
  145.21     600
    1946    1946
    1944    1944
   82.19     600
    1946    1946
    1944    1944
Pier Skew, UpSta & Num, DnSta & Num=  ,255, 2 ,228, 2 , 0 , 0 , 0 ,,
       4       2
    1930    1945
       4       2
    1930    1945
BR Coef=-1 , 1 , 0 ,, 0 ,,,0.8,0,2,0,
WSPro=,,,, 1 ,,,, 0 ,,,, 0 ,,,,-1 ,-1 ,-1 , 0 , 0 , 0 , 0 , 0
BR U #Sta/Elev= 145
       0 1954.25     6.4 1954.06    9.69 1954.03   13.34 1953.91   16.41 1953.74
   22.46 1953.34   24.95 1953.21   28.79    1953   35.95 1952.58   37.82 1952.48
    38.1 1952.46   44.88 1952.12   49.64 1951.83   51.83 1951.72   52.58 1951.72
   53.19 1951.76   58.95 1951.99   65.86    1951   71.68 1951.11   73.29 1950.99
   82.34 1950.78   82.54 1950.79   83.36 1950.74   89.63 1950.44   91.31 1950.34
   96.14 1949.61   97.65 1949.46    98.2 1949.45  103.68 1949.19  105.16 1949.02
  112.63 1947.29  118.79 1945.82  122.84 1945.53  123.73 1945.49  133.58 1946.22
  136.96 1946.14  141.12  1946.7  145.21 1946.35  150.36 1944.95  154.66 1945.13
  164.07 1945.03  164.54 1945.01   170.6 1944.67   178.4 1944.48  181.26 1944.62
  186.37 1945.03  188.09 1945.05  190.15    1945  198.16 1944.57  201.42 1944.58
  205.09 1944.56   208.3 1944.55  218.44 1940.01  221.81 1938.92     2261937.446
  229.71 1936.14  237.75 1935.26  238.24 1935.05  238.44 1935.05  246.23 1936.17
  247.88 1936.41  254.24 1936.33  261.27 1936.11  262.12 1936.22  262.63 1936.22
  264.57 1936.66  269.29 1937.48  285.86 1939.81  288.17 1940.66  293.39 1941.96
  302.15 1944.93  302.39 1944.99  302.72 1945.08  303.21 1945.14  312.89 1944.88
  319.85 1944.92  326.65  1944.9  329.49 1944.87  334.16 1944.83   340.2 1944.74
  346.59 1944.74  353.22 1944.78  363.14 1944.27  364.46 1944.25  366.36 1944.25
  370.65 1944.85  371.75 1944.87  380.17 1945.05  381.95 1945.08  382.76 1945.09
  390.69  1945.1  397.26  1945.3   400.8 1945.36  404.62 1945.59  408.27 1945.68
  412.38 1945.72  423.19 1945.71  433.92 1945.92   438.3 1945.75  445.02 1945.85
  449.01  1945.7  456.78 1944.99  465.81 1945.73  469.69 1946.29  471.16 1946.33
  473.91 1946.36   477.3 1946.48  484.29 1946.56  488.13 1946.63  492.57 1946.49
  495.44  1946.5   501.5 1946.63   508.1 1946.39  510.76 1946.59  513.63 1946.82
  515.24 1947.04  520.35 1947.17  528.58 1947.24  533.55 1947.35  538.21 1947.08
  546.46  1947.5  550.99 1947.59  551.64 1947.68  552.03 1947.71  552.99 1947.72
  561.73 1947.97  564.39 1948.04  570.55 1948.27  581.68 1947.92  593.54 1949.26
  594.08 1949.35  595.23 1949.63  601.52 1950.13  609.88 1950.74  613.57    1951
  620.84 1951.58  625.45  1951.4  632.32 1950.93  632.48  1950.9  638.79 1950.93
  642.05 1950.81  647.99  1950.8  651.32 1950.64  654.67 1951.56   657.5 1951.76
BR U #Mann= 4
       0    .055  218.44     .04  288.17    .055  302.15     .08
BR D #Sta/Elev= 138
       0  1953.1    1.37 1953.04     3.8  1952.9    7.72 1952.53   10.39 1952.23
   13.24 1951.87   15.75 1951.48   22.82 1950.75   25.49 1950.36    31.4  1949.1
      40 1949.86   40.88  1949.8   41.49 1949.77   47.47 1947.76   50.18 1948.14
   53.62 1947.23   57.29 1947.24   61.24 1947.72   66.94 1947.12   71.01 1946.33
   82.19 1946.84   83.11 1946.82   83.31 1946.82   83.58 1946.87   89.05 1946.05
   89.84 1945.92   89.91 1945.91   91.33 1945.89   99.01 1945.73  105.94 1945.41
  107.81 1945.39  110.64  1945.4   115.8 1945.07  120.26 1944.93  124.67 1944.98
  127.61 1944.93  132.95 1944.81  137.41 1944.62  139.92 1944.62  145.02 1944.88
  150.15 1945.03  151.35 1944.97  157.27 1944.43   157.6 1944.42  158.89 1944.41
   165.1 1944.25   165.8 1944.23   167.2 1944.23  169.57 1944.24  176.58 1944.23
  182.51  1943.8  183.47 1943.74  194.11 1941.14   203.4 1936.06  206.19 1934.86
  213.77 1934.94  218.57 1935.17  220.63 1935.27  222.76 1934.98  225.24 1934.94
   228.5 1935.09  235.72  1935.3  239.19 1935.91  259.36 1939.48  262.36 1940.12
  266.22 1941.54  272.97 1944.01  273.13 1944.05  273.23 1944.06  273.87 1944.09
  283.18 1944.23  285.05 1944.57  290.66 1944.78  291.07 1944.81  291.49 1944.83
  300.61 1944.87  306.19 1944.79  313.76 1944.65  314.93 1944.65  320.29 1944.02
  320.82 1944.01  328.86 1944.69  335.49 1944.29     336 1944.31  340.47 1944.45
  345.47 1944.82  349.56 1944.91  352.22 1944.96  357.82 1945.11  365.76 1945.12
  367.91 1945.14  369.24 1945.16  372.38 1945.09  379.75 1944.99  381.58 1944.97
  386.85 1945.05  388.49 1945.05  396.76 1945.06  397.06 1945.06  403.99 1944.58
  405.89 1944.54  409.85 1944.75  412.61 1945.07  413.94 1945.11  418.17  1945.3
  420.95  1945.4  425.76 1945.51  430.29 1945.52   433.5 1945.52   434.5  1945.5
  436.57 1945.48     441 1945.57  444.54 1945.43  446.71 1945.42  450.84 1945.43
  453.34 1945.18  461.02 1946.06  462.36 1946.19  470.15 1945.57  470.71 1945.57
  482.21 1945.63  483.75 1945.62  495.62  1945.8  496.72 1945.85  500.69    1946
  501.09 1946.01   509.5 1946.13  513.06 1946.26  516.76 1946.38  520.49 1946.54
  533.43 1947.01  536.17 1947.08  541.37 1947.17  545.91 1947.42  549.69 1947.12
  550.98 1947.14  553.35 1947.38  555.74 1947.61
BR D #Mann= 3
       0    .055  194.11     .04  262.36    .055
BC Design=,, 0 ,, 0 ,,,,,,