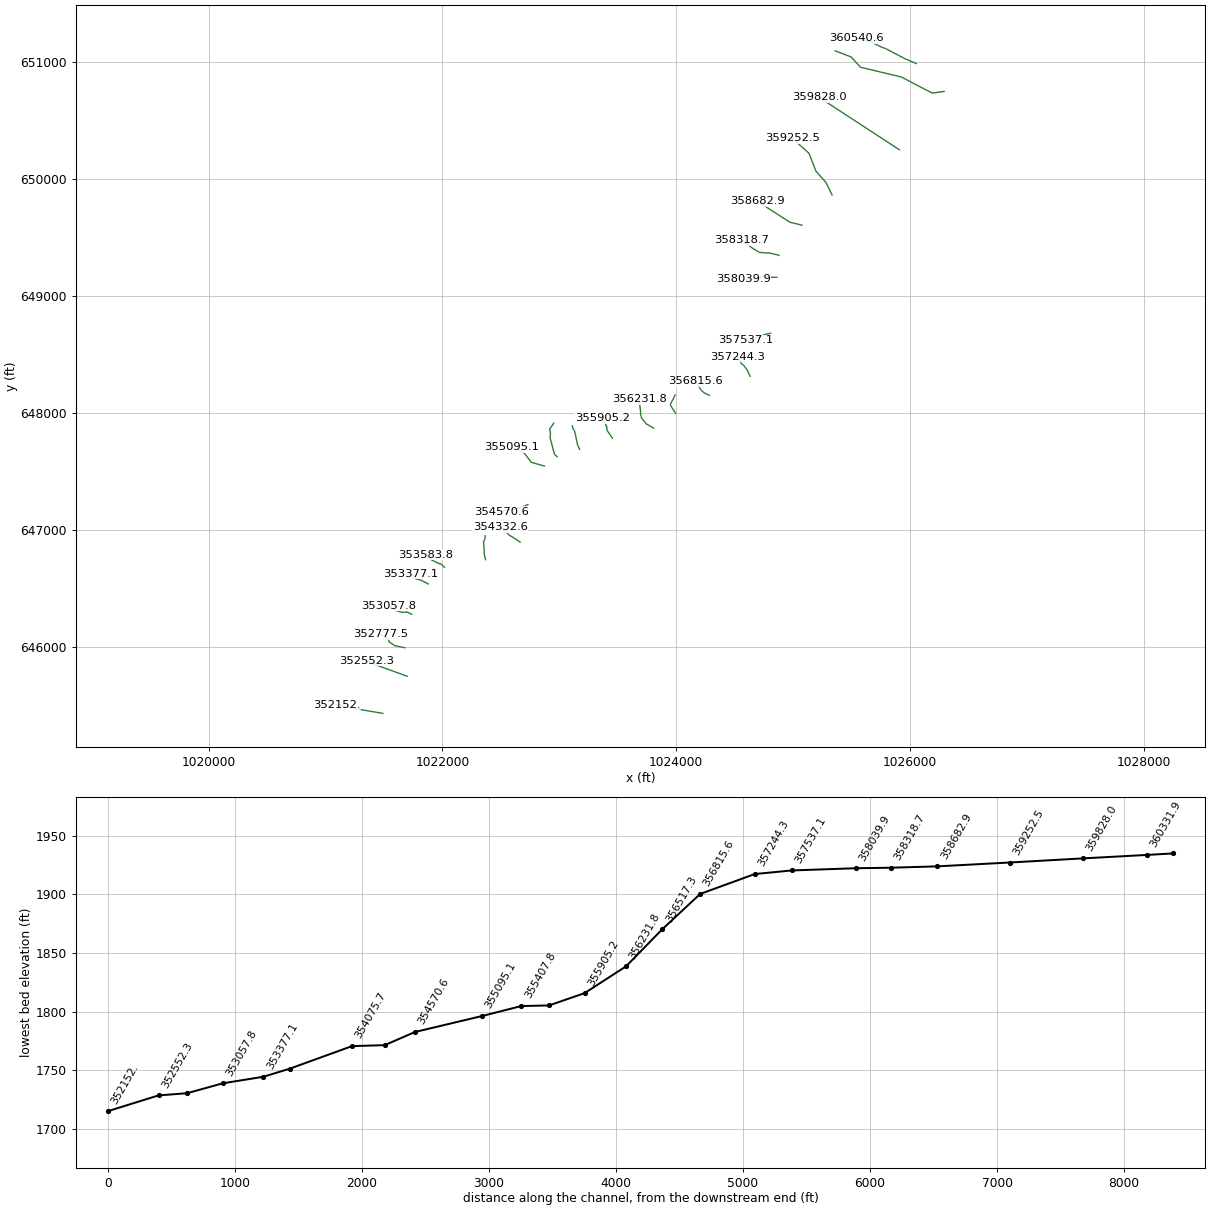
HEC-RAS study lds_broad_rvr.prj: Upper_Broad 3-06-07

--- lds_broad_rvr.g05 (geometry) --- (continued)

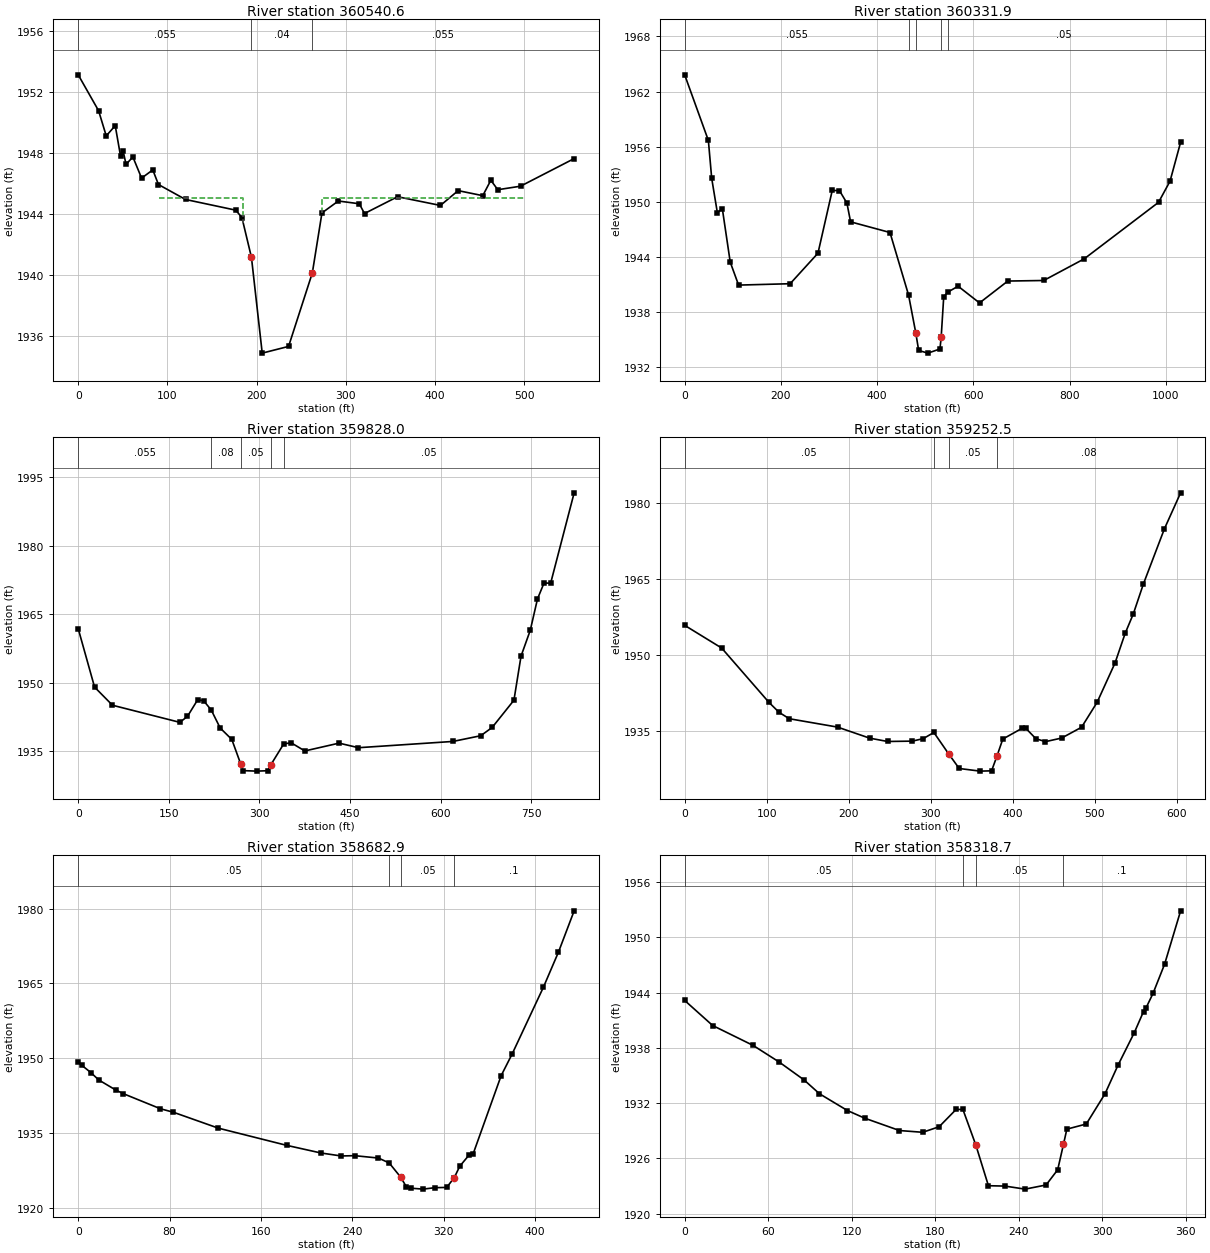
Type RM Length L Ch R = 1 ,360540.6,158.8,208.66,230.82
XS GIS Cut Line= 6
 1026052.7648995  650988.0932263  1025953.754107  651030.7563948
 1025788.7360893  651116.8877693 1025749.2927677   651131.377141
 1025661.6232957  651174.0598627  1025543.034691  651203.7070138
#Sta/Elev= 30
       0  1953.1   22.82 1950.75    31.4  1949.1   41.49 1949.77   47.47 1947.76
   50.18 1948.14   53.62 1947.23   61.24 1947.72   71.01 1946.33   83.58 1946.87
   89.91 1945.91  120.26 1944.93  176.58 1944.23  183.47 1943.74  194.11 1941.14
  206.19 1934.86  235.72  1935.3  262.36 1940.12  273.13 1944.05  291.49 1944.83
  314.93 1944.65  320.82 1944.01  357.82 1945.11  405.89 1944.54  425.76 1945.51
  453.34 1945.18  462.36 1946.19  470.15 1945.57  495.62  1945.8  555.74 1947.61
#Mann= 3 , 0 , 0
       0    .055       0  194.11     .04       0  262.36    .055       0
#XS Ineff= 2 ,-1
      90  184.92    1945  273.39     500    1945
Permanent Ineff=
       T       T
Bank Sta=194.11,262.36
Exp/Cntr=0.5,0.3

Type RM Length L Ch R = 1 ,360331.9,538.04,503.93,430.81
XS GIS Cut Line= 6
 1026290.4285758  650749.6481518 1026189.0955333  650735.1720072
 1025926.1121791  650872.6954113 1025573.8592362  650957.1396184
 1025496.6531014  651043.9965163 1025359.1296974  651097.0757132
#Sta/Elev= 30
       0 1963.83   49.25 1956.69   56.18 1952.57   67.96 1948.82   78.22 1949.29
   94.68 1943.46  112.07 1940.96  219.25 1941.11  277.08 1944.43  306.76 1951.26
  321.83 1951.23  337.25 1949.88  344.89 1947.84  426.78 1946.68   465.4 1939.88
  480.35 1935.78  486.42 1933.85  505.53 1933.56  530.63 1934.01  533.16 1935.26
   538.5 1939.69  546.78 1940.19  568.38 1940.84  612.92 1939.02  671.71  1941.4
  746.35 1941.46   830.4 1943.81  984.99 1949.96 1008.93 1952.26 1030.95  1956.5
#Mann= 5 ,-1 , 0
       0    .055       0   465.4     .08       0  480.35     .05       0
  533.16     .08       0  546.78     .05       0
Bank Sta=480.35,533.16
Exp/Cntr=0.3,0.1

Type RM Length L Ch R = 1 ,359828.0,712.02,575.52,457.64
XS GIS Cut Line= 2
 1025909.2233437  650250.2210419 1025221.6062934  650698.9816457
#Sta/Elev= 30
       0  1961.827.07996 1949.0156.71997 1945.04  168.33 1941.29  180.91 1942.61
  197.71 1946.22  207.48 1946.05  220.23    1944235.0699 1940.05   254.3 1937.55
  269.06 1932.17  273.03 1930.72  295.42 1930.61  314.13  1930.7  318.56 1931.92
  340.31 1936.59   352.6 1936.81  375.21 1935.03  431.89 1936.74  464.01 1935.74
  620.33 1937.11   666.4 1938.36  685.39 1940.18   721.4 1946.14  733.15 1955.79
  748.48 1961.47  760.38 1968.32771.2599 1971.82  782.17 1971.76   821.1 1991.56
#Mann= 5 ,-1 , 0
       0    .055       0  220.23     .08       0  269.06     .05       0
  318.56     .08       0  340.31     .05       0
#XS Ineff= 2 , 0
       0                   352.6       0 1936.81
Permanent Ineff=
       F       F
Bank Sta=269.06,318.56
Exp/Cntr=0.3,0.1

Type RM Length L Ch R = 1 ,359252.5,477.89,569.62,597.98
XS GIS Cut Line= 5
  1025332.590099  649864.1904283 1025279.5108718  649972.7615128
 1025195.0666647   650066.856483 1025134.7493955  650221.2687527
 1024992.4006099  650349.1413936
#Sta/Elev= 30
       0 1955.8745.07996 1951.39  102.64 1940.68  115.06  1938.7  127.47 1937.44
  186.28 1935.79  225.39 1933.61  247.29 1932.95  277.41 1933.02  290.72 1933.51
  303.69 1934.73  321.56 1930.54  334.57 1927.62  359.96  1927.1  374.02 1927.16
  380.58 1930.07   387.7 1933.43  411.06 1935.54  415.43  1935.6  428.09 1933.49
  439.73 1932.92  459.45 1933.63  483.68 1935.76  502.61 1940.67  524.48 1948.44
536.8199 1954.29  546.74 1958.12  559.11 1964.06  584.71 1974.94  604.41 1982.02
#Mann= 4 ,-1 , 0
       0     .05       0  303.69     .08       0  321.56     .05       0
  380.58     .08       0
#XS Ineff= 2 , 0
       0   303.6 1934.72  415.43       0  1935.6
Permanent Ineff=
       F       F
Bank Sta=321.56,380.58
Exp/Cntr=0.3,0.1

Type RM Length L Ch R = 1 ,358682.9,321.87,364.19,358.42
XS GIS Cut Line= 3
  1025074.432096  649606.0324253 1024973.0990838  649630.1593633
 1024695.6395547  649808.6985104
#Sta/Elev= 30
       0 1949.36 2.98999 1948.64      11 1947.1717.96997 1945.68   33.09 1943.63
39.48999 1942.9371.97998 1939.9183.32999 1939.21  122.63 1936.03  182.39 1932.59
  212.36 1931.06  230.15 1930.46  242.02 1930.52  262.81 1930.04   272.2 1929.06
  282.15 1926.25  287.15 1924.32  291.56    1924  301.93 1923.82  312.21 1924.11
  322.53 1924.16   329.2 1926.13  333.97  1928.4  342.47 1930.74  345.63 1930.84
  370.21 1946.54  379.92 1950.92  407.21 1964.25   420.4 1971.29  434.11 1979.54
#Mann= 4 ,-1 , 0
       0     .05       0   272.2     .08       0  282.15     .05       0
   329.2      .1       0
Bank Sta=282.15,329.2
Exp/Cntr=0.3,0.1

Type RM Length L Ch R = 1 ,358318.7,202.81,278.76,320.05
XS GIS Cut Line= 6
 1024878.2215956  649347.6642113 1024807.9091137  649365.8933733
 1024712.8570095  649372.4038034 1024656.8674255  649404.9558632
 1024599.5757736  649447.9246172 1024556.6070196  649476.5704432
#Sta/Elev= 30
       0 1943.14    20.1 1940.42   49.16 1938.26   67.84 1936.46    85.7 1934.52
   96.85 1933.01  116.93 1931.19  129.35 1930.36  154.31 1929.02  170.98 1928.83
  182.77 1929.43  194.98 1931.31  199.87 1931.31   209.1 1927.47   218.2 1923.03
  230.08 1922.99  244.54 1922.66  259.62 1923.11  267.95 1924.76  272.13 1927.53
  274.54 1929.17  288.52 1929.73  301.99 1933.02  311.28 1936.11  323.01 1939.65
  329.63 1941.94  331.26 1942.28  336.43  1943.9  344.77 1947.08  356.27 1952.87
#Mann= 4 ,-1 , 0
       0     .05       0  199.87     .08       0   209.1     .05       0
  272.13      .1       0
#XS Ineff= 2 , 0
       0  194.98 1931.31               0
Permanent Ineff=
       F       F
Bank Sta=209.1,272.13
Exp/Cntr=0.3,0.1

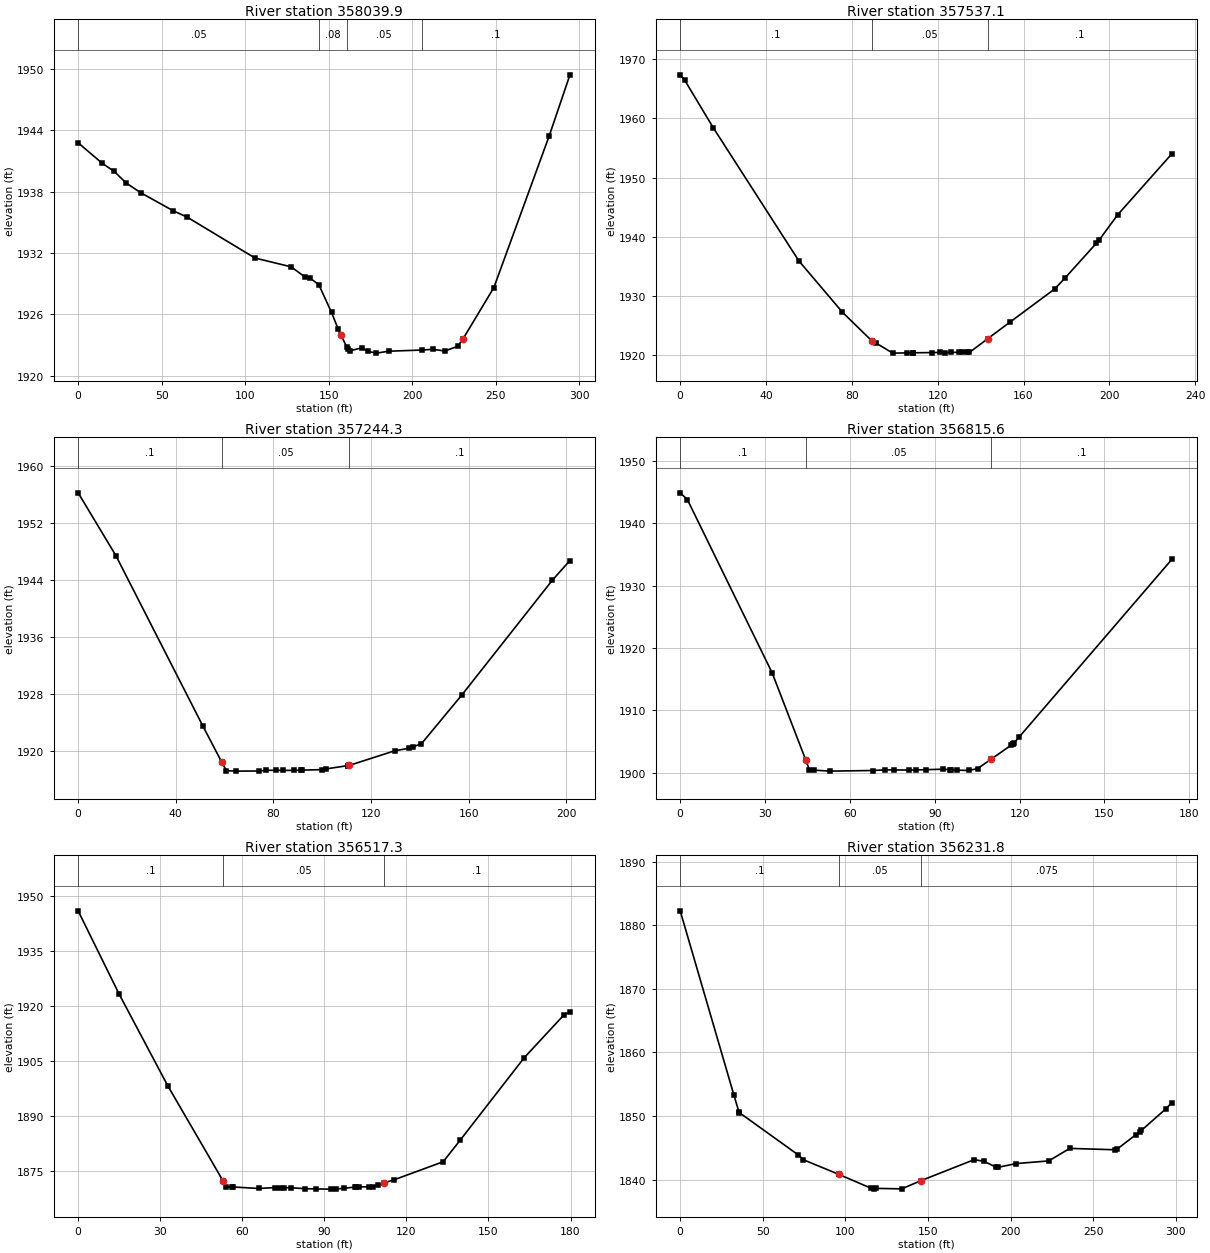
Type RM Length L Ch R = 1 ,358039.9,513.62,502.84,533.63
XS GIS Cut Line= 6
 1024859.9924336  649160.1641992 1024802.7007817  649158.8621313
 1024745.4090996  649171.8829613 1024705.0445115  649153.6537993
 1024671.1903536  649147.1433692 1024572.2320156  649143.2371354
#Sta/Elev= 30
       0 1942.76   14.33 1940.77   21.63 1939.96   28.77 1938.83   37.49 1937.88
   56.67 1936.14   65.36 1935.49  105.92  1931.5  127.55 1930.64  135.57 1929.68
  138.91 1929.53  144.12  1928.9  151.73 1926.18  155.59 1924.61  157.44 1923.98
  160.88 1922.79  161.45 1922.62  163.03 1922.45  169.92 1922.73  173.29 1922.39
  178.58 1922.21  186.05  1922.4  205.64 1922.51  212.36 1922.58  219.56 1922.42
  227.21 1922.87  230.56 1923.63  248.94 1928.62  282.12 1943.46  294.48  1949.4
#Mann= 4 ,-1 , 0
       0     .05       0  144.12     .08       0  160.88     .05       0
  205.64      .1       0
Bank Sta=157.44,230.56
Exp/Cntr=0.3,0.1

Type RM Length L Ch R = 1 ,357537.1,409.88,292.83,207.91
XS GIS Cut Line= 6
 1024806.6070156  648682.2996333 1024750.6174316  648667.9767052
 1024721.9716056  648651.0496111 1024695.9299457  648649.7475432
 1024642.5445277  648618.4975513 1024593.0653435  648619.7996192
#Sta/Elev= 27
       0 1967.37    2.15 1966.44   15.41 1958.43   55.29 1935.93   75.58 1927.26
   89.35 1922.39   91.07 1922.08   99.06 1920.33  105.82 1920.37  108.43 1920.39
  108.58 1920.39  117.14 1920.42  120.99 1920.45  123.54 1920.43  126.44 1920.46
  129.73 1920.47  131.22 1920.47  133.88 1920.45  134.77 1920.44  143.34 1922.77
  153.62 1925.55  174.47 1931.16  179.27 1932.99  193.83 1938.86  195.09 1939.37
  203.89 1943.71   229.2 1954.05
#Mann= 3 , 0 , 0
       0      .1       0   89.35     .05       0  143.34      .1       0
Bank Sta=89.35,143.34
Exp/Cntr=0.3,0.1

Type RM Length L Ch R = 1 ,357244.3,429.31,428.71,428.84
XS GIS Cut Line= 6
 1024632.1278637  648312.5079713 1024607.3882716  648365.8933893
 1024576.1382797  648407.5600452 1024560.5132837  648417.9767092
 1024556.6070196  648424.4871393 1024525.3570277  648480.4766931
#Sta/Elev= 25
       0 1956.25   15.44 1947.46   51.16  1923.5   58.84 1918.47   60.73 1917.29
    64.8 1917.23   74.27 1917.25   77.14 1917.35   81.19 1917.34   83.85 1917.34
   88.48 1917.33   91.39 1917.37   91.69 1917.37   99.67 1917.44  101.49 1917.54
  110.59 1918.01  110.69    1918  110.92 1918.02   129.7 1920.09  135.53 1920.43
  137.29 1920.65   140.6 1921.07  157.17 1927.92  194.24 1944.01  201.41 1946.76
#Mann= 3 , 0 , 0
       0      .1       0   58.84     .05       0  110.92      .1       0
Bank Sta=58.84,110.92
Exp/Cntr=0.3,0.1

Type RM Length L Ch R = 1 ,356815.6,322.56,298.25,265.77
XS GIS Cut Line= 5
 1024284.4715975  648149.7475513 1024241.5028435  648169.2787811
 1024214.1591157  648192.7163053 1024207.6486856  648203.1329693
 1024165.9820297  648269.5392173
#Sta/Elev= 26
       0 1944.87    2.54 1943.79   32.52 1916.01   44.37 1902.08    45.7 1900.43
    47.2 1900.42   52.88 1900.26   68.09 1900.36   72.56 1900.46   75.45 1900.45
   80.91 1900.43   83.21 1900.45   86.74 1900.49   92.82 1900.57    95.5 1900.49
    95.8 1900.48   97.88 1900.41  102.19 1900.37   105.2 1900.68  110.01 1902.19
  116.95  1904.4  117.57 1904.61  117.79 1904.66  117.88 1904.69  119.97 1905.79
  173.89 1934.23
#Mann= 3 , 0 , 0
       0      .1       0   44.37     .05       0  110.01      .1       0
Bank Sta=44.37,110.01
Exp/Cntr=0.3,0.1

Type RM Length L Ch R = 1 ,356517.3,271.55,285.51,295.9
XS GIS Cut Line= 6
 1023994.1070135  647996.1016971 1023949.8361916  648066.4142092
 1023951.1382595  648075.5288053 1023956.3465914  648088.5496353
 1023973.2736855  648117.1954612 1023990.2007796  648153.6537851
#Sta/Elev= 30
       0 1945.85   14.96 1923.24   32.77 1898.27   53.03 1872.34   54.22 1870.74
   56.23 1870.77   56.73 1870.75   66.01 1870.35   71.83 1870.59    73.7 1870.57
   75.23 1870.56   77.99 1870.53   83.09 1870.29   86.95 1870.22    92.3 1870.17
   94.29 1870.18   97.02 1870.39  101.25 1870.73  101.75 1870.74  102.59 1870.78
  106.32  1870.8  107.63 1870.81  109.65 1871.22  111.75 1871.85  115.48  1872.7
  133.45 1877.62   139.6 1883.42  163.03 1905.87  177.53 1917.49  179.79 1918.46
#Mann= 3 , 0 , 0
       0      .1       0   53.03     .05       0  111.75      .1       0
Bank Sta=53.03,111.75
Exp/Cntr=0.3,0.1

Type RM Length L Ch R = 1 ,356231.8,331.32,326.55,347.98
XS GIS Cut Line= 6
 1023806.6070316  647869.7996312 1023742.8049497  647906.2579551
 1023702.4403616  647958.3413053 1023694.6278636  647986.9871312
 1023694.6278636  648014.3308893 1023681.6070337  648114.5912952
#Sta/Elev= 26
       0 1882.28   32.51 1853.29   35.49 1850.69   35.75 1850.54   71.42 1843.88
   74.59 1843.11   95.94 1840.82  115.18 1838.67  117.35 1838.49  118.39 1838.61
  134.01 1838.53   145.8 1839.83  177.96 1843.13  183.83 1842.86  190.86 1841.99
  192.38 1841.92  203.28 1842.51  223.03 1842.93  235.78  1844.9  263.33 1844.68
  264.55 1844.81  275.66 1847.03  278.49 1847.53  279.09 1847.72  294.08 1851.16
  297.64 1852.12
#Mann= 3 , 0 , 0
       0      .1       0   95.94     .05       0   145.8    .075       0
#XS Ineff= 1 ,-1
  177.96     230 1843.13
Permanent Ineff=
       F
Bank Sta=95.94,145.8
Exp/Cntr=0.3,0.1

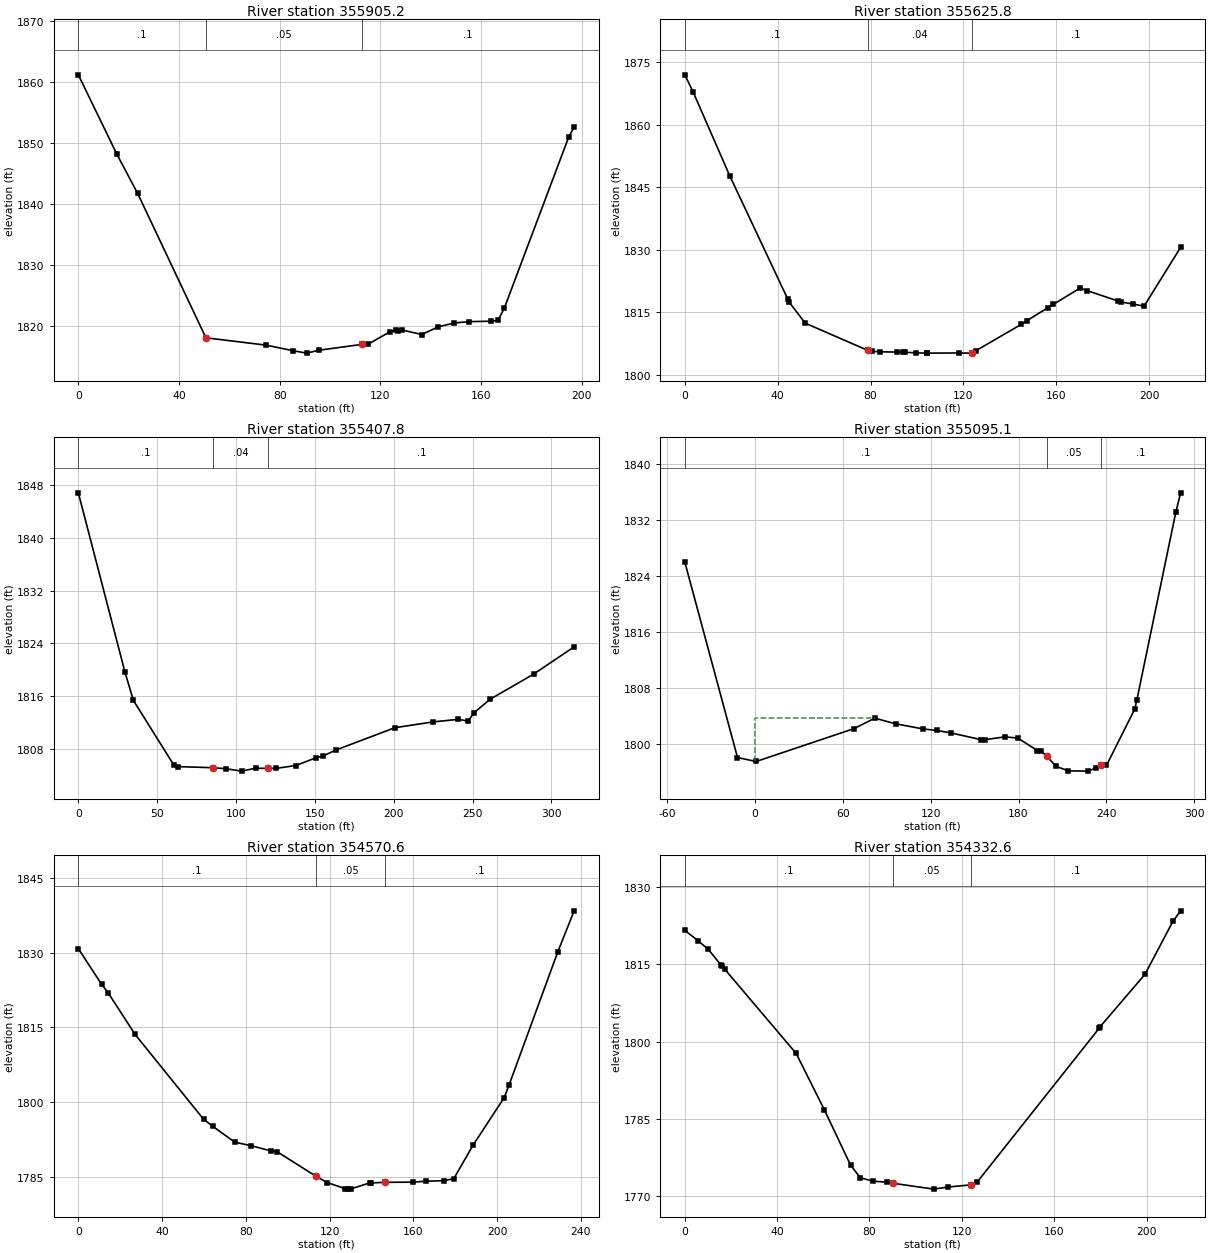
Type RM Length L Ch R = 1 ,355905.2,293.04,279.4,276.02
XS GIS Cut Line= 6
 1023453.7424335  647783.8621231 1023405.5653475  647854.1746353
 1023405.5653475  647881.5183631 1023396.4507816   647894.539193
 1023395.1486835  647908.8621211 1023365.2007594   647953.132943
#Sta/Elev= 23
       0 1861.22   15.35 1848.18   23.57 1841.79   50.67 1818.14   74.74 1816.93
   85.32 1816.02   90.79 1815.63   95.48  1816.1  112.66 1817.06  114.91 1817.05
  123.86 1819.14  126.17 1819.37  126.85 1819.31  128.56 1819.42  136.43 1818.68
  142.94 1819.93   149.3 1820.57  155.29 1820.79  164.05 1820.86  166.73 1820.99
  169.23 1823.02  194.75 1850.98  196.96  1852.7
#Mann= 3 , 0 , 0
       0      .1       0   50.67     .05       0  112.66      .1       0
Bank Sta=50.67,112.66
Exp/Cntr=0.3,0.1

Type RM Length L Ch R = 1 ,355625.8,215.07,218.06,257.57
XS GIS Cut Line= 6
 1023173.7945134  647687.5079511 1023155.5653515  647727.8725391
 1023132.1278575  647837.2475412 1023125.6174274  647852.8725371
 1023117.8049294  647863.2892011 1023109.9924314   647889.330861
#Sta/Elev= 30
       0 1871.95    3.55 1867.89   19.38  1847.7   44.29 1818.21   44.98 1817.39
   51.88 1812.36   78.76 1805.84   78.84 1805.82   80.85  1805.6    84.2 1805.49
   91.55 1805.42      94  1805.4   94.66 1805.39   99.77 1805.23  104.17 1805.17
  104.36 1805.17  118.29 1805.21  123.59 1805.17   125.5 1805.79  144.97 1812.08
  147.37 1812.96  156.45 1816.09   158.7 1816.86  170.27 1820.77  173.38 1820.15
   186.4 1817.72   187.8 1817.45  193.14 1816.94  197.83 1816.44  213.58 1830.55
#Mann= 3 , 0 , 0
       0      .1       0   78.76     .04       0  123.59      .1       0
#XS Ineff= 2 , 0
       0                  170.27       0 1820.77
Permanent Ineff=
       F       F
Bank Sta=78.76,123.59
Exp/Cntr=0.3,0.1

Type RM Length L Ch R = 1 ,355407.8,199.74,312.67,387.82
XS GIS Cut Line= 6
 1022981.0861996  647625.0079672 1022958.9507735  647644.5391971
 1022921.1903515  647785.1642213 1022923.7945175  647834.6433752
 1022915.9820195  647859.3829672 1022951.1382755  647911.4662871
#Sta/Elev= 23
       0  1846.8   29.52 1819.69   34.89 1815.38   60.54 1805.59   63.14 1805.34
   85.22 1805.18   93.72 1805.02  103.52 1804.66  112.39  1805.1  120.57 1805.07
   125.2 1805.07  137.93 1805.51  150.67 1806.68  155.12 1806.95  163.41 1807.86
   200.6 1811.23  224.82 1812.11  240.83  1812.5  247.22 1812.23  250.76 1813.47
  260.96 1815.52  288.61 1819.34  314.39 1823.48
#Mann= 3 , 0 , 0
       0      .1       0   85.22     .04       0  120.57      .1       0
Bank Sta=85.22,120.57
Exp/Cntr=0.3,0.1

Type RM Length L Ch R = 1 ,355095.1,417.25,524.48,546.06
XS GIS Cut Line= 6
 1022872.2914299  647545.4151152 1022761.0340974  647576.8308812
 1022689.4195174  647667.9767213 1022642.5445295  647686.2058832
 1022616.5028393  647691.4142152 1022591.7632775   647708.341279
#Sta/Elev= 26
     -48    1826     -12    1798     .73 1797.43   67.61 1802.14   81.81 1803.63
   96.02 1802.83   114.9 1802.09  124.25 1801.87  133.94 1801.52  154.36 1800.56
     157 1800.55  170.62 1800.96  179.57 1800.78  192.87    1799  195.65 1798.87
  199.16 1798.22  205.64 1796.73   214.1 1796.09   227.2 1796.05  232.66 1796.47
  236.44 1796.94   240.1 1796.87   259.4 1804.93  260.78 1806.17  287.54 1833.21
  290.75 1835.91
#Mann= 3 , 0 , 0
     -48      .1       0  199.16     .05       0  236.44      .1       0
#XS Ineff= 2 , 0
       0   81.81 1803.63               0
Permanent Ineff=
       T       F
Bank Sta=199.16,236.44
Exp/Cntr=0.3,0.1

Type RM Length L Ch R = 1 ,354570.6,302.57,238.04,198.93
XS GIS Cut Line= 6
 1022731.0861733  647216.1537851 1022672.4924233  647190.1121251
 1022654.2632614   647188.810027 1022604.7841075   647173.185031
 1022542.2840934   647170.580865 1022505.8257694  647154.9558691
#Sta/Elev= 27
       0 1830.83    11.1 1823.67    14.2 1821.99   27.06 1813.62   59.83 1796.54
   64.12 1795.15   74.72 1791.94    82.4 1791.25   91.89  1790.2   94.88 1790.04
   113.3 1785.15  118.83 1783.83  127.51  1782.6  128.69 1782.51  130.46 1782.59
   139.5 1783.81  139.97 1783.76  146.52 1783.88  159.71 1783.91  165.99  1784.1
  174.75 1784.21  179.32 1784.61   188.5 1791.33  203.42 1800.91  205.76 1803.47
  229.05 1830.25  236.81 1838.43
#Mann= 3 , 0 , 0
       0      .1       0   113.3     .05       0  146.52      .1       0
Bank Sta=113.3,146.52
Exp/Cntr=0.3,0.1

Type RM Length L Ch R = 1 ,354332.6,321.03,256.92,215.37
XS GIS Cut Line= 6
 1022664.6799254  646894.5392091 1022608.6903413  646932.2996311
 1022570.9299496   646954.435027 1022550.0965913  646975.2683852
 1022520.1486975  647003.9142111 1022494.1070073  647023.4454712
#Sta/Elev= 22
       0 1821.64    5.81  1819.6   10.14 1817.95   15.66 1814.92   16.13 1814.78
   17.28 1814.09   48.22 1797.71   60.44 1786.74   71.81 1775.96   76.03 1773.51
   81.33 1772.87   87.42 1772.64   89.98 1772.45  107.87  1771.3  114.01 1771.71
  124.13 1772.14  126.54 1772.62  179.58 1802.66  179.82 1802.86   199.3 1813.07
  211.44 1823.41  214.76 1825.44
#Mann= 3 , 0 , 0
       0      .1       0   89.98     .05       0  124.13      .1       0
Bank Sta=89.98,124.13
Exp/Cntr=0.3,0.1

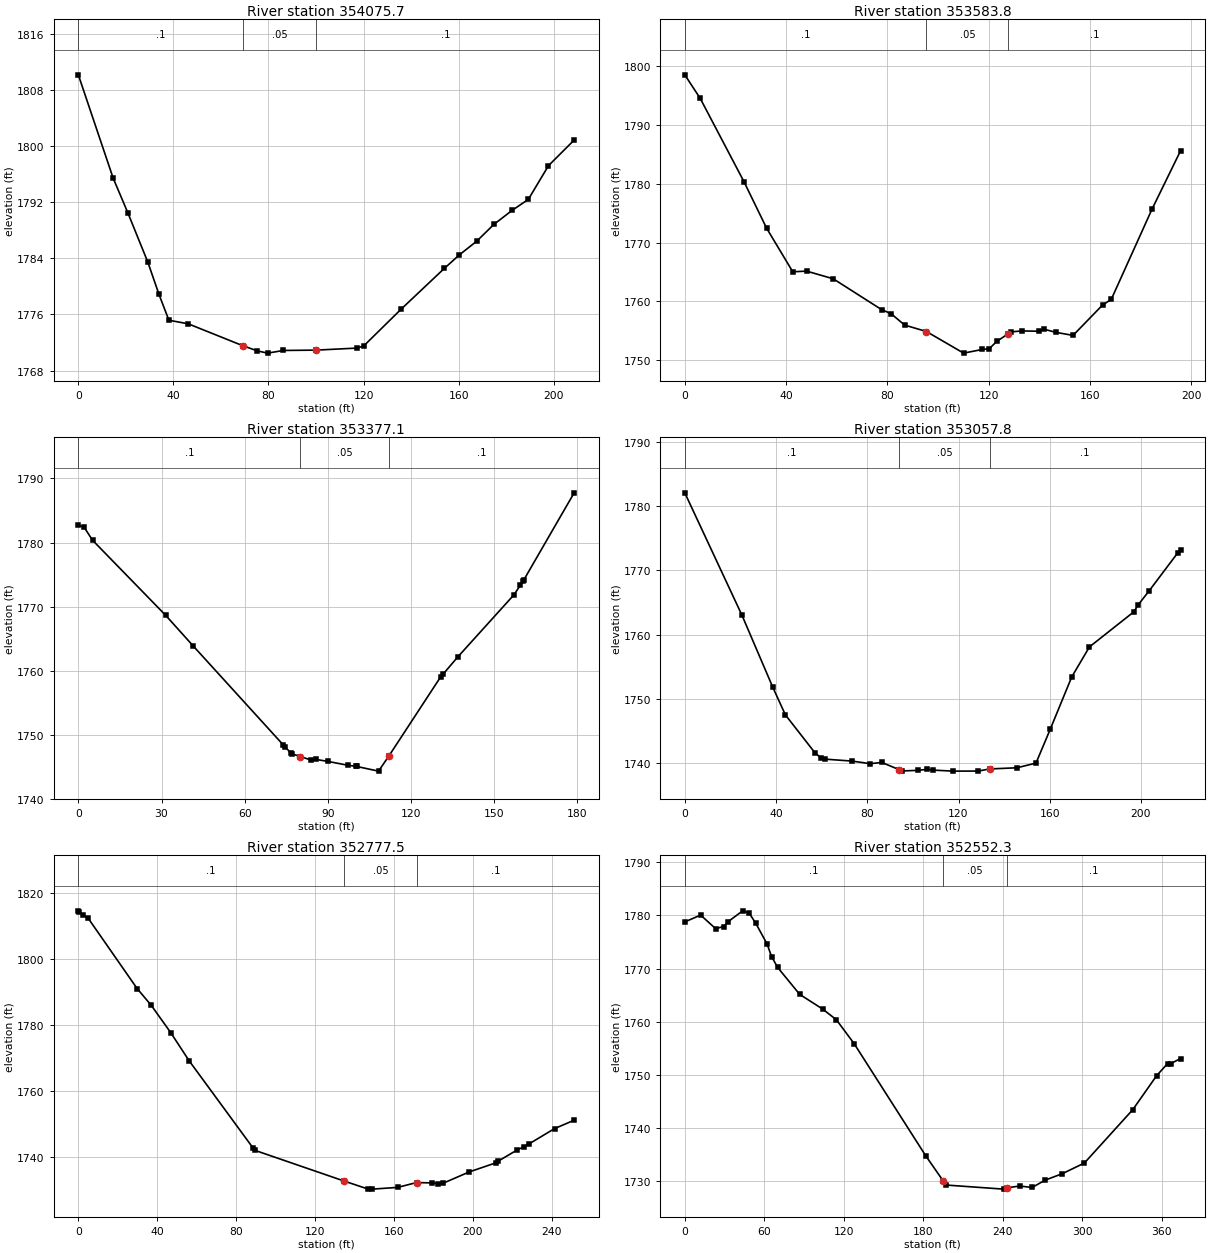
Type RM Length L Ch R = 1 ,354075.7,420.51,491.91,550.17
XS GIS Cut Line= 6
 1022369.1070093   646744.799619 1022357.3882775  646790.3725391
 1022357.3882775  646812.5079651 1022352.1799455  646897.1433751
 1022363.8986773   646923.185035 1022365.2007755   646949.226695
#Sta/Elev= 23
       0 1810.16   14.62 1795.46   20.83 1790.49   29.28 1783.42    33.9 1778.89
    38.1 1775.17   46.24 1774.66   69.19 1771.54   75.31  1770.8   79.66 1770.48
    86.3 1770.86  100.15 1770.91  117.25  1771.2  120.07  1771.5  135.83 1776.75
     154 1782.56  160.34 1784.49  167.73 1786.47  174.84 1788.83  182.55 1790.84
  189.35  1792.4  197.83 1797.21  208.63 1800.86
#Mann= 3 , 0 , 0
       0      .1       0   69.19     .05       0  100.15      .1       0
Bank Sta=69.19,100.15
Exp/Cntr=0.3,0.1

Type RM Length L Ch R = 1 ,353583.8,207.76,206.68,222.65
XS GIS Cut Line= 6
 1022017.5445093  646679.6954692 1021986.2945174  646708.3412951
 1021971.9715893  646710.9454611 1021908.1695073  646740.8933852
 1021897.7528433  646756.5183811 1021858.6903534  646786.4663052
#Sta/Elev= 26
       0 1798.57    6.11 1794.54   23.36 1780.37   32.28 1772.46   42.62 1765.02
   48.07 1765.14    58.6 1763.83   77.65 1758.59   81.45 1757.88   86.77 1755.95
   95.39 1754.85  110.06 1751.17  117.49  1751.8   120.2 1751.93  123.18 1753.18
  127.69 1754.47   128.9  1754.8  133.13 1754.95  139.63  1754.9  141.62 1755.27
  146.46 1754.71  153.26 1754.19  164.96 1759.38  168.34 1760.31  184.38 1775.64
  195.73 1785.66
#Mann= 3 , 0 , 0
       0      .1       0   95.39     .05       0  127.69      .1       0
#XS Ineff= 2 , 0
       0                  141.62       0 1755.27
Permanent Ineff=
       F       F
Bank Sta=95.39,127.69
Exp/Cntr=0.3,0.1

Type RM Length L Ch R = 1 ,353377.1,300.98,319.32,343.79
XS GIS Cut Line= 6
 1021879.5236813   646536.466279 1021813.1174334  646570.3204671
 1021775.3570113   646579.435033 1021759.7320153  646588.5496291
 1021749.3153514  646611.9871231 1021731.0861894  646623.7058852
#Sta/Elev= 26
       0 1782.68    2.07  1782.4    5.11 1780.36   31.47 1768.65   41.36 1763.89
   73.94  1748.4   74.56  1748.1   76.57  1747.2   77.05 1747.03   80.02 1746.61
   83.99 1746.05    85.8 1746.15   90.07 1745.84    97.4 1745.23  100.02 1745.09
  100.37 1745.06  108.25 1744.33  111.95 1746.66  130.61    1759  131.49 1759.43
  136.77 1762.11  157.14 1771.86  159.44 1773.36  160.53 1774.03  160.68 1774.18
  178.81 1787.75
#Mann= 3 , 0 , 0
       0      .1       0   80.02     .05       0  111.95      .1       0
Bank Sta=80.02,111.95
Exp/Cntr=0.3,0.1

Type RM Length L Ch R = 1 ,353057.8,311.27,280.24,251.42
XS GIS Cut Line= 6
 1021736.2945214  646277.3517171 1021702.4403635  646295.5808791
 1021652.9611793  646294.2787809 1021611.2945234  646307.2996109
 1021565.7216034  646330.7371351 1021538.3778453  646351.5704631
#Sta/Elev= 28
       0 1782.05    25.1 1762.97   38.45  1751.9   44.09  1747.5   57.02 1741.61
   59.87 1740.75   61.29 1740.61   73.43  1740.3   81.29  1739.9   86.37 1740.09
   94.04 1738.96    95.4 1738.77  102.28 1738.86  106.23 1739.02  108.68  1738.9
  117.63 1738.74  128.68 1738.75  133.63 1739.08   145.6 1739.26  153.97 1739.99
   160.2 1745.24  169.64  1753.4   177.4 1758.07   196.9 1763.54  198.81 1764.64
  203.58  1766.8  216.04 1772.67  217.38 1773.16
#Mann= 3 , 0 , 0
       0      .1       0   94.04     .05       0  133.63      .1       0
Bank Sta=94.04,133.63
Exp/Cntr=0.3,0.1

Type RM Length L Ch R = 1 ,352777.5,236.78,225.26,255.45
XS GIS Cut Line= 6
 1021678.4176987  645991.0286648 1021591.7632633  646009.1225289
 1021543.5861773   646041.674619 1021539.6799434  646062.5079469
 1021533.1695133   646071.622543 1021469.3674313   646105.476701
#Sta/Elev= 26
       0 1814.69     .44 1814.32     2.5 1813.38    4.87 1812.55    29.8 1791.14
   36.99 1786.03   46.82  1777.8   56.17 1769.25   88.52 1742.86   89.54 1742.08
  134.81 1732.77  146.78 1730.37  149.03 1730.32  161.93 1730.84  171.52 1732.31
  179.18 1732.21  182.55 1732.02  185.06 1732.12  198.27 1735.54  211.81  1738.3
  212.77 1738.74  222.59 1742.21  226.16 1743.22  228.78  1744.1  241.52 1748.67
  251.47 1751.21
#Mann= 3 , 0 , 0
       0      .1       0  134.81     .05       0  171.52      .1       0
Bank Sta=134.81,171.52
Exp/Cntr=0.3,0.1

Type RM Length L Ch R = 1 ,352552.3,385.98,400.3,429.1
XS GIS Cut Line= 6
  1021698.433428  645747.2008543 1021464.1590993   645832.039211
 1021443.3257714   645842.455875 1021406.8674474   645858.080871
 1021378.2215912   645865.893369 1021349.5757653  645881.5183649
#Sta/Elev= 30
       0 1778.79   11.95 1780.08   23.28 1777.52    29.3 1777.92   32.75 1778.84
   43.69 1780.88   48.62 1780.44   53.44  1778.6   62.15 1774.62   65.52 1772.26
   70.14  1770.2   86.78 1765.13  104.23 1762.34  114.46 1760.35  127.86 1755.85
  181.85 1734.74  195.21 1729.94  197.31 1729.19  240.68 1728.42  243.05 1728.68
  253.02    1729  262.36 1728.73  271.88 1730.09  285.17 1731.34  301.76 1733.34
  338.31  1743.4  356.31  1749.8  364.58 1752.09  366.94 1752.08  374.44 1753.04
#Mann= 3 , 0 , 0
       0      .1       0  195.21     .05       0  243.05      .1       0
Bank Sta=195.21,243.05
Exp/Cntr=0.3,0.1

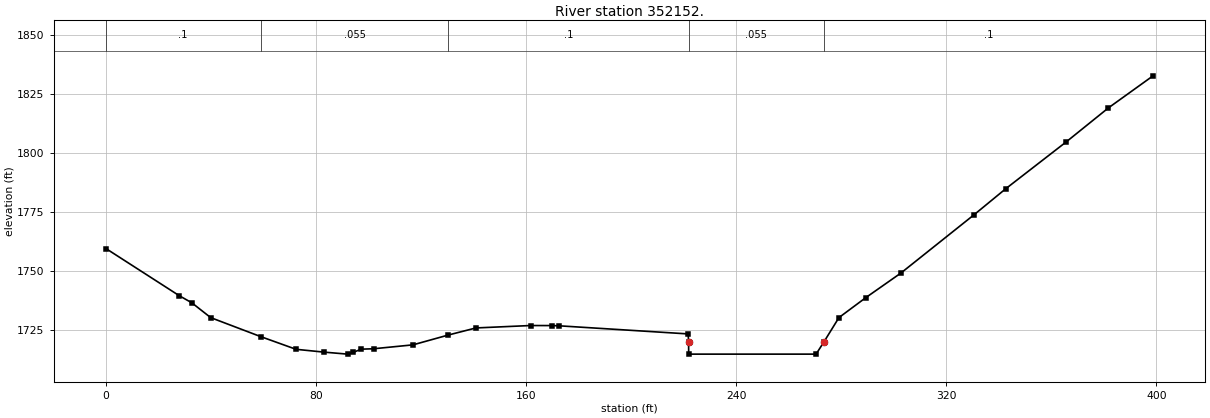
Type RM Length L Ch R = 1 ,352152. ,,,
BEGIN DESCRIPTION:
Hickory Creek Basin US Terminal Section
END DESCRIPTION:
XS GIS Cut Line= 3
 1021490.0848934  645429.7765166 1021247.8263565  645471.0120052
 1021098.3867642   645503.648246
#Sta/Elev= 30
       0 1759.62      28 1739.61    32.7 1736.66    39.9 1730.38    58.9 1722.36
    72.4 1716.97    83.1 1715.77      92 1714.93    94.1 1715.63    97.2 1717.03
   101.9  1717.2   116.9 1718.85   130.4 1723.02   140.9 1726.01   161.7 1727.03
   169.8 1727.01   172.6 1726.91   221.7 1723.48  221.85    1720   221.9 1714.93
   270.4 1714.93  273.33    1720   279.1 1730.39   289.4 1738.89   302.7 1749.24
   330.6 1773.95   342.6  1784.9   365.6  1804.7   381.7 1819.12   398.7 1832.69
#Mann= 5 ,-1 , 0
       0      .1       0    58.9    .055       0   130.4      .1       0
  221.85    .055       0  273.33      .1       0
Bank Sta=221.85,273.33
Exp/Cntr=0.3,0.1
Stream Node=Broad_Creek     ,Main_Branch     , 0 , 0 ,Upstream end
Stream Node=Broad_Creek     ,Main_Branch     , 0 , 1 ,Downstream end

Chan Stop Cuts=-1
Use User Specified Reach Order=0
User Specified Reach Order=Broad_Creek     ,Main_Branch