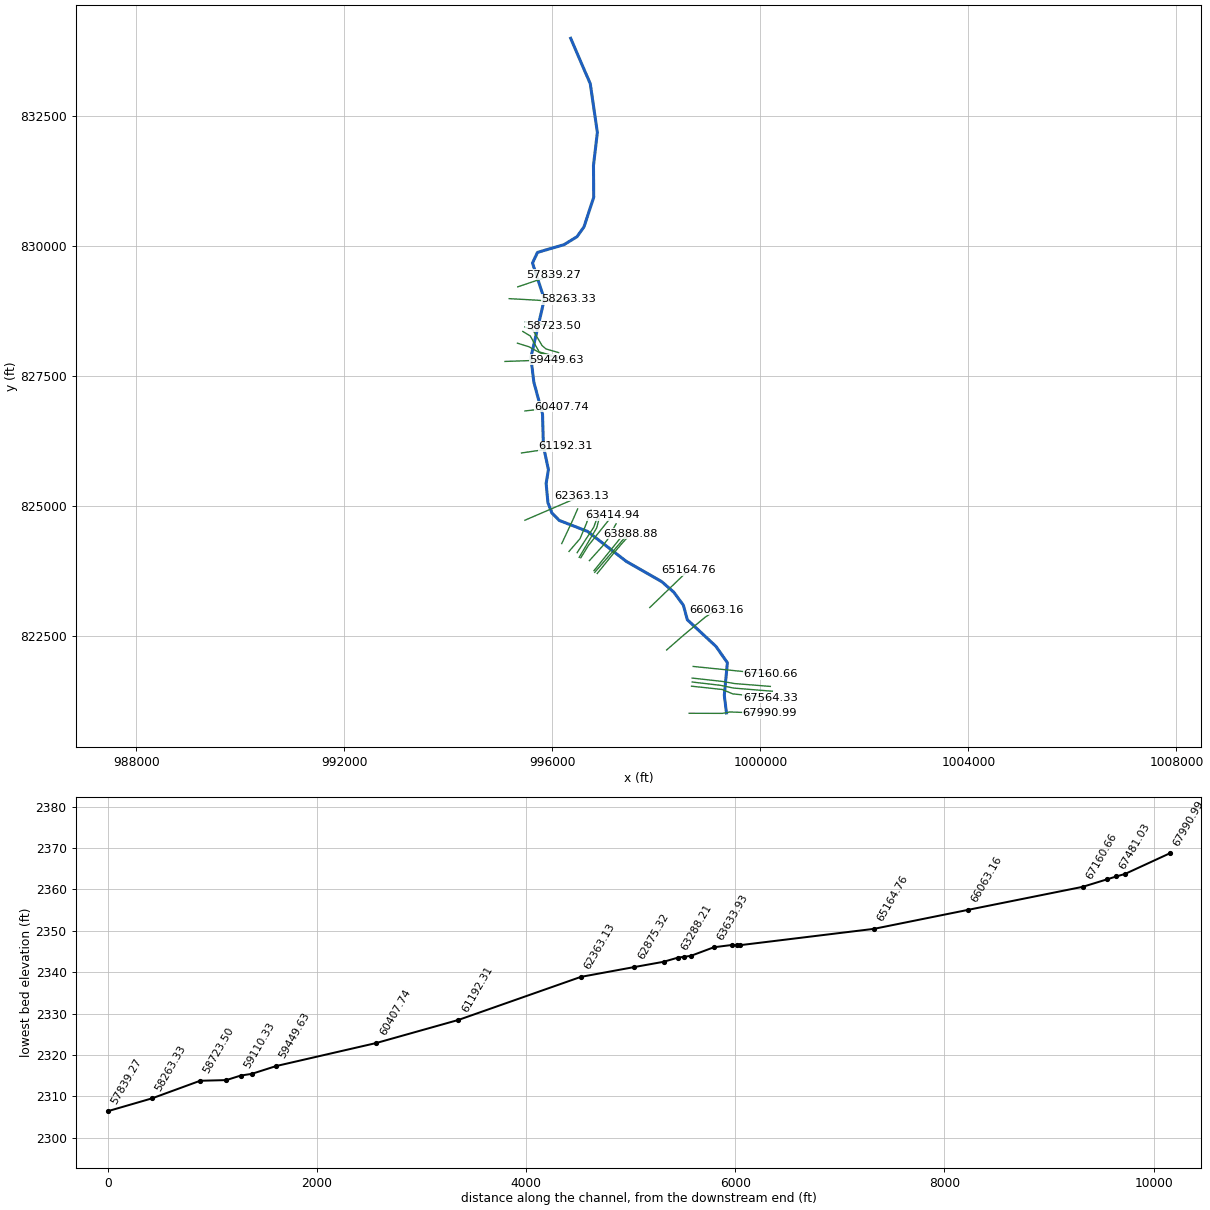
--- lds_cane_rvr_downstream.prj (project) ---

Proj Title=Cane River Downstream LDS
Current Plan=p01
Default Exp/Contr=0.3,0.1
English Units
Geom File=g01
Flow File=f01
Plan File=p01
Y Axis Title=Elevation
X Axis Title(PF)=Main Channel Distance
X Axis Title(XS)=Station
BEGIN DESCRIPTION:
END DESCRIPTION:
DSS Export Rating Curves= 0
DSS Export Rating Curve Sorted= 0
DSS Export Volume Flow Curves= 0
DXF OffsetX= 0
DXF OffsetY= 0
DXF ScaleX= 1
DXF ScaleY= 10

--- lds_cane_rvr_downstream.p01 (plan) ---

Plan Title=Floodway
Program Version=3.13
Short Identifier=FW
Geom File=g01
Flow File=f01
Subcritical Flow
K Sum by GR= 0
Std Step Tol= 0.01
Critical Tol= 0.01
Num of Std Step Trials= 20
Max Error Tol= 0.3
Flow Tol Ratio= 0.001
Split Flow NTrial= 30
Split Flow Tol= 0.02
Split Flow Ratio= 0.02
Log Output Level= 0
Friction Slope Method= 1
Unsteady Friction Slope Method= 2
Unsteady Bridges Friction Slope Method= 1
Parabolic Critical Depth
Global Vel Dist= 0 , 0 , 0
Global Log Level= 0
CheckData=True
Encroach Param=-1 ,0,0, 2
Encroach River=Cane River
Encroach Reach=Downstream
Encroach Node=67990.99
       1    4955    5170
Encroach Node=67564.33
       1 5040.04    5165
Encroach Node=67481.03
       1 4963.61    5080
Encroach Node=67397.30
       1    4955    5068
Encroach Node=67160.66
       1 5041.48 5145.42
Encroach Node=66063.16
       1 4944.68 5053.11
Encroach Node=65164.76
       1 4941.15 5061.11
Encroach Node=63888.88
       1 4953.12  5084.4
Encroach Node=63853.71
       1 4953.02  5103.1
Encroach Node=63805.15
       1 4949.49  5103.1
Encroach Node=63633.93
       1    4950    5080
Encroach Node=63414.94
       1    4900    5055
Encroach Node=63349.40
       1    4872  5039.4
Encroach Node=63288.21
       1    4875 5038.83
Encroach Node=63153.08
       1 4849.04 5031.23
Encroach Node=62875.32
       1 4940.28  5051.8
Encroach Node=62363.13
       1 4956.17    5070
Encroach Node=61192.31
       1 4956.59 5044.35
Encroach Node=60407.74
       1 4949.15 5046.66
Encroach Node=59449.63
       1 4958.79 5068.23
Encroach Node=59217.39
       1    4950    5070
Encroach Node=59110.33
       1    3479    3606
Encroach Node=58973.75
       1 3461.63 3615.18
Encroach Node=58723.50
       1  4903.5  5076.8
Encroach Node=58263.33
       1 4865.76 5037.23
Encroach Node=57839.27
       1 4950.83  5048.6
Encroach Node=57248.63
       1 4946.89  5061.7
Encroach Node=56210.64
       1 4932.09 5046.49
Encroach Node=55465.17
       1 4936.75  5065.1
Encroach Node=54335.02
       1 4940.61 5055.41
Encroach Node=53467.39
       1 4948.04 5067.38
Encroach Node=52642.39
       1 4908.94 5082.28
Encroach Node=52590.38
       1  4398.5 4564.83
Encroach Node=52505.31
       1 4395.91 4562.24
Encroach Node=52453.55
       1 4915.42 5108.72
Computation Interval=1HOUR
Output Interval=1HOUR
Run HTab= 0
Run UNet= 0
Run PostProcess= 0
UNET Theta= 1
UNET Theta Warmup= 1
UNET ZTol= 0.02
UNET ZSATol= 0.05
UNET MxIter= 20
UNET MaxInSteps= 0
UNET DtIC= 0
UNET DtMin= 0
UNET MaxCRTS= 20
UNET WFStab= 2
UNET SFStab= 1
UNET WFX= 1
UNET SFX= 1
UNET DSS MLevel= 4
UNET DZMax Abort= 100
UNET Convert EG Bridges=-1
UNET Use Existing IB Tables=-1
UNET Froude Reduction=False
UNET Froude Limit= 1
UNET Froude Power= 10
Instantaneous Interval=1HOUR
Write IC File= 0
Echo Input=False
Echo Output=False
Write Detailed= 0
Detailed Automatic Start=False, 10

--- lds_cane_rvr_downstream.f01 (steady flow) ---

Flow Title=Floodway Flows
Program Version=3.13
Number of Profiles= 2
Profile Names=PF 1,PF 2
River Rch & RM=Cane River,Downstream      ,67990.99
   18530   18530
River Rch & RM=Cane River,Downstream      ,67564.33
   19060   19060
River Rch & RM=Cane River,Downstream      ,62363.13
   19170   19170
River Rch & RM=Cane River,Downstream      ,59449.63
   19370   19370
River Rch & RM=Cane River,Downstream      ,58263.33
   19580   19580
River Rch & RM=Cane River,Downstream      ,55465.17
   19800   19800
Boundary for River Rch & Prof#=Cane River,Downstream      , 1
Up Type= 0
Dn Type= 1
Dn Known WS=2294.24
Boundary for River Rch & Prof#=Cane River,Downstream      , 2
Up Type= 0
Dn Type= 1
Dn Known WS=2294.74
Set Internal Change=Cane River      ,Downstream      ,67990.99, 2 , 3 ,2390.8
Set Internal Change=Cane River      ,Downstream      ,67990.99, 1 , 3 ,2390.8
DSS Import GetInterval= 0
DSS Import GetPeak= 0
DSS Import FillOption= 0

--- lds_cane_rvr_downstream.g01 (geometry) ---

Geom Title=Cane River - Downstream - Geom
Program Version=3.13

River Reach=Cane River      ,Downstream
Reach XY= 30
      999347.323      821025.509      999305.122      821363.899
      999364.674      821991.975      999144.452       822305.45
      998595.027      822816.672      998517.502       823097.56
      998334.362      823346.997      998101.782      823550.364
      997423.149      823937.992      996672.827      824517.434
      996131.045       824727.86      995990.605      824869.432
      995913.076      825069.426      995879.367      825437.956
      995923.185      825704.242      995826.561      826153.665
      995809.706      826771.631      995643.421      827383.973
      995584.994      827861.489      995844.538      828980.866
      995616.451       829677.17      995713.079      829881.661
      996222.742      830030.003      996471.283      830182.665
      996607.193      830372.564      996794.298      830942.258
      996789.645      831554.772      996864.114      832185.903
      996728.206      833124.222       996351.34      833998.003

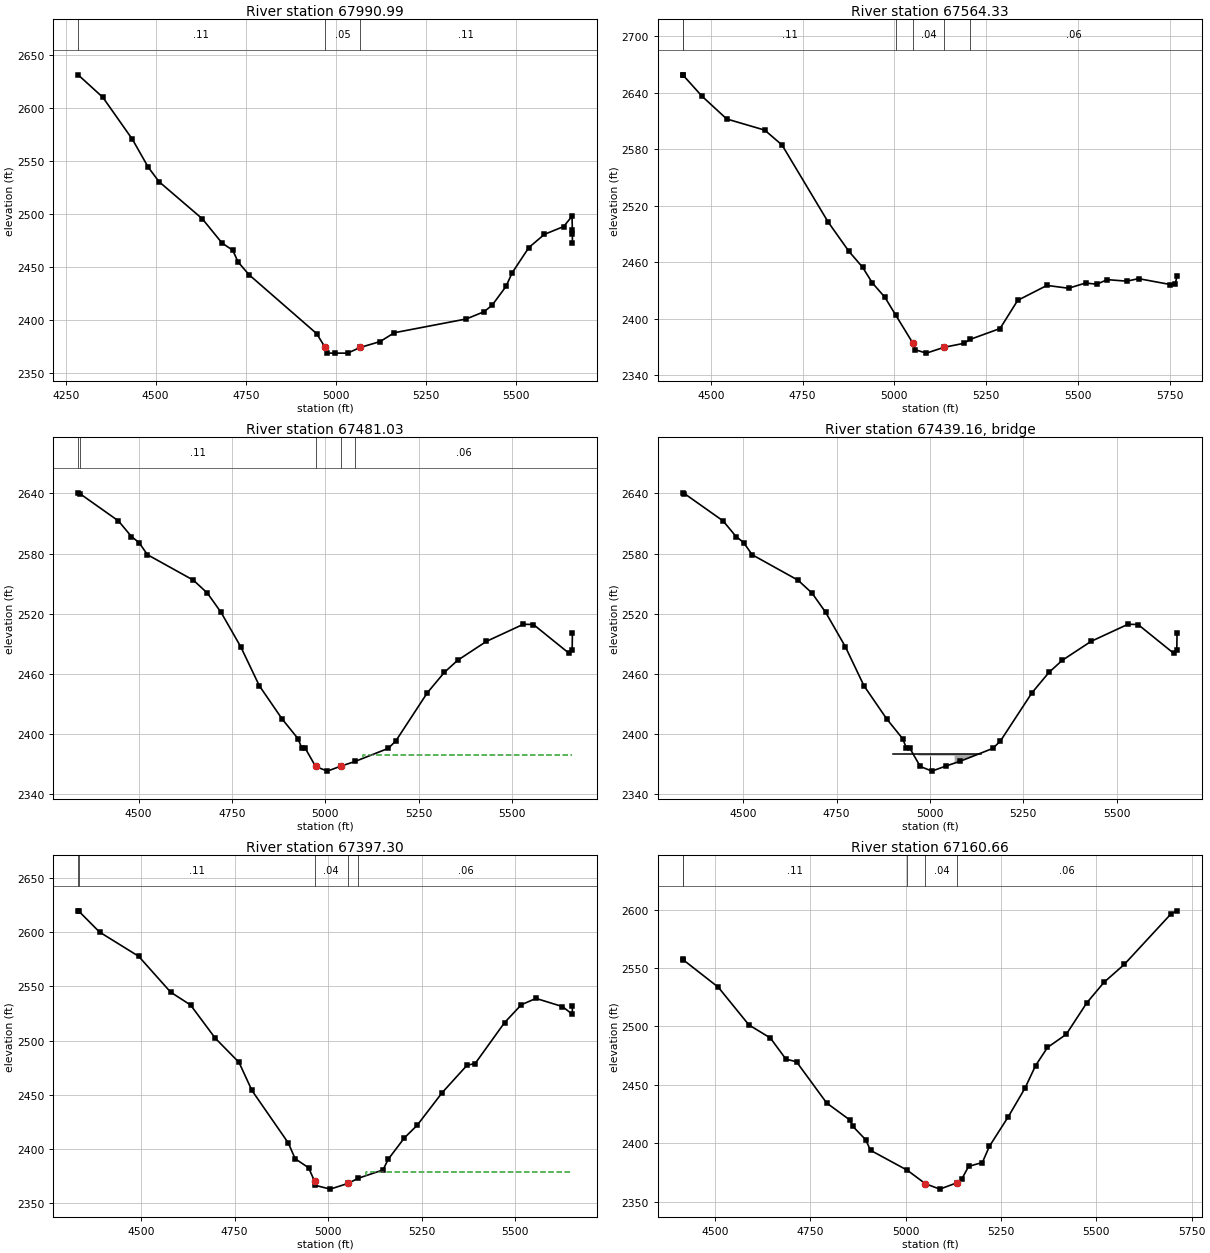
Type RM Length L Ch R = 1 ,67990.99,443.64,426.64,408.86
BEGIN DESCRIPTION:
Adjustment to Manning's n values were attempted, but no reasonable value was able to increase the WSEL to the adjusted effective
END DESCRIPTION:
XS GIS Cut Line= 4
      998630.155      821018.732      999267.957      821016.941
      999411.284      821043.814      1000178.08      821016.941
#Sta/Elev= 30
 4284.64 2631.38 4353.39 2610.08 4435.36  2570.5 4479.41 2544.11 4509.23 2530.54
 4629.57 2495.47  4684.1 2472.67 4714.26 2465.71 4728.61 2454.82 4759.08 2442.74
 4946.99 2387.11 4969.31 2374.78 4974.57 2368.71 4997.19  2368.7 5032.93  2368.7
 5068.27 2374.08 5123.24 2379.62 5162.77 2387.95 5362.68 2400.96 5411.74 2407.77
 5434.01 2413.77 5472.97 2431.73 5489.77 2444.43 5536.32 2468.36 5579.31 2480.77
    5633 2488.19 5656.19 2497.92 5657.11 2484.61 5657.22 2481.44 5657.25 2472.52
#Mann= 3 ,-1 , 0
 4284.64     .11       0 4969.31     .05       0 5068.27     .11       0
Bank Sta=4969.31,5068.27
Exp/Cntr=0.3,0.1

Type RM Length L Ch R = 1 ,67564.33,77.68,83.29,88.91
XS GIS Cut Line= 4
      998674.586      821539.613      999266.072       821476.24
      999468.867      821391.742 1000189.5039773  821315.8855811
#Sta/Elev= 30
 4423.61    2659 4424.79  2658.5 4475.94 2636.35 4543.34 2612.16 4646.97 2600.33
 4694.11 2584.52 4819.49 2502.94 4875.82 2471.99 4913.77 2454.74 4940.11 2438.27
  4974.4 2422.95 5004.44 2403.72 5050.04 2374.67 5056.77 2367.31 5087.43 2363.73
 5136.18 2369.97 5189.04 2374.07 5207.48 2378.42 5288.08 2389.82 5336.24 2419.72
  5415.9 2435.57 5474.73 2432.56 5521.25 2438.13 5551.32 2436.84 5580.52 2441.68
 5633.65 2440.07  5665.6 2442.77 5752.12 2436.51 5765.43 2437.29 5770.41  2445.4
#Mann= 6 ,-1 , 0
 4423.61     .11       0 4424.79     .11       0 5004.44     .11       0
 5050.04     .04       0 5136.18     .15       0 5207.48     .06       0
Bank Sta=5050.04,5136.18
Exp/Cntr=0.5,0.3

Type RM Length L Ch R = 1 ,67481.03,82.59,83.73,84.87
XS GIS Cut Line= 4
      998687.261      821619.886      999232.272      821556.513
      999482.378      821503.446 1000228.0535017  821442.8996046
#Sta/Elev= 30
 4338.17 2640.51 4342.63 2639.74 4446.18 2612.49 4480.87 2596.94 4500.99    2591
 4523.82 2578.83 4646.79 2553.42  4684.2 2540.57 4720.87  2521.3 4773.36 2487.17
 4823.24 2448.23 4884.15 2415.16 4926.58 2395.58 4936.91 2386.23 4945.86  2386.1
 4973.86 2367.81 5005.26 2363.13 5042.33 2368.21 5079.33 2372.74  5168.1 2385.78
 5188.55 2393.13 5273.19 2441.31 5318.57 2461.53 5353.91 2473.53 5431.17 2492.44
 5530.31 2509.54 5557.11 2509.25 5652.05 2480.68 5660.75 2483.67 5661.41 2500.46
#Mann= 5 ,-1 , 0
 4338.17     .11       0 4342.63     .11       0 4973.86     .04       0
 5042.33     .15       0 5079.33     .06       0
#XS Ineff= 2 , 0
       0                    5102       0    2379
Permanent Ineff=
       F       F
Bank Sta=4973.86,5042.33
Exp/Cntr=0.5,0.3

Type RM Length L Ch R = 3 ,67439.16,,,
BEGIN DESCRIPTION:
Unknown Bridge
END DESCRIPTION:
Bridge Culvert--1,0,-1,-1, 0
Deck Dist Width WeirC Skew NumUp NumDn MinLoCord MaxHiCord MaxSubmerge Is_Ogee
35.9,12,2.6,0, 7, 7, , , 0.95, 0, 0,0,,
    4900    4955    4955    5066    5066    5100    5137
    2380    2380    2380    2380    2380    2380    2380
                  2378.5  2378.5
    4900    4955    4955    5066    5066    5100    5137
    2380    2380    2380    2380    2380    2380    2380
                  2378.5  2378.5
Pier Skew, UpSta & Num, DnSta & Num=  ,5000, 2 ,5000, 2 , 0 , 0 , 0 ,,
       1       1
    2360  2379.5
       1       1
    2360  2379.5
BR Coef=-1 , 1 , 1 ,0.9, 0 ,,,0.8,0,1.2,0,
WSPro=,,,, 1 ,,,, 0 ,,,, 0 ,,,,-1 ,-1 ,-1 , 0 , 0 , 0 , 0 , 0
BC Design=,, 0 ,, 0 ,,,,,,

Type RM Length L Ch R = 1 ,67397.30,234.55,236.65,238.75
XS GIS Cut Line= 4
      998687.261      821695.934      999257.622      821632.561
      999502.666      821590.312 1000190.7160672  821535.4364858
#Sta/Elev= 30
  4331.9 2620.02 4334.44 2619.45 4389.16 2600.35 4493.69 2577.93 4579.07 2544.76
 4632.27 2532.89 4698.39 2502.13 4761.85 2479.75 4796.34 2453.77 4893.21 2405.35
 4911.93 2390.58 4947.77 2382.24  4963.7 2369.79 4966.08 2365.94 5005.58 2362.47
 5052.68 2367.74 5080.76 2372.57 5146.58 2380.23 5160.73 2390.21 5203.82 2409.93
 5237.86 2421.57 5305.03 2451.89 5371.27 2477.16 5392.78 2478.68 5471.33 2516.52
 5516.12 2533.08 5555.45 2538.97 5626.03 2531.42 5652.42 2524.33 5652.73  2532.3
#Mann= 5 ,-1 , 0
  4331.9     .11       0 4334.44     .11       0  4963.7     .04       0
 5052.68     .15       0 5080.76     .06       0
#XS Ineff= 2 , 0
       0  4924.4 2377.95    5102       0 2377.95
Permanent Ineff=
       F       F
Bank Sta=4963.7,5052.68
Exp/Cntr=0.5,0.3

Type RM Length L Ch R = 1 ,67160.66,1073.58,1097.49,1121.41
XS GIS Cut Line= 2
      998707.195      821919.294 1000196.7485086  821768.0650656
#Sta/Elev= 30
 4415.29 2557.38 4416.22  2557.1 4508.51 2533.56  4588.7  2501.3 4644.95 2490.11
  4685.7 2472.03  4713.6  2469.7 4792.68 2434.43 4853.75 2419.79 4861.27 2414.43
 4894.89    2403 4907.81 2393.88 5004.33 2376.78 5051.48 2365.29 5089.35 2360.63
 5135.42 2366.17 5146.94 2369.14 5164.98 2380.12 5201.03 2383.42 5219.55 2397.32
  5269.4 2422.82 5312.97 2447.17 5340.62  2466.4 5371.92 2481.98 5421.03 2493.19
 5475.33 2520.35 5520.55 2537.91 5573.29 2553.08  5696.2 2596.51  5711.7 2599.01
#Mann= 5 ,-1 , 0
 4415.29     .11       0 4416.22     .11       0 5004.33     .15       0
 5051.48     .04       0 5135.42     .06       0
Bank Sta=5051.48,5135.42
Exp/Cntr=0.3,0.1

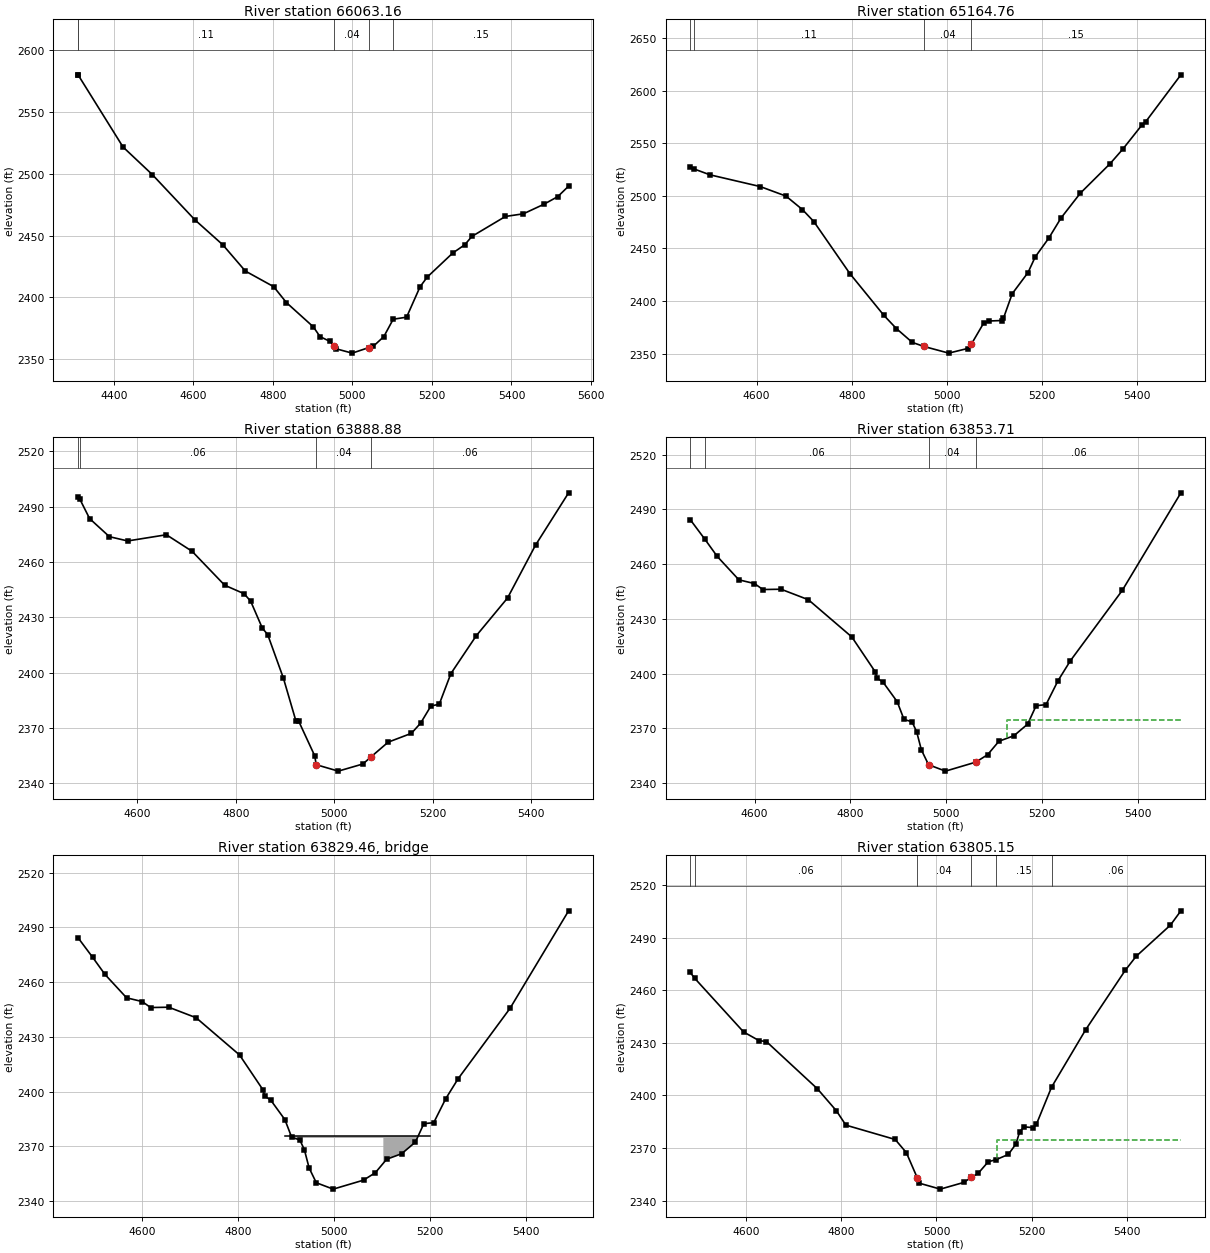
Type RM Length L Ch R = 1 ,66063.16,896.26,898.41,900.55
XS GIS Cut Line= 4
      998197.173      822236.721      998527.106      822524.953
      998939.425      822868.421      999156.224      823009.877
#Sta/Elev= 30
 4310.07 2579.87  4310.9 2579.58 4423.42 2521.56 4496.81 2499.35 4604.03 2462.74
 4674.32 2442.54 4730.89 2421.37 4802.04 2408.77 4834.23 2395.88 4901.81 2376.29
 4918.81 2368.38 4943.82 2364.51 4954.68 2360.78 4958.47 2358.61 4999.59 2355.06
 5041.39 2359.54 5052.59 2360.57 5079.12 2368.41 5102.66 2382.44  5136.3  2384.1
 5170.31 2408.73 5188.53 2416.58 5252.38 2435.92 5282.44 2442.56 5300.58 2449.35
 5384.76 2465.46 5430.01 2467.61 5481.41 2475.29 5516.38 2481.48 5543.67 2489.95
#Mann= 5 ,-1 , 0
 4310.07     .11       0  4310.9     .11       0 4954.68     .04       0
 5041.39     .11       0 5102.66     .15       0
Bank Sta=4954.68,5041.39
Exp/Cntr=0.3,0.1

Type RM Length L Ch R = 1 ,65164.76,1272.79,1275.88,1278.96
XS GIS Cut Line= 2
      997871.841      823051.978      998614.055      823767.445
#Sta/Elev= 30
 4460.58 2527.45 4467.72 2525.62 4502.04  2519.9 4607.61 2508.76 4661.82 2499.68
 4696.24 2486.91 4720.22  2475.5 4796.06 2426.01 4867.42 2386.38 4893.61 2373.87
 4927.04 2360.71 4951.15 2356.88 5003.72 2350.48 5043.17 2354.87 5051.11 2358.87
 5077.11 2379.04 5089.23 2381.01  5115.5 2381.48 5118.63 2383.56  5137.1 2406.92
  5170.3 2427.04 5185.46 2441.91 5213.92 2459.73 5239.73 2478.93 5280.08 2502.39
 5342.66 2530.46  5369.1 2544.11 5408.91 2566.81  5417.7 2570.43 5491.49 2614.91
#Mann= 4 ,-1 , 0
 4460.58     .11       0 4467.72     .11       0 4951.15     .04       0
 5051.11     .15       0
Bank Sta=4951.15,5051.11
Exp/Cntr=0.3,0.1

Type RM Length L Ch R = 1 ,63888.88,35.55,35.17,34.78
XS GIS Cut Line= 4
      996862.326      823707.187      997156.514      824070.596
      997324.374      824269.605      997504.348      824468.615
#Sta/Elev= 30
 4479.45 2495.46 4483.23 2494.12 4503.14 2483.55 4543.32 2473.74 4580.41 2471.42
 4659.03 2474.79 4711.25  2465.8 4777.35 2447.41 4816.88 2442.79 4830.19  2438.7
 4853.78 2424.15 4864.74  2420.6 4896.68 2396.92  4921.8 2373.97  4927.9  2373.5
 4960.33 2354.78 4963.12 2350.05 5008.03 2346.55 5058.05 2350.43  5074.4 2354.26
 5109.28 2362.26 5156.47 2367.05 5175.22 2372.59 5196.18 2381.91 5213.02 2382.82
 5236.64 2399.45 5288.24 2420.02 5351.69 2440.47 5408.49 2469.14 5475.68 2497.53
#Mann= 4 ,-1 , 0
 4479.45     .06       0 4483.23     .06       0 4963.12     .04       0
  5074.4     .06       0
Bank Sta=4963.12,5074.4
Exp/Cntr=0.5,0.3

Type RM Length L Ch R = 1 ,63853.71,47.6,48.56,49.51
XS GIS Cut Line= 2
      996813.338      823728.763      997483.407      824503.025
#Sta/Elev= 30
 4465.64  2484.4 4496.34  2473.6 4522.05 2464.22 4567.16  2451.4 4599.75 2449.35
 4617.25 2446.08 4655.13 2446.25 4712.18  2440.5 4802.89 2420.08 4851.35 2401.13
 4855.55 2397.53 4868.05  2395.3 4897.48 2384.65 4911.81 2374.87  4928.5 2373.58
 4938.15 2368.15 4948.02 2358.18 4963.02 2350.04 4998.33 2346.54 5061.56 2351.46
 5086.25 2355.54 5109.82 2362.91 5141.28 2365.96 5169.87 2372.33 5187.48 2382.41
 5208.12 2382.98 5233.22 2396.13 5258.99 2407.04 5367.21 2445.58 5489.59 2499.09
#Mann= 4 ,-1 , 0
 4465.64     .06       0 4496.34     .06       0 4963.02     .04       0
 5061.56     .06       0
#XS Ineff= 2 , 0
       0                    5126       0  2374.6
Permanent Ineff=
       F       F
Bank Sta=4963.02,5061.56
Exp/Cntr=0.5,0.3

Type RM Length L Ch R = 3 ,63829.46,,,
BEGIN DESCRIPTION:
Unknown Structure
END DESCRIPTION:
Bridge Culvert--1,0,-1,-1, 0
Deck Dist Width WeirC Skew NumUp NumDn MinLoCord MaxHiCord MaxSubmerge Is_Ogee
21.3,6,2.6,0, 5, 5, , , 0.95, 0, 0,0,,
    4897    4897    5103    5103    5200
  2375.6  2375.6  2375.6  2375.6  2375.6
          2374.6  2374.6
    4897    4897    5103    5103    5200
  2375.6  2375.6  2375.6  2375.6  2375.6
          2374.6  2374.6
BR Coef=-1 , 0 , 0 ,, 0 ,,,0.8,0,,0,
WSPro=,,,, 1 ,,,, 0 ,,,, 0 ,,,,-1 ,-1 ,-1 , 0 , 0 , 0 , 0 , 0
BC Design=,, 0 ,, 0 ,,,,,,

Type RM Length L Ch R = 1 ,63805.15,170.34,171.23,172.12
XS GIS Cut Line= 2
      996798.966      823761.099      997447.479      824560.511
#Sta/Elev= 30
 4483.39 2470.16 4492.37 2466.92 4595.34  2436.2 4627.35 2431.32 4643.35 2430.69
 4750.24 2403.78 4790.12 2391.23 4809.92 2383.07 4913.38 2374.89 4936.81 2367.39
 4959.49 2353.16 4963.06 2350.04 5008.14 2346.58  5056.8 2350.36 5073.02 2353.22
 5087.73 2355.65 5108.51 2362.16 5125.42 2363.43 5150.76 2366.35 5166.42 2372.21
 5174.78 2379.37 5183.97 2382.08 5203.26 2381.65 5209.68 2383.58 5241.46 2404.73
 5313.07 2437.49  5396.1 2471.37 5418.67 2479.26 5490.84 2497.13 5512.77 2505.27
#Mann= 6 ,-1 , 0
 4483.39     .06       0 4492.37     .06       0 4959.49     .04       0
 5073.02     .11       0 5125.42     .15       0 5241.46     .06       0
#XS Ineff= 2 , 0
       0                    5126       0  2374.6
Permanent Ineff=
       F       F
Bank Sta=4959.49,5073.02
Exp/Cntr=0.5,0.3

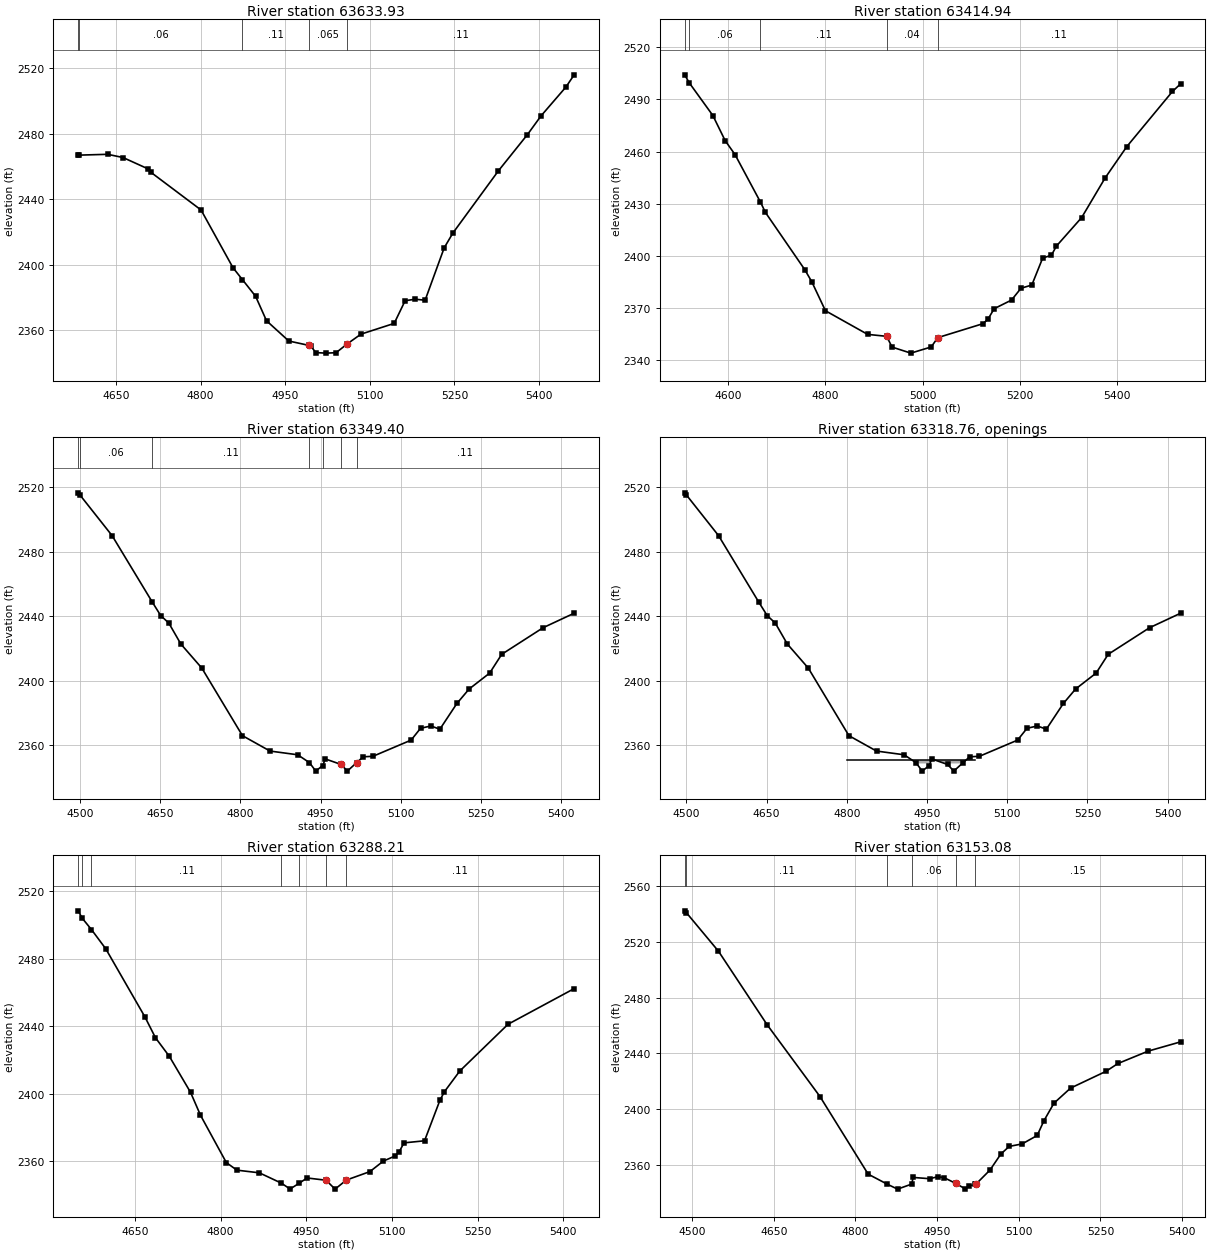
Type RM Length L Ch R = 1 ,63633.93,219.67,218.98,218.3
XS GIS Cut Line= 4
      996711.771      823954.651      996959.235      824228.073
      997059.605      824359.592      997224.004      824662.433
#Sta/Elev= 30
  4583.3 2467.16 4584.73 2466.97 4635.41 2467.47 4662.66 2465.51 4707.35 2458.53
 4712.26 2456.44 4800.99 2433.46 4857.62 2398.17 4874.26 2390.93 4897.62 2380.75
 4916.96 2365.81 4956.46 2353.43 4992.33 2350.74    4995 2350.48 5004.47 2346.35
 5022.18 2346.03 5040.19 2346.28 5060.14  2351.7 5084.25 2357.61 5143.22 2364.19
 5162.59 2378.04 5180.29 2378.96 5198.02 2378.35 5231.85 2410.37 5247.19 2419.36
 5327.89 2457.39 5379.31  2479.5 5403.53 2490.99 5447.45 2508.53 5462.11 2516.02
#Mann= 5 ,-1 , 0
  4583.3     .06       0 4584.73     .06       0 4874.26     .11       0
 4992.33    .065       0 5060.14     .11       0
Bank Sta=4992.33,5060.14
Exp/Cntr=0.3,0.1

Type RM Length L Ch R = 1 ,63414.94,61.51,65.54,69.57
XS GIS Cut Line= 3
      996545.669      824009.006      996694.017      824248.178
      997156.762      824826.609
#Sta/Elev= 30
 4509.81 2504.19 4519.08 2499.65 4567.88 2480.77 4593.25  2466.3 4613.51  2458.3
 4665.89 2430.98 4676.32 2424.93 4757.25 2392.06 4771.76 2385.07 4799.96 2368.36
 4886.87 2354.76 4926.13 2353.63 4937.19 2347.44    4976 2343.96 5017.89 2347.51
  5031.5 2352.88 5124.12 2360.87  5134.6 2363.34 5147.69 2369.54 5183.48 2374.51
    5203 2381.31 5225.34 2383.17  5247.7 2398.71 5265.65 2400.31 5276.16 2405.64
 5328.07 2422.03 5376.31 2444.78 5421.07 2462.86 5515.14  2494.6 5532.01 2499.01
#Mann= 5 ,-1 , 0
 4509.81     .06       0 4519.08     .06       0 4665.89     .11       0
 4926.13     .04       0  5031.5     .11       0
Bank Sta=4926.13,5031.5
Exp/Cntr=0.5,0.3

Type RM Length L Ch R = 1 ,63349.40,62.31,61.19,60.06
XS GIS Cut Line= 4
       996515.13      824017.989      996710.941      824348.532
      996851.063      824582.068      996919.327      824844.348
#Sta/Elev= 30
 4496.63 2516.66 4499.26 2515.58 4560.08 2490.02 4635.32 2448.69  4650.9  2440.4
 4666.03 2435.75 4688.61 2422.71 4727.83 2407.75 4803.78 2365.77 4855.41  2356.2
 4907.11 2353.89 4929.07 2349.01 4940.93 2343.76 4953.86 2347.19 4958.85  2351.3
 4988.53 2347.85 4999.91 2343.73 5017.46 2349.04 5029.75 2352.63  5047.9 2352.95
 5119.23    2363  5136.9 2370.35 5156.23 2371.79 5173.04 2369.78 5204.87 2385.77
 5227.67 2394.73 5266.13 2404.64 5288.73 2416.32 5366.09 2432.84 5424.18 2441.85
#Mann= 7 ,-1 , 0
 4496.63     .06       0 4499.26     .06       0 4635.32     .11       0
 4929.07    .038       0 4953.86     .06       0 4988.53    .038       0
 5017.46     .11       0
Bank Sta=4988.53,5017.46
Exp/Cntr=0.5,0.3

Type RM Length L Ch R = 4 ,63318.76,,,
BEGIN DESCRIPTION:
Wood Bridges
END DESCRIPTION:
Bridge Culvert--1,0,-1,-1, 0
Deck Dist Width WeirC Skew NumUp NumDn MinLoCord MaxHiCord MaxSubmerge Is_Ogee
23.6,14,2.6,0, 10, 11, , , 0.95, 0, 0,0,,
    4800  4932.5  4932.5  4950.5  4950.5    4975    4975    5015    5015    5040
  2350.5  2350.5  2350.5  2350.5  2350.5  2350.5  2350.5  2350.5  2350.5  2350.5
                  2348.5  2348.5                  2348.5  2348.5
    4800    4915    4915    4933    4933    4964    4975    4975    5015    5015
    5040
  2350.5  2350.5  2350.5  2350.5  2350.5  2350.5  2350.5  2350.5  2350.5  2350.5
  2350.5
                  2348.5  2348.5                          2348.5  2348.5
        
BR Coef=-1 , 0 , 0 ,, 0 ,,,0.8,-1,,0,
WSPro=,,,, 1 ,,,, 0 ,,,, 0 ,,,,-1 ,-1 ,-1 , 0 , 0 , 0 , 0 , 0
BC Mult= 3 ,4400,4966,4400,4966
BC Mult= 3 ,4966,6000,4966,6000
BC Design=,, 0 ,, 0 ,,,,,,

Type RM Length L Ch R = 1 ,63288.21,129.71,135.13,140.55
XS GIS Cut Line= 3
      996475.608       824107.81      996795.392      824598.224
      996892.381      824864.108
#Sta/Elev= 30
 4550.59 2508.36 4557.49 2504.03 4573.82 2497.24 4598.89 2485.84 4667.51 2445.47
  4685.9 2433.16 4710.19 2422.16 4747.25 2400.88 4764.73 2387.27    4810 2359.22
 4828.47 2354.75  4867.8 2353.17 4906.55 2347.02 4921.57 2343.57 4937.88 2347.07
 4951.35 2350.12 4984.73 2348.77 5000.37 2343.51 5020.12 2348.87 5061.46  2353.9
 5084.79 2360.08 5104.58 2363.02  5112.4 2365.47 5121.12 2370.91 5157.06 2372.14
 5184.06 2396.18 5191.95 2401.24 5218.77 2413.46 5303.36 2441.19 5419.08 2462.28
#Mann= 7 ,-1 , 0
 4550.59     .06       0 4557.49     .06       0 4573.82     .11       0
 4906.55    .036       0 4937.88     .06       0 4984.73    .036       0
 5020.12     .11       0
Bank Sta=4984.73,5020.12
Exp/Cntr=0.5,0.3

Type RM Length L Ch R = 1 ,63153.08,279.07,277.76,276.44
XS GIS Cut Line= 4
      996319.319      824131.164      996531.298      824377.275
      996653.455      824668.297      996743.277      824923.391
#Sta/Elev= 30
 4486.35 2542.29 4489.31 2541.04 4548.46 2513.27 4637.62 2460.61 4734.81    2409
 4823.33 2353.28  4858.8 2345.99 4877.37 2342.52 4903.24 2346.14 4905.99 2350.91
  4936.2 2350.01 4951.27 2351.41 4962.54 2350.81 4984.44 2346.58 5002.01  2342.6
 5007.75 2344.78 5020.37 2345.87 5021.23 2346.07 5047.21 2356.26 5067.07 2367.72
  5082.4 2373.18 5106.12 2374.97 5133.78 2381.02  5146.2 2391.63 5164.64 2404.24
 5195.08 2415.03  5260.2 2427.09 5282.16  2432.7 5337.89 2441.62 5397.23 2448.24
#Mann= 6 ,-1 , 0
 4486.35     .11       0 4489.31     .11       0  4858.8     .04       0
 4903.24     .06       0 4984.44     .04       0 5020.37     .15       0
Bank Sta=4984.44,5021.23
Exp/Cntr=0.3,0.1

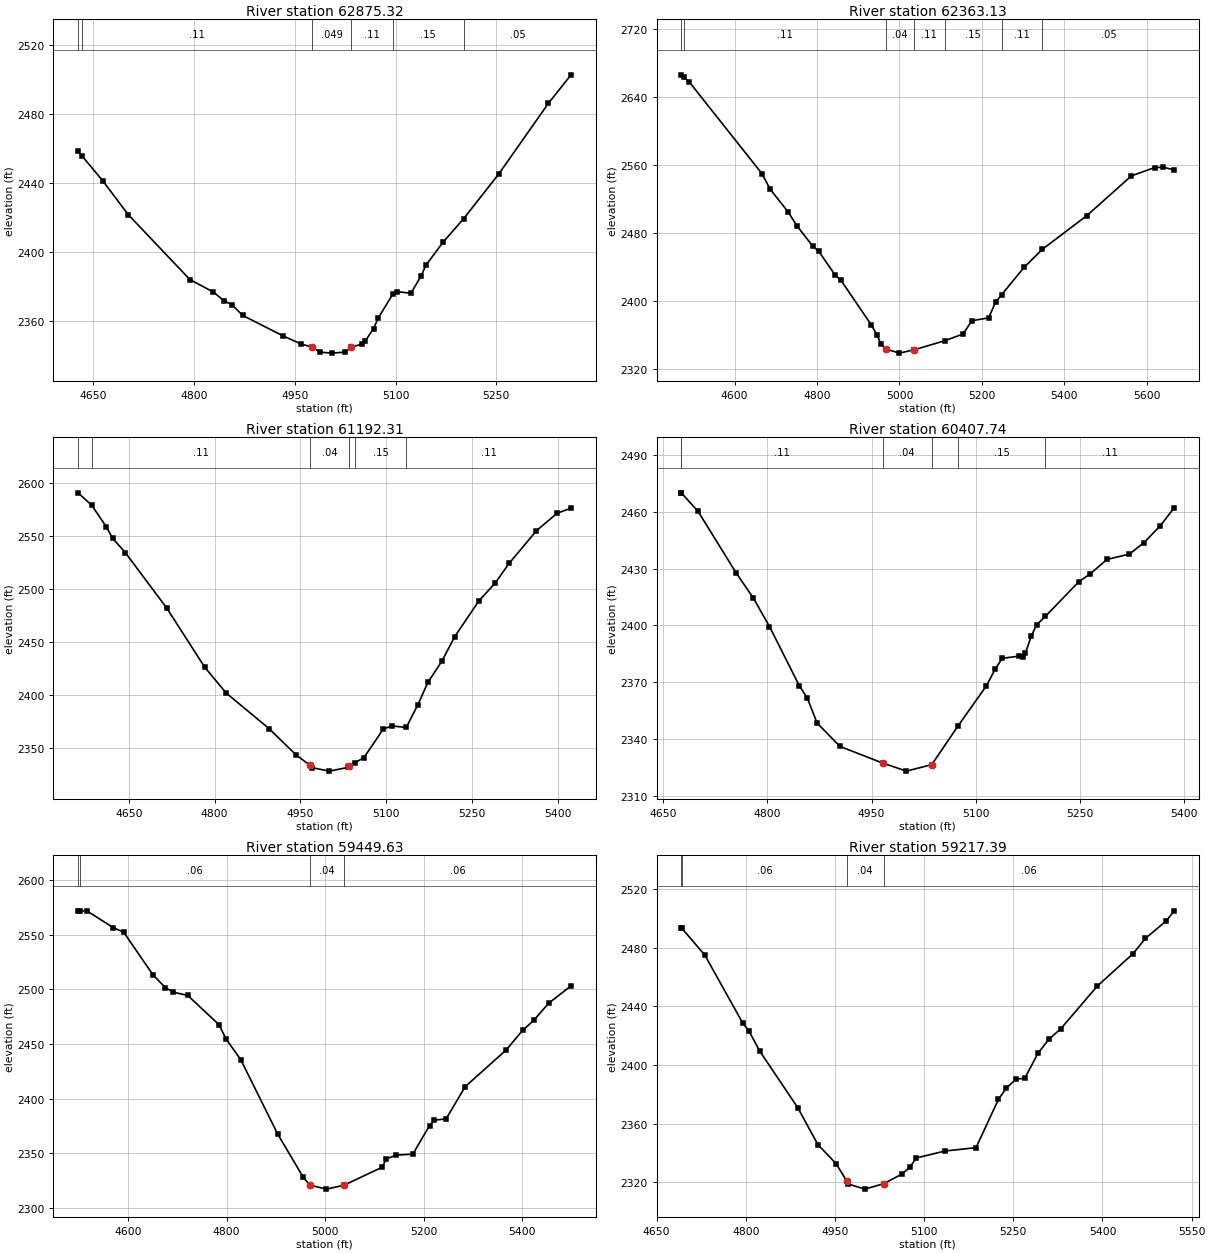
Type RM Length L Ch R = 1 ,62875.32,534.01,512.2,490.38
XS GIS Cut Line= 3
      996179.197      824282.064      996381.065      824711.866
      996485.258      824948.995
#Sta/Elev= 30
 4627.33 2458.46 4633.43 2455.74 4664.13 2441.36 4701.88  2421.8 4793.92 2383.96
  4828.9 2376.73 4844.19 2371.76 4856.45 2369.39 4872.19 2363.21 4933.12 2351.14
 4958.75 2346.69 4975.39 2344.75 4987.92 2341.83 5005.05 2341.26 5024.75 2341.83
 5033.61 2344.73 5049.66 2346.48 5054.44  2348.1 5067.14 2355.52 5074.35 2361.77
 5095.59 2375.38 5101.95 2377.03  5122.7 2376.03 5138.37 2386.32 5144.86 2392.18
 5170.74 2405.75 5201.34 2419.41 5253.45 2445.28 5327.46 2486.41 5361.19 2502.96
#Mann= 6 ,-1 , 0
 4627.33     .11       0 4633.43     .11       0 4975.39    .049       0
 5033.61     .11       0 5095.59     .15       0 5201.34     .05       0
Bank Sta=4975.39,5033.61
Exp/Cntr=0.3,0.1

Type RM Length L Ch R = 1 ,62363.13,1178.68,1170.82,1162.95
XS GIS Cut Line= 2
      995471.145      824730.952      996569.254       825204.15
#Sta/Elev= 30
 4470.82 2666.01 4477.37 2662.98  4490.2 2657.61 4666.52 2549.79 4686.13  2531.7
 4729.77 2504.94 4751.58 2488.35 4789.11 2464.93    4804  2458.7 4843.67 2430.83
 4858.33 2424.36 4931.92 2371.81 4946.02  2359.9 4955.25 2349.11 4966.17 2343.83
 4999.74 2338.88 5035.64 2342.82  5109.6 2353.42 5154.17 2361.35 5175.47 2376.94
 5216.12 2380.33 5232.92 2398.55 5247.62 2407.43  5302.2  2439.7  5346.7 2460.96
 5454.32 2500.47 5562.65 2547.29 5618.67 2556.93 5639.56 2557.46 5666.55 2554.19
#Mann= 7 ,-1 , 0
 4470.82     .11       0 4477.37     .11       0 4966.17     .04       0
 5035.64     .11       0  5109.6     .15       0 5247.62     .11       0
  5346.7     .05       0
Bank Sta=4966.17,5035.64
Exp/Cntr=0.3,0.1

Type RM Length L Ch R = 1 ,61192.31,785.48,784.58,783.68
XS GIS Cut Line= 2
      995405.764      826024.842      996258.243      826149.102
#Sta/Elev= 30
 4561.39 2591.08 4585.37 2579.28  4610.6 2559.21 4621.79  2548.2 4644.02 2534.63
 4716.75 2482.03 4782.37  2426.8 4820.02 2402.29 4894.99 2368.66 4942.54 2343.72
 4966.59 2333.96  4970.3 2331.76 5000.47 2328.48 5033.79 2332.08 5034.35 2333.62
 5045.48 2336.52 5060.95 2341.24 5094.73 2368.16 5109.59 2371.12 5134.84  2369.7
  5154.8 2390.67 5172.72 2412.25 5197.17 2432.27 5219.65 2455.45 5261.68 2489.03
 5290.18 2505.85  5314.7 2524.56 5362.45 2555.33  5398.7 2571.94 5422.88 2576.55
#Mann= 6 ,-1 , 0
 4561.39     .11       0 4585.37     .11       0 4966.59     .04       0
 5034.35     .11       0 5045.48     .15       0 5134.84     .11       0
Bank Sta=4966.59,5034.35
Exp/Cntr=0.3,0.1

Type RM Length L Ch R = 1 ,60407.74,960.52,958.11,955.7
XS GIS Cut Line= 2
      995471.523      826832.519      996175.793      826913.895
#Sta/Elev= 30
 4676.47 2470.05  4676.5 2470.04 4700.61 2460.23  4755.4 2427.68 4780.26  2414.3
  4803.3 2399.35 4846.17 2368.06 4857.82 2361.44 4871.72 2348.35 4904.76 2335.95
 4965.83 2327.22 5000.28 2322.91 5036.66 2326.35 5074.73 2346.95 5115.19 2367.98
 5127.96 2376.88    5138 2382.55 5162.46 2383.73 5167.22 2383.12 5171.33 2385.24
 5179.93 2394.58 5187.86  2400.4 5199.94 2404.69 5248.43 2423.16 5264.48 2427.19
 5288.55 2434.82 5320.93 2437.67 5342.04 2443.78 5365.43 2452.71 5385.43 2462.22
#Mann= 6 ,-1 , 0
 4676.47     .11       0  4676.5     .11       0 4965.83     .04       0
 5036.66     .11       0 5074.73     .15       0 5199.94     .11       0
Bank Sta=4965.83,5036.66
Exp/Cntr=0.3,0.1

Type RM Length L Ch R = 1 ,59449.63,248.54,232.24,215.94
XS GIS Cut Line= 2
      995087.099      827784.458      996086.845      827819.102
#Sta/Elev= 30
 4498.76 2571.58 4501.67 2571.82  4516.4 2571.84 4570.18 2556.48 4591.32  2552.3
 4651.05 2513.14 4675.77  2501.7 4691.88 2497.47 4721.37 2494.43 4784.67 2467.75
 4799.63 2454.21 4828.78 2435.81 4903.98 2367.59  4955.5 2328.31 4968.79 2321.15
 5002.17 2317.34 5038.09 2320.87 5115.57  2337.3  5124.5 2345.03 5143.81 2348.42
 5178.07 2349.37 5211.86 2375.37 5221.67  2380.3 5245.66 2381.68 5284.26 2411.03
 5367.01  2444.4 5400.65 2462.42 5423.24 2471.62 5453.73 2487.39 5499.11 2503.22
#Mann= 4 ,-1 , 0
 4498.76     .06       0 4501.67     .06       0 4968.79     .04       0
 5038.09     .06       0
Bank Sta=4968.79,5038.09
Exp/Cntr=0.3,0.1

Type RM Length L Ch R = 1 ,59217.39,127.47,107.07,86.59
XS GIS Cut Line= 5
      995327.137      828135.853      995549.853      828066.564
      995705.754      827979.952      995770.094      827945.308
      996101.693      827851.272
#Sta/Elev= 30
 4691.46 2493.69 4692.47 2493.19 4730.87 2475.08 4795.07 2428.48 4805.19  2423.3
 4823.07 2409.74 4887.19 2371.09 4921.32 2345.77 4952.16 2332.67  4969.9  2320.9
 4972.53 2318.92 5000.22 2315.46 5032.11  2319.2 5062.69 2325.74 5075.98 2330.37
 5086.69 2336.66 5134.62 2341.41 5187.25 2343.71 5225.06 2376.69 5238.49 2384.46
 5254.91 2390.53  5269.2 2390.91 5291.29 2407.92 5309.63 2417.56 5329.59 2424.62
 5391.23 2453.84 5451.23 2475.89 5472.25 2486.35 5507.09 2498.23  5520.8 2505.15
#Mann= 4 ,-1 , 0
 4691.46     .06       0 4692.47     .06       0  4969.9     .04       0
 5032.11     .06       0
Bank Sta=4969.9,5032.11
Exp/Cntr=0.5,0.3

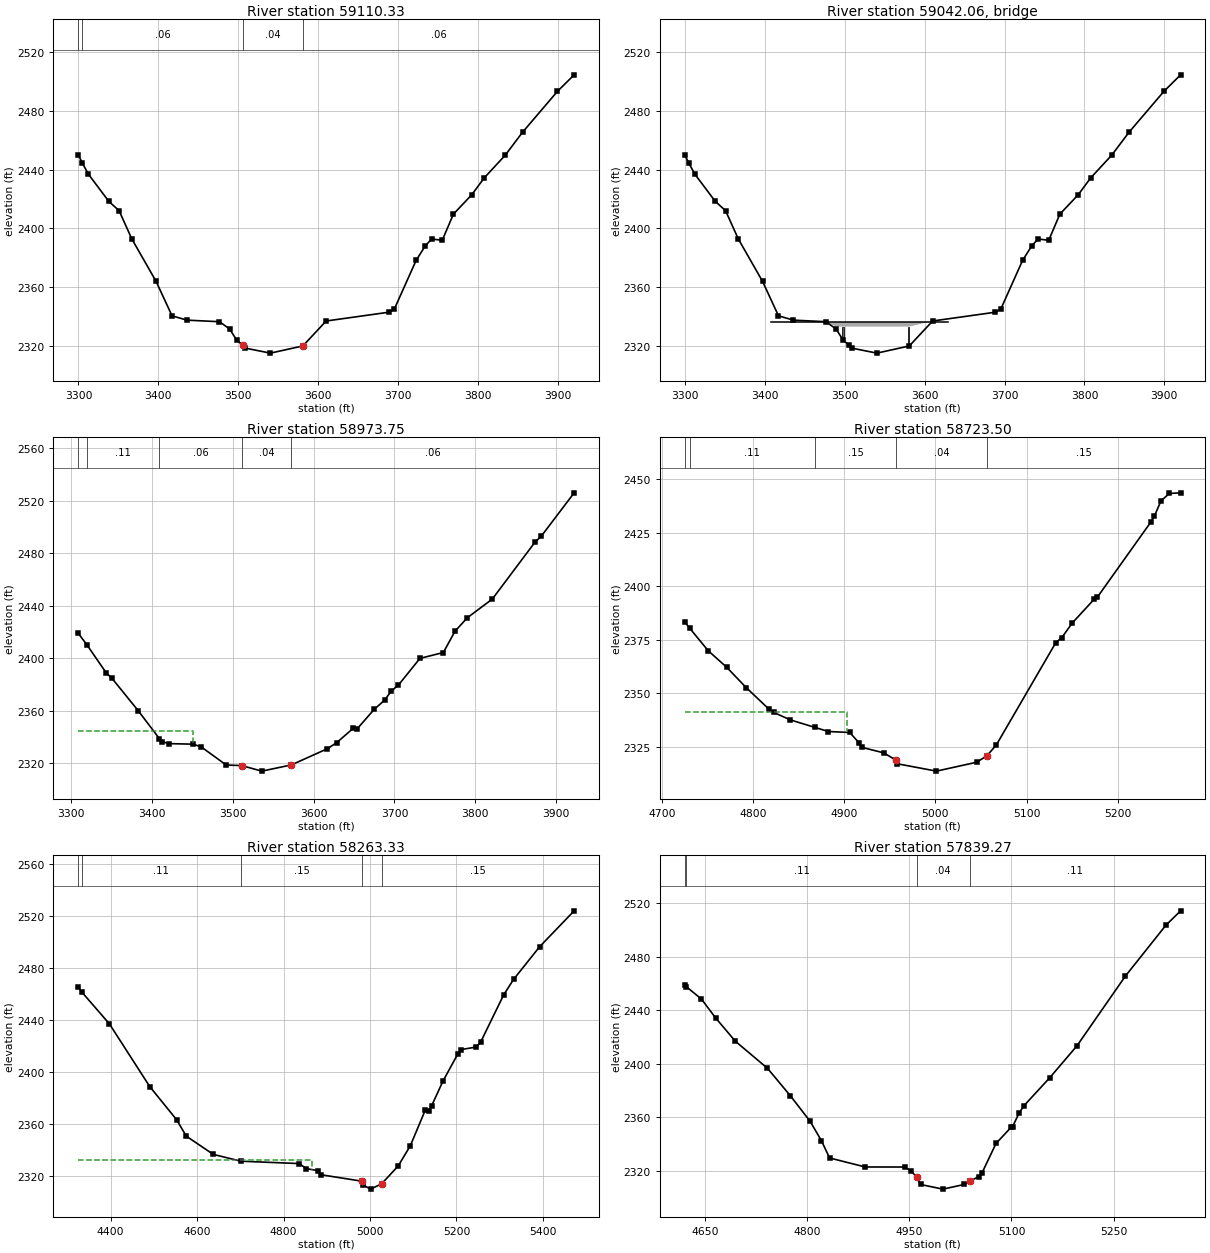
Type RM Length L Ch R = 1 ,59110.33,137.56,136.58,135.67
XS GIS Cut Line= 4
      995431.071      828361.044      995574.599      828274.432
      995745.348      827967.579      996091.794      827873.544
#Sta/Elev= 30
3299.699 2450.133304.635  2444.73312.336 2436.983337.855 2418.473350.887 2412.01
3366.733 2392.863397.238 2363.83  3417.1 2340.443435.803  2337.53476.519 2336.43
3489.091 2331.513498.191 2323.773505.864 2320.343508.706 2318.463540.229 2315.04
3580.817 2319.92 3610.02 2336.923688.212 2342.883695.184 2344.85 3722.62  2378.2
3733.757 2387.833741.931 2392.783755.302 2391.863769.219 2409.653792.291 2422.93
3807.812 2434.35 3834.11 2449.813855.825 2465.47 3899.51 2493.313920.384 2504.55
#Mann= 4 ,-1 , 0
3299.699     .06       03304.635     .06       03505.864     .04       0
3580.817     .06       0
Bank Sta=3505.864,3580.817
Skew Angle= 45
Exp/Cntr=0.5,0.3

Type RM Length L Ch R = 3 ,59042.06,,,
BEGIN DESCRIPTION:
US-19W
END DESCRIPTION:
Bridge Culvert--1,0,-1,-1, 0
Deck Dist Width WeirC Skew NumUp NumDn MinLoCord MaxHiCord MaxSubmerge Is_Ogee
50.8,35,2.6,45, 6, 6, , , 0.95, 0, 0,0,,
3408.2553450.6813450.6813620.3873620.3873628.872
  2336.1  2336.1  2336.1  2336.1  2336.1  2336.1
                  2333.1  2333.1
3408.2553450.6813450.6813620.3873620.3873628.872
  2336.1  2336.1  2336.1  2336.1  2336.1  2336.1
                  2333.1  2333.1
Pier Skew, UpSta & Num, DnSta & Num=  ,3498, 2 ,3498, 2 , 0 , 0 , 0 ,,
       2       2
       0  2333.1
       2       2
       0  2333.1
Pier Skew, UpSta & Num, DnSta & Num=  ,3580, 2 ,3580, 2 , 0 , 0 , 0 ,,
       2       2
       0  2333.1
       2       2
       0  2333.1
BR Coef=-1 , 1 , 1 ,0.9, 0 ,,,0.8,0,1.2,0,
WSPro=,,,, 1 ,,,, 0 ,,,, 0 ,,,,-1 ,-1 ,-1 , 0 , 0 , 0 , 0 , 0
BC Design=,, 0 ,, 0 ,,,,,,

Type RM Length L Ch R = 1 ,58973.75,218.42,250.24,282.07
XS GIS Cut Line= 5
       995468.19      828447.655      995624.091      828390.739
      995799.789       828091.31      995876.502      828024.496
      996119.015      827955.206
#Sta/Elev= 30
3308.991 2418.973319.534 2410.353343.887 2388.593350.632 2384.733383.188 2359.96
3409.478  2338.63412.123 2336.513421.131  2334.93451.353 2334.48 3461.33 2332.29
3492.061 2318.573510.919 2318.193536.029 2313.953572.509 2318.683617.148 2331.06
3628.575 2335.653649.067 2346.633654.002 2346.283675.173 2361.193687.852 2368.04
3695.969 2374.963704.851 2379.483731.452 2399.843760.436 2404.313774.769 2420.49
3790.099 2430.823820.929 2445.03 3873.58 2488.283881.394 2492.873922.109 2525.96
#Mann= 5 ,-1 , 0
3308.991     .11       03319.534     .11       03409.478     .06       0
3510.919     .04       03572.509     .06       0
#XS Ineff= 2 , 0
         3451.24 2344.29
Permanent Ineff=
       F       F
Bank Sta=3510.919,3572.509
Skew Angle= 45
Exp/Cntr=0.5,0.3

Type RM Length L Ch R = 1 ,58723.50,457.68,460.17,462.67
XS GIS Cut Line= 2
      995478.089       828546.64      996015.081      828460.028
#Sta/Elev= 30
 4725.04 2383.39 4730.76 2380.32 4750.85 2369.93 4771.12 2362.22 4792.41 2352.78
 4817.52 2342.67 4822.65 2341.16 4841.06 2337.67  4867.7  2334.2 4882.74 2332.26
 4906.02 2331.82 4916.38 2326.94 4919.04 2324.91 4943.33 2322.31 4957.19 2318.82
 4957.74 2317.26 5001.15 2313.79 5045.21 2317.93 5056.39 2320.89 5066.88 2326.02
 5132.06  2373.7 5138.69 2376.07 5150.14 2382.87 5174.16 2393.95 5177.78 2394.99
 5236.16 2429.85 5240.27 2432.79 5247.34 2439.75 5256.47 2443.26 5268.97 2443.57
#Mann= 5 ,-1 , 0
 4725.04     .11       0 4730.76     .11       0  4867.7     .15       0
 4957.19     .04       0 5056.39     .15       0
#XS Ineff= 2 , 0
         4903.44 2341.32
Permanent Ineff=
       F       F
Bank Sta=4957.19,5056.39
Exp/Cntr=0.3,0.1

Type RM Length L Ch R = 1 ,58263.33,412,424.06,436.12
XS GIS Cut Line= 4
      995168.762      828992.071      995687.971      828963.677
      995963.114      828942.579      996312.035      828982.173
#Sta/Elev= 30
 4325.12 2464.81 4333.35 2461.19 4397.28 2436.67 4490.53 2388.45  4552.9 2362.85
 4574.98 2350.34 4637.42 2336.27  4701.5 2331.03  4836.3  2329.2 4852.81 2325.29
 4878.85 2323.83 4887.22 2320.57 4981.85 2315.62 4983.65 2312.75 5001.68 2309.54
 5027.23 2313.74 5065.24 2327.36 5093.41 2342.99 5127.76 2370.26 5136.24 2370.02
 5142.43 2373.54 5168.45 2392.41  5202.6 2413.22 5210.84  2416.9 5245.06 2418.82
 5255.61 2422.44 5309.09 2458.92 5332.04 2470.86 5392.55 2496.08 5472.22 2523.64
#Mann= 5 ,-1 , 0
 4325.12     .11       0 4333.35     .11       0  4701.5     .15       0
 4981.85     .04       0 5027.23     .15       0
#XS Ineff= 2 , 0
         4865.66 2331.63
Permanent Ineff=
       F       F
#Block Obstruct= 2 , 0
         4835.49 2329.66
Bank Sta=4981.85,5027.23
Exp/Cntr=0.3,0.1

Type RM Length L Ch R = 1 ,57839.27,629.41,590.64,551.87
XS GIS Cut Line= 2
      995334.561      829219.736      996024.979       829452.35
#Sta/Elev= 30
 4619.92 2458.62  4622.3 2457.69 4644.45 2448.52 4665.29 2434.42 4694.31 2416.96
 4741.56 2396.72 4774.89 2376.37 4804.21  2357.1  4820.8  2342.6 4832.81 2329.71
 4885.16 2322.98 4943.16 2322.95  4952.3 2320.15 4960.83 2315.34 4966.42 2309.89
 4999.29 2306.43  5030.7 2309.92  5038.6 2312.27 5051.87 2315.79 5056.91 2318.76
  5077.3 2340.55 5099.99 2352.93 5101.53 2352.96 5111.27 2363.46 5118.58  2368.9
 5156.14 2389.62 5196.06 2413.42 5267.31 2465.61 5326.75 2503.57 5348.47 2514.39
#Mann= 4 ,-1 , 0
 4619.92     .11       0  4622.3     .11       0 4960.83     .04       0
  5038.6     .11       0
Bank Sta=4960.83,5038.6
Exp/Cntr=0.3,0.1