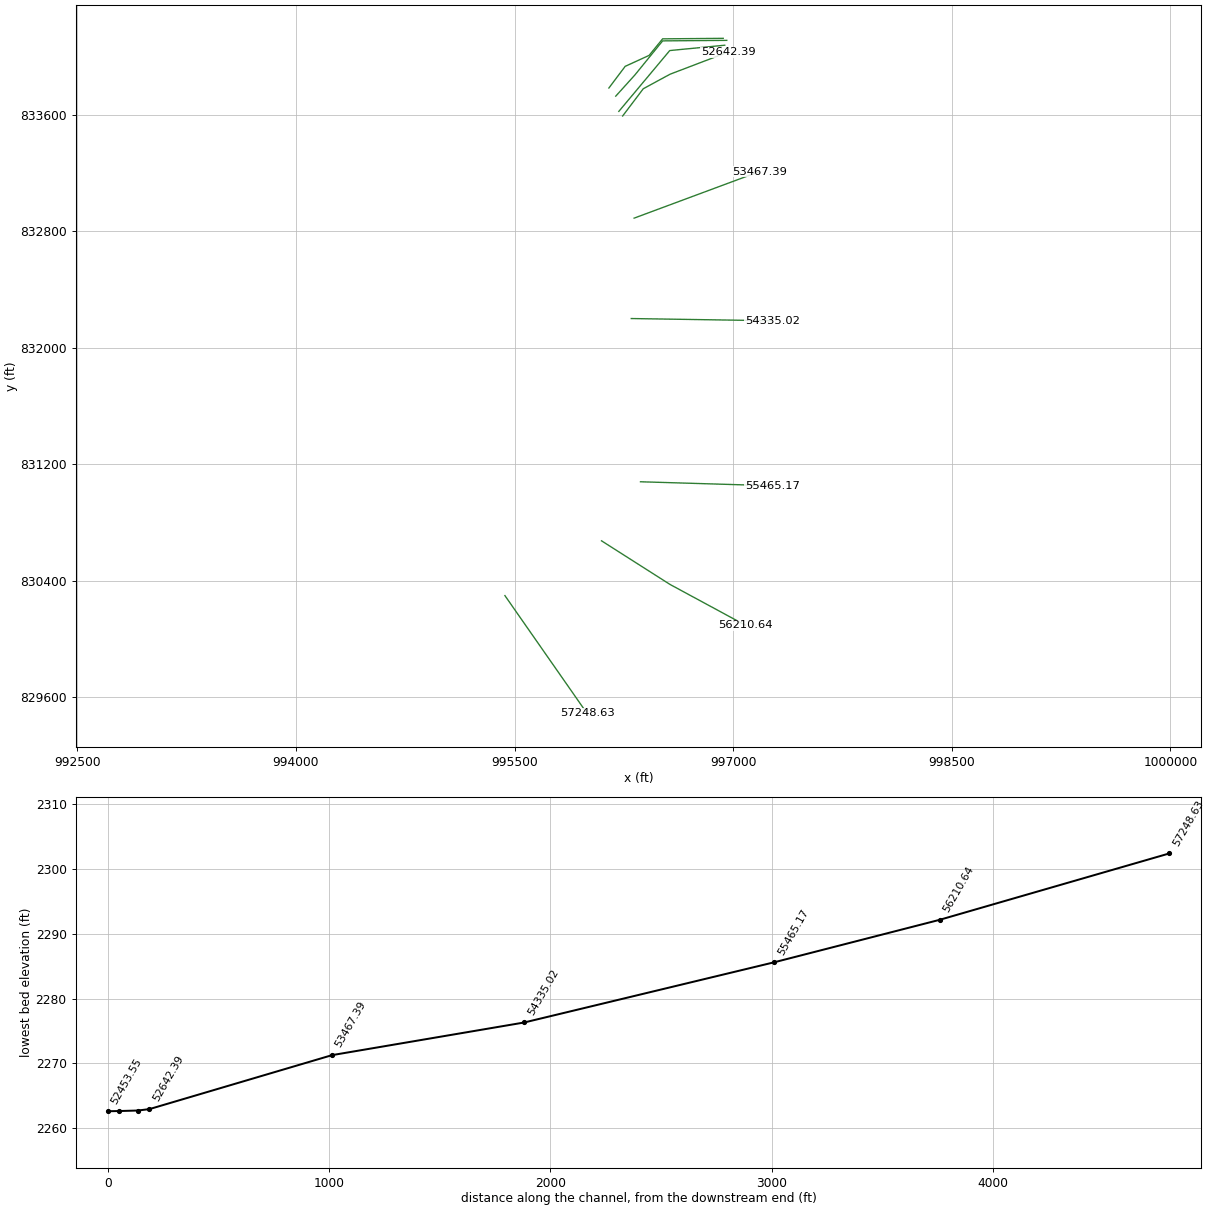
HEC-RAS study lds_cane_rvr_downstream.prj: Cane River Downstream LDS

--- lds_cane_rvr_downstream.g01 (geometry) --- (continued)

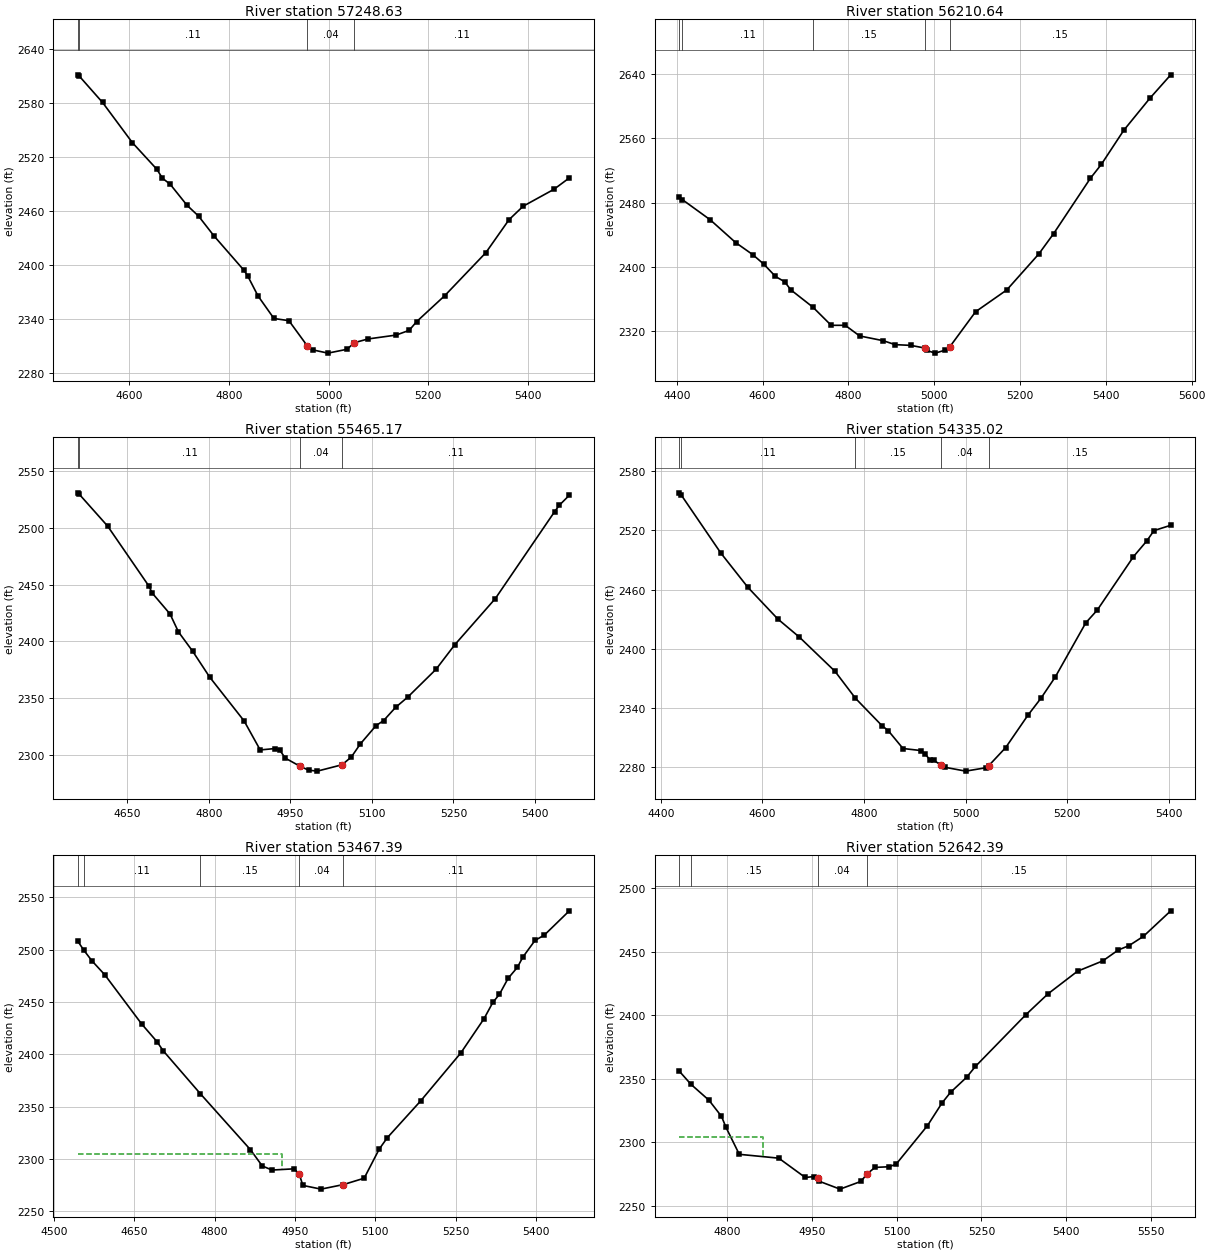
Type RM Length L Ch R = 1 ,57248.63,1023.96,1037.99,1052.02
XS GIS Cut Line= 2
      995433.691      830298.982      995997.386      829490.793
#Sta/Elev= 30
 4497.58 2611.31  4499.2 2610.49 4546.91  2580.6 4606.68    2536 4655.55 2506.57
 4667.05  2496.5 4682.56 2489.79 4716.28 2466.48 4739.38 2454.49 4770.17 2432.59
 4829.76 2394.77 4837.59 2388.44 4858.53 2365.94 4890.57 2340.82 4920.58 2338.39
 4956.89 2310.84 4968.28 2306.01 4998.81 2302.38 5037.22 2306.65  5051.7 2313.93
 5079.01 2318.09 5135.59 2322.42 5161.79 2327.68 5176.58 2337.28 5233.07 2366.15
 5315.46 2413.84 5362.01  2450.5 5390.23 2465.42    5452 2484.21 5482.93 2496.89
#Mann= 4 ,-1 , 0
 4497.58     .11       0  4499.2     .11       0 4956.89     .04       0
  5051.7     .11       0
Bank Sta=4956.89,5051.7
Exp/Cntr=0.3,0.1

Type RM Length L Ch R = 1 ,56210.64,731.5,745.47,759.44
XS GIS Cut Line= 3
      996096.743      830674.811      996566.921      830375.383
      997084.116      830095.751
#Sta/Elev= 30
 4405.84 2487.26 4413.03 2483.56 4477.72 2458.49 4536.94 2430.11 4577.01 2414.97
 4603.04 2402.95 4629.83 2387.79 4651.29 2381.16 4665.56  2371.1 4717.22 2349.43
 4759.66 2326.85 4792.47 2326.83 4825.97 2313.59 4881.18 2307.63 4908.67 2302.74
 4945.51  2301.8 4979.04 2298.37 4981.92 2295.57 5002.04 2292.14 5024.13 2295.67
 5036.49 2300.25 5096.25 2343.76 5168.97 2370.97 5243.58 2415.83 5277.94 2441.04
  5363.9 2510.29 5389.49 2527.69 5441.63 2570.14  5502.3 2609.98 5551.22 2639.41
#Mann= 5 ,-1 , 0
 4405.84     .11       0 4413.03     .11       0 4717.22     .15       0
 4979.04     .04       0 5036.49     .15       0
Bank Sta=4979.04,5036.49
Exp/Cntr=0.3,0.1

Type RM Length L Ch R = 1 ,55465.17,1129.72,1130.15,1130.59
XS GIS Cut Line= 2
      996364.127      831080.005      997267.397      831052.839
#Sta/Elev= 30
 4559.56 2530.94 4562.13 2529.56 4614.12 2501.59 4689.41 2449.12 4696.48 2442.34
 4728.88 2424.12  4744.3 2408.38 4770.55 2391.24 4801.86 2368.44 4865.08 2329.87
 4894.68 2304.29 4921.33 2305.49  4930.4  2304.2 4941.03 2297.02 4967.92 2289.91
 4983.71 2286.46 4999.72 2285.61 5045.19 2291.21 5062.38 2298.09 5078.79 2309.54
 5107.84 2325.79 5121.55 2330.11 5143.72  2341.8 5166.26 2350.96 5218.12  2375.4
  5252.8 2397.15  5327.1 2437.69 5436.05 2514.25 5444.84 2520.01 5463.24 2528.82
#Mann= 4 ,-1 , 0
 4559.56     .11       0 4562.13     .11       0 4967.92     .04       0
 5045.19     .11       0
Bank Sta=4967.92,5045.19
Exp/Cntr=0.3,0.1

Type RM Length L Ch R = 1 ,54335.02,856.48,867.62,878.78
XS GIS Cut Line= 2
      996300.682      832200.097      997267.364      832184.873
#Sta/Elev= 30
 4436.59  2558.1 4439.82  2556.2  4518.3 2497.01 4571.36 2462.41 4630.25 2430.35
 4672.86 2411.92 4742.86 2377.32 4783.06 2350.05 4835.33  2322.3 4847.56 2317.28
 4876.53 2299.23 4911.04  2297.2 4920.22 2293.77 4929.32 2287.73 4937.78 2287.09
 4950.61 2282.63 4958.26 2280.29 4999.84 2276.32 5039.98 2279.77 5045.41  2281.9
 5078.63 2300.17 5122.27 2332.86 5148.18 2350.22 5176.17 2371.62 5236.28  2426.5
 5258.81 2439.38 5330.11 2493.54 5355.81 2509.11 5370.49 2519.88 5403.39 2525.22
#Mann= 5 ,-1 , 0
 4436.59     .11       0 4439.82     .11       0 4783.06     .15       0
 4950.61     .04       0 5045.41     .15       0
Bank Sta=4950.61,5045.41
Exp/Cntr=0.3,0.1

Type RM Length L Ch R = 1 ,53467.39,820.74,825,829.25
XS GIS Cut Line= 2
       996320.39      832888.994      997180.356       833208.41
#Sta/Elev= 30
 4544.96 2507.85 4556.08 2499.38 4570.81 2489.51 4594.95 2476.07 4663.95 2428.99
 4692.27 2412.27  4704.1 2403.44 4773.54 2362.36 4866.87 2309.01 4888.99 2293.44
 4907.13 2289.51 4948.46 2290.68 4958.04 2285.71  4964.8 2274.84 4998.77 2271.29
 5040.57 2275.64 5079.29 2281.72 5107.42 2309.57 5122.58 2320.46 5184.61 2355.46
 5259.94 2401.53 5303.19  2434.2 5319.47 2449.59  5331.8 2457.38 5348.08 2472.69
 5365.26 2483.08 5375.65    2493 5398.22 2508.86  5415.7 2513.99 5462.33 2537.15
#Mann= 5 ,-1 , 0
 4544.96     .11       0 4556.08     .11       0 4773.54     .15       0
 4958.04     .04       0 5040.57     .11       0
#XS Ineff= 2 , 0
         4926.09 2304.41
Permanent Ineff=
       F       F
Bank Sta=4958.04,5040.57
Exp/Cntr=0.3,0.1

Type RM Length L Ch R = 1 ,52642.39,39.84,52.01,64.17
XS GIS Cut Line= 4
      996241.601      833589.853      996383.127      833776.806
      996566.586      833876.399      996964.955      834028.408
#Sta/Elev= 30
 4715.53 2355.86 4736.25 2345.48 4767.96 2333.01 4790.02 2320.34 4797.96  2311.7
 4821.51 2290.41 4891.42 2287.37 4938.29 2272.14 4953.08 2272.86 4960.21 2271.65
 4962.55 2269.25 4999.84 2262.97 5037.07  2269.1 5047.22  2274.8 5061.74 2280.09
 5086.17  2280.6 5098.91 2282.53 5154.62 2313.04  5180.3 2330.86 5195.45 2339.29
 5223.76 2351.08 5239.36 2359.64 5328.85 2400.52 5368.01 2416.95 5420.13 2434.74
 5464.79 2442.86 5492.56 2451.55 5510.83 2454.79 5536.73 2462.21 5585.14 2482.35
#Mann= 4 ,-1 , 0
 4715.53     .15       0 4736.25     .15       0 4960.21     .04       0
 5047.22     .15       0
#XS Ineff= 2 , 0
         4863.58 2303.77
Permanent Ineff=
       F       F
Bank Sta=4960.21,5047.22
Exp/Cntr=0.5,0.3

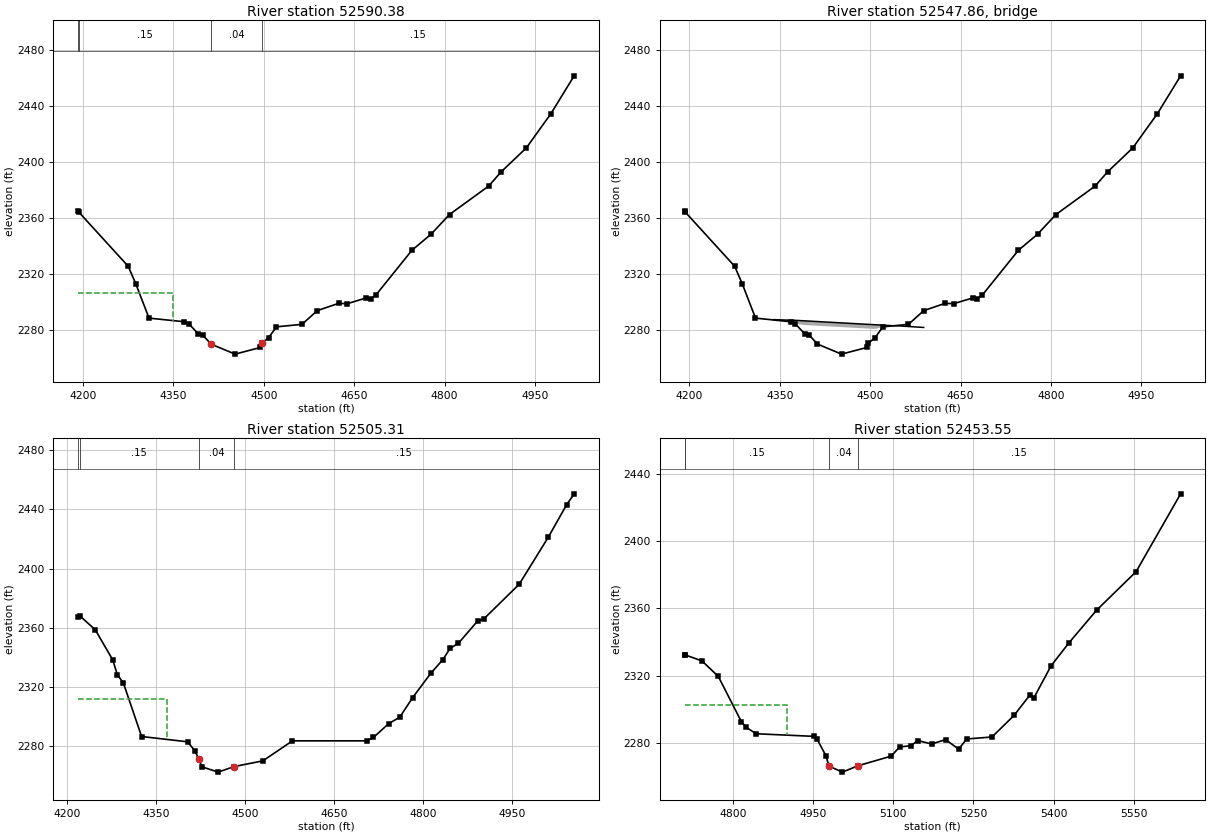
Type RM Length L Ch R = 1 ,52590.38,84.1,85.07,86.05
XS GIS Cut Line= 3
      996215.392      833621.303      996564.839      834038.891
      996942.241      834075.583
#Sta/Elev= 30
4192.043 2364.754193.273 2364.08 4274.96 2325.514287.452 2313.154309.558 2288.47
4368.418 2285.864375.519 2284.414391.522 2277.174398.365 2276.534412.416 2269.91
4452.342 2262.754494.451 2267.514496.918 2270.524508.012 2274.514521.056 2282.25
4563.388 2284.034588.755 2293.814624.502 2299.074638.197 2298.74 4669.89 2302.87
4677.205 2302.234685.607 2304.73 4745.75 2336.884777.613  2348.44808.201 2362.48
4873.102 2382.76 4894.05 2393.014935.722 2410.054976.619 2434.585015.057 2461.53
#Mann= 4 ,-1 , 0
4192.043     .15       04193.273     .15       04412.416     .04       0
4496.918     .15       0
#XS Ineff= 2 , 0
        4349.288 2306.584570.498         2280.99
Permanent Ineff=
       F       F
#Block Obstruct= 2 , 0
                        4570.498         2280.99
Bank Sta=4412.416,4496.918
Skew Angle= 27
Exp/Cntr=0.5,0.3

Type RM Length L Ch R = 3 ,52547.86,,,
BEGIN DESCRIPTION:
US-19W
END DESCRIPTION:
Bridge Culvert--1,0,-1,-1, 0
Deck Dist Width WeirC Skew NumUp NumDn MinLoCord MaxHiCord MaxSubmerge Is_Ogee
25.5,34,2.6,27, 8, 9, , , 0.95, 0, 0,0,,
4339.2024365.9324371.2784371.2784538.7874538.7874544.1334588.684
  2287.4    2287    2287    2287    2283    2283    2283  2281.8
                       0    2284    2280
4325.8374339.2024365.9324380.1884380.1884547.6974547.6974553.0434597.594
    2287  2287.4    2287    2287    2287    2283    2283    2283  2281.8
                               0    2284    2280
BR Coef=-1 , 0 , 0 ,, 0 ,,,0.8,0,,0,
WSPro=,,,, 1 ,,,, 0 ,,,, 0 ,,,,-1 ,-1 ,-1 , 0 , 0 , 0 , 0 , 0
BC Design=,, 0 ,, 0 ,,,,,,

Type RM Length L Ch R = 1 ,52505.31,66.82,51.77,36.72
XS GIS Cut Line= 4
      996194.426      833726.137      996325.468      833871.157
      996515.916      834105.286      996956.219      834108.781
#Sta/Elev= 30
 4219.21 2367.124221.553  2368.3  4247.9 2358.774277.303 2338.494285.162 2328.44
4295.346 2322.794325.979 2286.714403.515 2283.144415.347 2277.244422.618 2271.48
4427.438 2266.274455.006 2262.67 4481.54  2266.44530.251 2270.27 4580.13 2283.79
4705.183 2283.794716.587 2286.09 4742.24 2295.434760.915 2299.774782.549 2312.99
4813.012 2329.354833.497  2338.64845.525 2346.164859.683 2349.674891.795 2364.58
4902.086 2365.954962.051 2389.515010.967  2421.25042.001 2443.23  5054.6 2450.54
#Mann= 4 ,-1 , 0
 4219.21     .15       04221.553     .15       04422.618     .04       0
 4481.54     .15       0
#XS Ineff= 2 , 0
        4369.122  2312.24570.142         2281.05
Permanent Ineff=
       F       F
#Block Obstruct= 2 , 0
                         4581.46         2299.67
Bank Sta=4422.618,4481.54
Skew Angle= 27
Exp/Cntr=0.5,0.3

Type RM Length L Ch R = 1 ,52453.55,37.93,24.08,10.23
XS GIS Cut Line= 5
       996147.25      833782.048      996259.073      833930.563
      996423.313      834005.694      996515.916      834119.264
      996931.758      834122.758
#Sta/Elev= 30
 4709.17 2332.24 4709.89 2332.36 4741.62 2328.73 4772.08 2319.56 4815.39 2292.62
 4824.42 2289.25 4843.08 2285.45 4950.48 2283.91 4957.21 2282.19 4973.67 2272.42
 4979.34 2266.21 5004.75 2262.64 5033.34 2266.39 5096.13 2272.16 5111.67 2277.58
  5133.3 2278.37 5145.45 2281.42  5171.8 2279.35 5197.87 2281.98 5222.22 2276.32
 5237.43 2282.35 5284.78 2283.53 5326.07 2296.34 5355.21 2308.23 5363.37 2306.87
  5395.5 2325.87 5429.28 2339.64 5480.84 2358.95 5554.64 2381.78 5638.08 2428.07
#Mann= 4 ,-1 , 0
 4709.17     .15       0 4709.89     .15       0 4979.34     .04       0
 5033.34     .15       0
#XS Ineff= 2 , 0
          4900.4 2302.76
Permanent Ineff=
       F       F
#Block Obstruct= 2 , 0
                         5118.15         2300.23
Bank Sta=4979.34,5033.34
Exp/Cntr=0.3,0.1
Stream Node=Cane River      ,Downstream      , 0 , 0 ,Upstream end
Stream Node=Cane River      ,Downstream      , 0 , 1 ,Downstream end

Chan Stop Cuts=-1
Use User Specified Reach Order=0
User Specified Reach Order=Cane River      ,Downstream