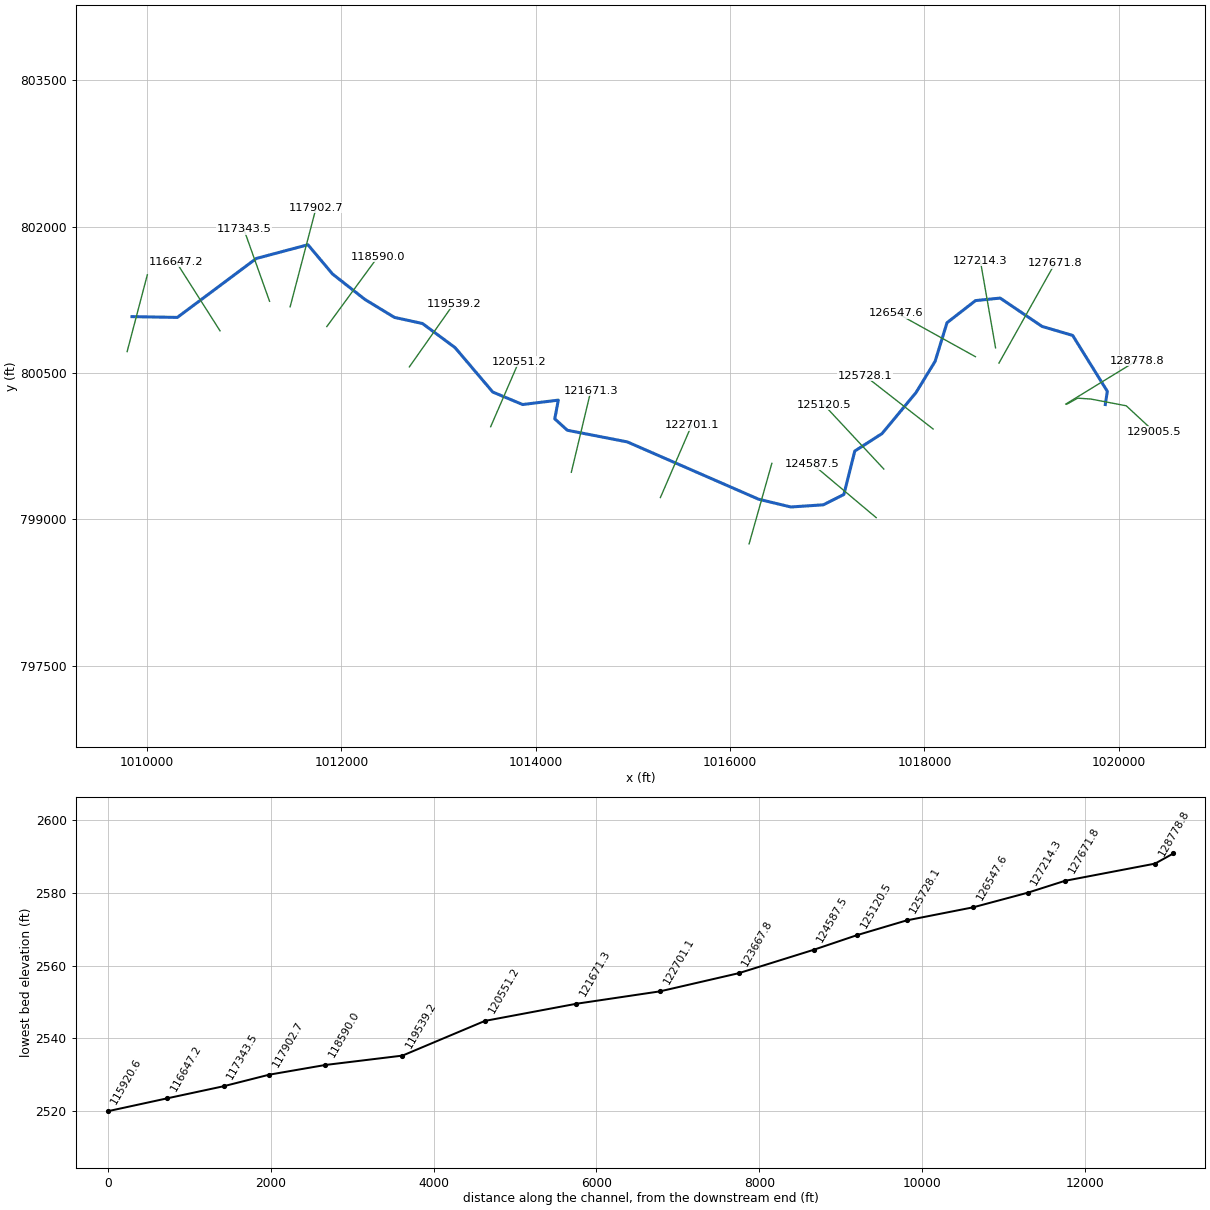
--- lds_cane_rvr_mid.prj (project) ---

Proj Title=Cane River - Midstream LDS
Current Plan=p01
Default Exp/Contr=0.3,0.1
English Units
Geom File=g01
Flow File=f01
Plan File=p01
Y Axis Title=Elevation
X Axis Title(PF)=Main Channel Distance
X Axis Title(XS)=Station
BEGIN DESCRIPTION:
END DESCRIPTION:
DSS File=dss
DSS Export Rating Curves= 0
DSS Export Rating Curve Sorted= 0
DSS Export Volume Flow Curves= 0
DXF OffsetX= 0
DXF OffsetY= 0
DXF ScaleX= 1
DXF ScaleY= 10

--- lds_cane_rvr_mid.p01 (plan) ---

Plan Title=Floodway Plan
Program Version=3.13
Short Identifier=Floodway Pla
Geom File=g01
Flow File=f01
Subcritical Flow
K Sum by GR= 0
Std Step Tol= 0.01
Critical Tol= 0.01
Num of Std Step Trials= 20
Max Error Tol= 0.3
Flow Tol Ratio= 0.001
Split Flow NTrial= 30
Split Flow Tol= 0.02
Split Flow Ratio= 0.02
Log Output Level= 0
Friction Slope Method= 1
Unsteady Friction Slope Method= 2
Unsteady Bridges Friction Slope Method= 1
Parabolic Critical Depth
Global Vel Dist= 0 , 0 , 0
Global Log Level= 0
CheckData=True
Encroach Param=-1 ,10,10, 2
Encroach River=Cane River
Encroach Reach=Midstream
Encroach Node=129005.5
       1    4889    5074
Encroach Node=128778.8
       1    4934    5119
Encroach Node=127671.8
       1    4944    5109
Encroach Node=127214.3
       1  4912.8  5070.3
Encroach Node=126547.6
       1  4914.1  5051.6
Encroach Node=125728.1
       1 4929.55    5095
Encroach Node=125120.5
       1  4939.8  5059.9
Encroach Node=124587.5
       1    4956    5054
Encroach Node=123667.8
       1    4950    5046
Encroach Node=122701.1
       1 4950.41  5067.9
Encroach Node=121671.3
       1    4947    5056
Encroach Node=120551.2
       1  4964.5  5080.7
Encroach Node=119539.2
       1 4936.38 5060.85
Encroach Node=118590.0
       1 4926.98 5053.61
Encroach Node=117902.7
       1    4900 5034.44
Encroach Node=117343.5
       1 4933.44 5053.95
Encroach Node=116647.2
       1 4950.23 5053.24
Encroach Node=115920.6
       1    4947    5047
Computation Interval=1HOUR
Output Interval=1HOUR
Run HTab= 0
Run UNet= 0
Run PostProcess= 0
UNET Theta= 1
UNET Theta Warmup= 1
UNET ZTol= 0.02
UNET ZSATol= 0.05
UNET MxIter= 20
UNET MaxInSteps= 0
UNET DtIC= 0
UNET DtMin= 0
UNET MaxCRTS= 20
UNET WFStab= 2
UNET SFStab= 1
UNET WFX= 1
UNET SFX= 1
UNET DSS MLevel= 4
UNET DZMax Abort= 100
UNET Convert EG Bridges=-1
UNET Use Existing IB Tables=-1
UNET Froude Reduction=False
UNET Froude Limit= 1
UNET Froude Power= 10
Instantaneous Interval=1HOUR
DSS File=dss
Write IC File= 0
Echo Input=False
Echo Output=False
Write Detailed= 0
Detailed Automatic Start=False, 10

--- lds_cane_rvr_mid.f01 (steady flow) ---

Flow Title=Floodway Flows
Program Version=3.13
Number of Profiles= 2
Profile Names=1%,Floodway
River Rch & RM=Cane River,Midstream       ,129005.5
   11550   11550
River Rch & RM=Cane River,Midstream       ,128778.8
   12550   12550
River Rch & RM=Cane River,Midstream       ,126547.6
   12670   12670
River Rch & RM=Cane River,Midstream       ,119539.2
   13300   13300
Boundary for River Rch & Prof#=Cane River,Midstream       , 1
Up Type= 0
Dn Type= 1
Dn Known WS=2537.94
Boundary for River Rch & Prof#=Cane River,Midstream       , 2
Up Type= 0
Dn Type= 1
Dn Known WS=2538.04
Set Internal Change=Cane River      ,Midstream       ,129005.5, 2 , 3 ,2605.54
Set Internal Change=Cane River      ,Midstream       ,129005.5, 1 , 3 ,2605.44
DSS Import GetInterval= 0
DSS Import GetPeak= 0
DSS Import FillOption= 0

--- lds_cane_rvr_mid.g01 (geometry) ---

Geom Title=Cane River Mid Geom
Program Version=3.13

River Reach=Cane River      ,Midstream
Reach XY= 30
     1019860.991      800175.455     1019881.824      800310.872
     1019525.059      800883.791      1019209.95       800976.24
      1018778.96        801266.6     1018525.056      801240.559
     1018232.088      801013.997     1018109.691      800618.162
     1017913.078      800297.847      1017563.88       799877.94
     1017283.362      799698.613      1017170.67       799253.57
      1016959.25       799147.45      1016624.43       799125.24
      1016292.92       799205.04     1014942.158      799792.391
      1014325.18       799911.68      1014195.79      800028.939
      1014232.41       800220.54      1013865.12       800175.43
     1013557.811      800303.339      1013169.34       800759.21
      1012834.32        801005.9      1012546.56        801068.4
     1012243.169       801251.99      1011908.53       801513.71
      1011655.93       801813.19     1011124.679       801672.57
      1010312.18        801068.4      1009845.52       801076.42

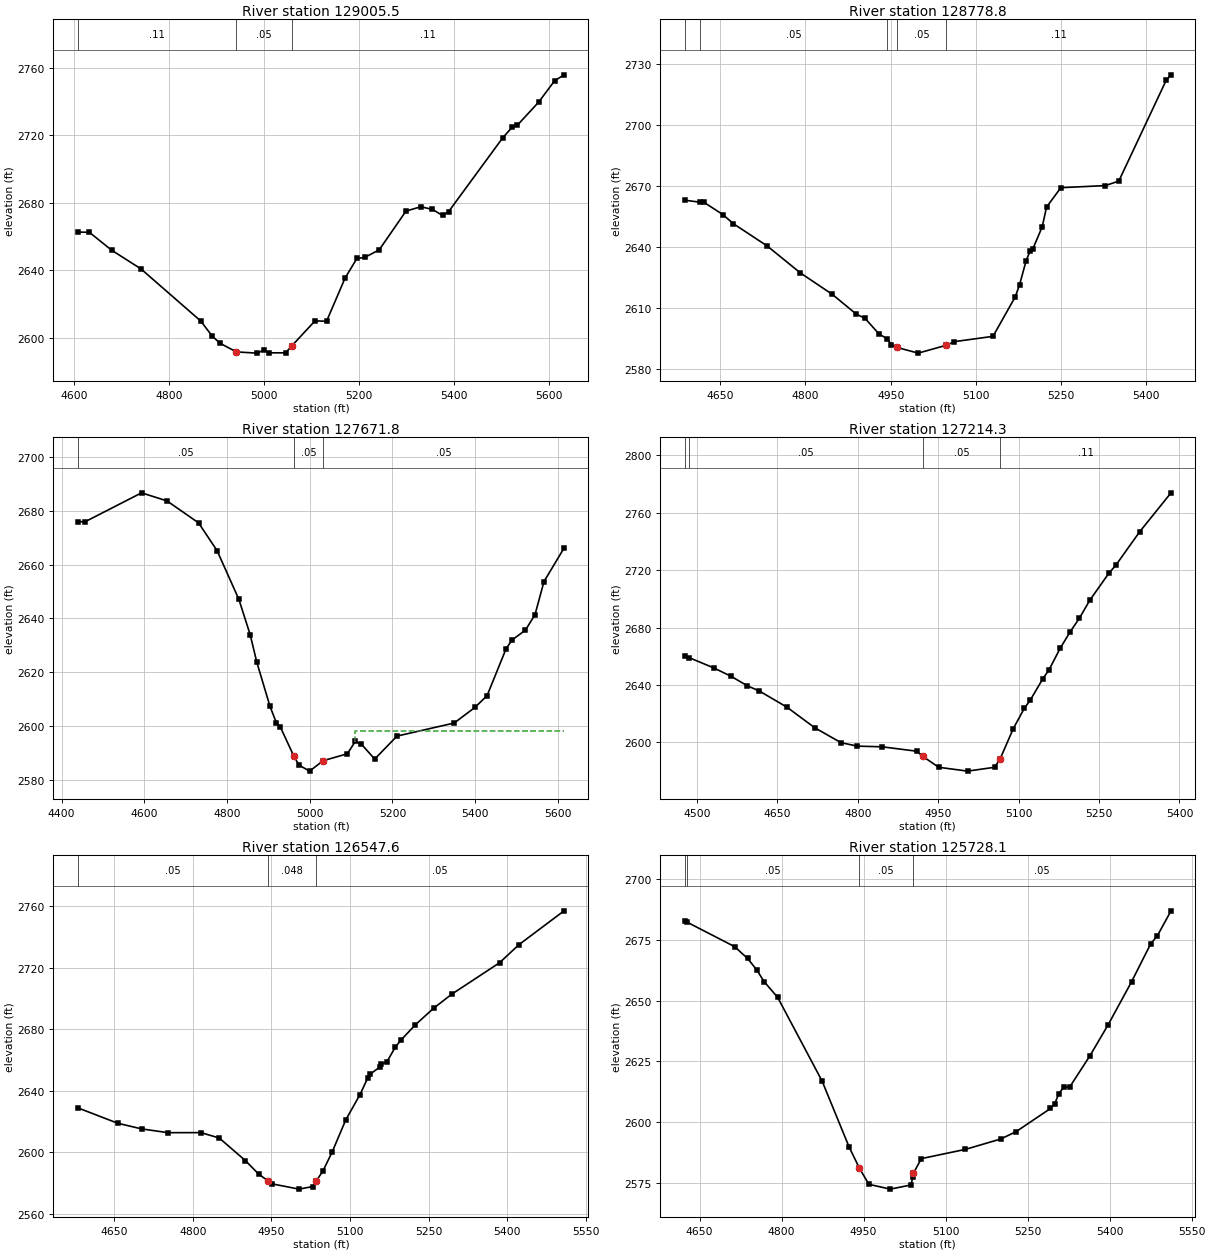
Type RM Length L Ch R = 1 ,129005.5,205.45,226.49,248.7
BEGIN DESCRIPTION:
Adjustment to Manning's n values were attempted, but no reasonable value was able to increase the WSEL to the adjusted effective
END DESCRIPTION:
XS GIS Cut Line= 5
     1019464.505       800178.66     1019576.614      800240.614
     1019712.324      800231.764     1020076.677      800162.433
     1020362.849      799898.388
#Sta/Elev= 30
 4607.23 2662.71 4631.92  2662.5 4678.72 2651.89 4740.12 2640.88 4866.29 2609.89
  4890.3    2601 4906.73 2596.72 4941.38 2591.54 4984.96 2590.82    5000 2592.64
 5010.26 2591.01 5045.03 2590.98 5057.54 2594.95 5107.01 2609.96 5131.31 2609.73
  5170.3 2635.35 5195.21 2647.01 5211.38 2647.59 5242.21 2652.12 5298.66 2675.13
 5329.89 2677.71 5354.36 2676.11 5375.54 2672.53 5388.51 2674.85 5502.61 2718.72
 5522.14 2724.87 5532.74 2725.97    5578 2739.78 5611.71 2752.49 5631.58 2756.01
#Mann= 3 , 0 , 0
 4607.23     .11       0 4941.38     .05       0 5057.54     .11       0
Bank Sta=4941.38,5057.54
Exp/Cntr=0.3,0.1

Type RM Length L Ch R = 1 ,128778.8,1091.85,1107.08,1124.1
XS GIS Cut Line= 2
     1019454.317      800180.025     1020185.112      800625.811
#Sta/Elev= 30
 4587.43 2663.04 4614.12 2662.05 4620.92 2662.06 4654.64 2655.97 4672.93 2651.54
 4732.27 2640.65 4791.23 2627.33 4847.36 2616.81  4889.2  2607.2 4904.93 2605.05
 4929.49  2597.4 4944.34 2594.99 4951.09 2592.06 4961.25 2590.78 4998.52 2588.01
 5048.14  2591.9 5061.93 2593.64 5130.06 2596.24 5169.28 2615.61 5176.89 2621.55
 5188.42 2633.38 5195.51 2638.13 5200.31  2639.2 5216.72 2649.96 5224.36 2659.65
 5249.56 2669.17  5328.1  2670.2 5351.55 2672.42 5434.85 2721.79 5443.46 2724.53
#Mann= 5 ,-1 , 0
 4587.43     .05       0 4614.12     .05       0 4944.34     .05       0
 4961.25     .05       0 5048.14     .11       0
Bank Sta=4961.25,5048.14
Exp/Cntr=0.3,0.1

Type RM Length L Ch R = 1 ,127671.8,436.85,457.52,478.18
XS GIS Cut Line= 2
      1018766.61      800599.998     1019343.904      801624.564
#Sta/Elev= 30
 4438.99 2675.88 4457.14 2675.93 4593.39 2686.64 4654.79 2683.64 4731.05  2675.5
 4775.97 2665.16 4828.69 2647.06 4856.03 2633.93 4872.14 2623.65 4903.96  2607.3
 4919.22 2601.29 4928.55 2599.79 4961.67 2588.81 4973.99 2585.53  4999.5 2583.28
 5032.63 2587.16 5090.91 2589.72 5110.16  2594.3 5124.55 2593.34 5157.16 2587.76
 5210.92 2596.29 5349.23 2601.14 5399.36 2606.93 5428.69 2611.27 5475.04 2628.81
 5489.56 2632.03 5521.34  2635.6 5544.75  2641.4  5566.4 2653.67    5615 2666.13
#Mann= 3 , 0 , 0
 4438.99     .05       0 4961.67     .05       0 5032.63     .05       0
#XS Ineff= 2 , 0
                         5109.74         2598.22
Permanent Ineff=
       F       F
#Block Obstruct= 2 , 0
                         5110.23         2594.24
Bank Sta=4961.67,5032.63
Exp/Cntr=0.3,0.1

Type RM Length L Ch R = 1 ,127214.3,639.89,666.67,693.44
XS GIS Cut Line= 2
     1018731.625      800756.755     1018574.982      801650.329
#Sta/Elev= 30
 4477.08 2660.26 4484.75 2659.11 4530.88 2651.94 4562.96 2646.16 4594.09  2639.4
 4616.45 2635.76 4667.91 2624.52 4719.37 2610.29 4768.47 2599.85 4799.09 2597.42
 4845.34 2596.94 4910.01 2593.87  4921.3 2590.25 4950.88  2582.7 5004.73 2580.01
 5055.36  2582.7 5065.64 2588.64 5090.13 2609.68 5110.45 2623.63 5121.49 2629.31
  5144.9 2644.16 5156.71 2650.55 5177.52 2665.53 5195.88 2676.88 5213.43  2686.5
 5232.68 2698.95 5268.32 2717.76 5281.43 2723.41 5325.53 2746.52 5384.28 2773.77
#Mann= 4 ,-1 , 0
 4477.08     .05       0 4484.75     .05       0  4921.3     .05       0
 5065.64     .11       0
Bank Sta=4921.3,5065.64
Exp/Cntr=0.3,0.1

Type RM Length L Ch R = 1 ,126547.6,824.16,819.48,814.8
XS GIS Cut Line= 2
     1018524.771      800665.658     1017712.138      801114.231
#Sta/Elev= 30
  4580.5 2628.88  4656.6 2618.87 4702.75 2615.15 4752.83 2612.72 4815.78 2612.75
 4850.66 2609.23  4900.7  2594.5 4926.26 2585.66 4943.03 2581.56 4951.55 2579.43
 5003.04 2576.02 5029.07 2577.71 5035.34 2581.07 5048.69 2587.95 5066.21 2600.24
 5092.25 2621.17 5119.29 2637.48 5133.77 2648.16 5138.97 2650.89 5157.16 2655.36
 5159.77 2657.19 5170.81 2658.88 5186.57 2668.32 5198.07 2673.15 5224.45 2682.69
 5259.65 2693.58 5294.04 2702.67 5385.57 2723.17 5422.67 2734.94 5508.72 2756.93
#Mann= 3 , 0 , 0
  4580.5     .05       0 4943.03    .048       0 5035.34     .05       0
Bank Sta=4943.03,5035.34
Exp/Cntr=0.3,0.1

Type RM Length L Ch R = 1 ,125728.1,612.42,607.66,602.91
XS GIS Cut Line= 2
       1018089.2      799924.538     1017387.085      800470.626
#Sta/Elev= 30
 4622.77 2682.73 4627.72 2682.29 4714.03 2672.29 4737.73 2667.43 4755.02 2662.58
 4767.96 2657.88 4792.71 2651.42 4873.96 2616.97 4923.64 2589.68 4941.85 2581.25
 4959.56  2574.4 4998.75 2572.41 5036.56 2574.12 5040.01 2577.31 5040.85 2578.85
 5055.56 2584.97 5136.33 2588.79 5201.17 2593.08 5229.07 2596.11 5291.78 2605.62
 5299.43 2607.53 5307.25 2611.79 5315.73 2614.34 5327.21 2614.56 5364.21 2627.42
 5397.44 2640.18 5440.11 2657.83 5474.87 2673.36 5487.49 2676.85 5512.25 2687.03
#Mann= 4 ,-1 , 0
 4622.77     .05       0 4627.72     .05       0 4941.85     .05       0
 5040.85     .05       0
Bank Sta=4941.85,5040.85
Exp/Cntr=0.3,0.1

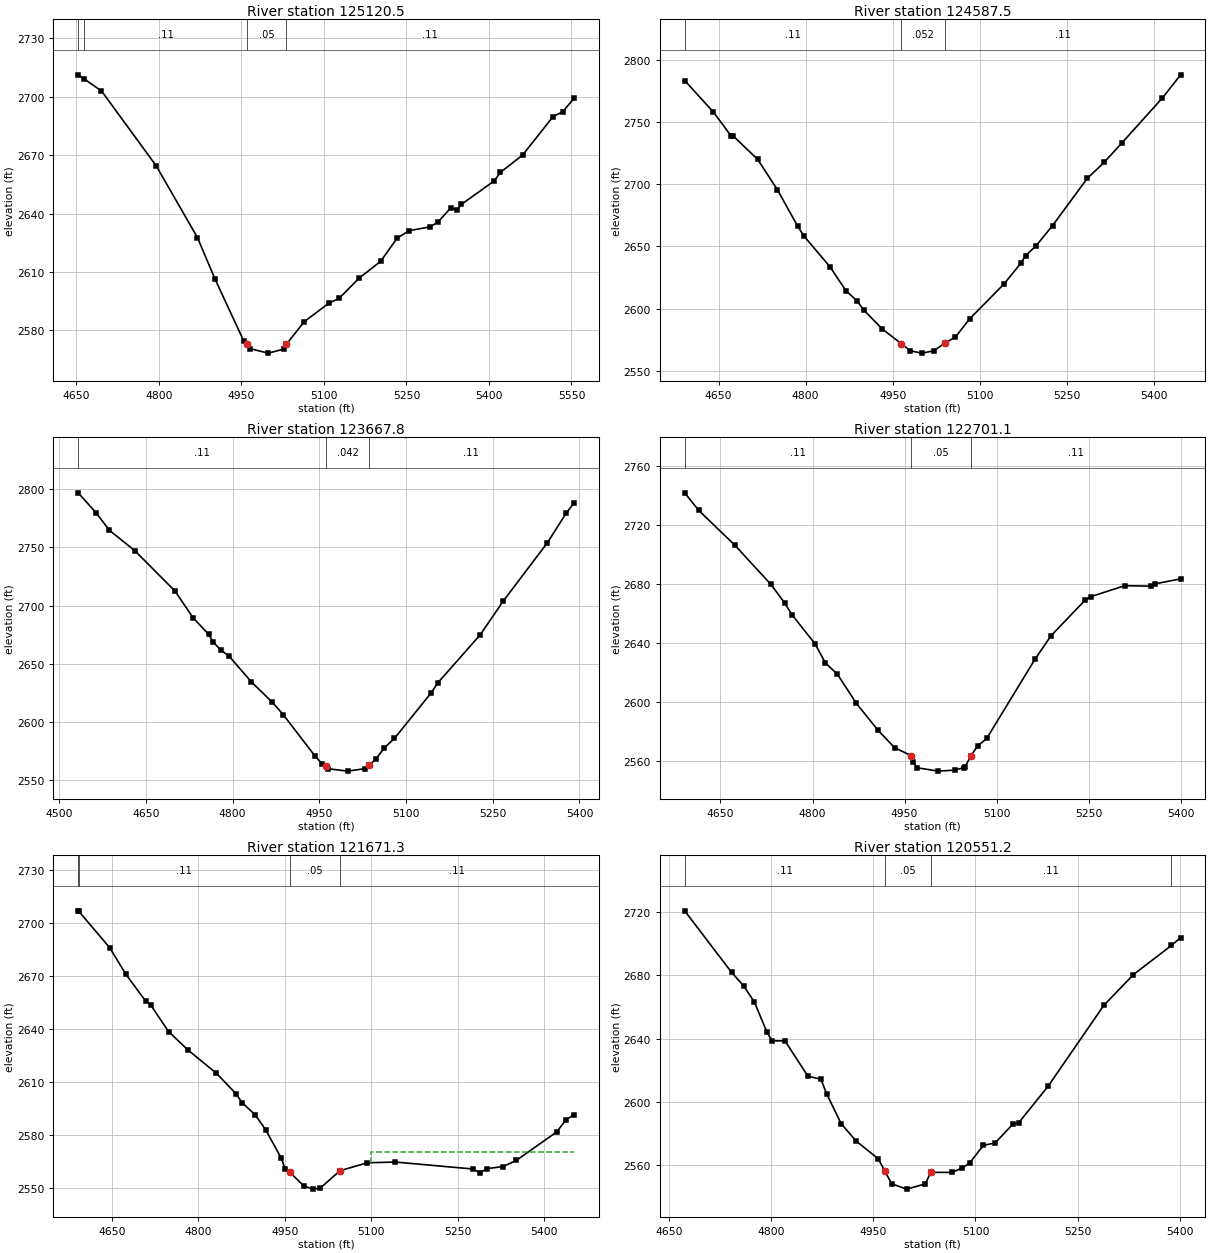
Type RM Length L Ch R = 1 ,125120.5,529.28,532.94,536.57
XS GIS Cut Line= 2
     1017581.726      799514.294     1016965.836      800172.905
#Sta/Elev= 30
 4653.15 2711.24 4664.57    2709 4695.32 2703.02 4794.96 2664.52    4870 2627.68
 4901.65 2606.55 4954.31  2574.5 4959.56  2573.3 4965.83 2570.63 4998.76 2568.37
 5027.74 2570.49 5031.51 2572.87 5064.02 2584.51 5109.07 2594.02 5127.42 2596.46
 5163.55 2606.78 5202.81 2615.43 5233.25 2627.45 5254.88 2631.24 5293.57 2633.21
 5307.87 2635.86 5330.19 2642.82 5342.16 2641.95 5349.72  2644.7 5409.73 2656.83
 5420.61 2661.13 5461.18 2670.06  5516.4 2689.75 5534.18 2692.31 5554.86 2699.23
#Mann= 4 ,-1 , 0
 4653.15     .11       0 4664.57     .11       0 4959.56     .05       0
 5031.51     .11       0
Bank Sta=4959.56,5031.51
Exp/Cntr=0.3,0.1

Type RM Length L Ch R = 1 ,124587.5,954.24,919.69,885.16
XS GIS Cut Line= 2
     1017503.404      799015.886     1016848.354      799564.135
#Sta/Elev= 30
 4591.58  2783.3  4640.9 2758.02 4671.26 2739.01 4675.47 2738.57 4717.35 2719.94
 4751.39 2695.47 4786.39 2666.09  4797.3 2658.23 4842.42 2633.35 4869.32 2614.47
 4888.02  2606.5 4899.85 2599.03 4932.04 2583.67 4964.98 2571.81 4980.31  2566.2
 5000.04 2564.34 5020.27 2566.15 5039.77 2572.36 5057.86 2577.22  5082.6 2591.96
  5141.7 2619.92 5170.61 2636.57 5178.97 2642.69 5197.24 2650.77 5225.18 2666.77
 5284.91 2704.62 5313.99 2717.54  5344.3 2732.97 5414.41 2769.26 5445.79 2787.86
#Mann= 3 , 0 , 0
 4591.58     .11       0 4964.98    .052       0 5039.77     .11       0
Bank Sta=4964.98,5039.77
Exp/Cntr=0.3,0.1

Type RM Length L Ch R = 1 ,123667.8,970.68,966.69,962.7
XS GIS Cut Line= 2
     1016195.731      798747.233     1016429.429       799572.48
#Sta/Elev= 30
 4533.15 2796.75 4563.81 2779.77 4587.18 2764.56 4631.15 2747.05 4700.48 2712.46
 4731.72 2689.59 4758.88 2675.21 4766.17 2668.99  4779.3 2662.02 4794.44 2656.35
 4832.45  2634.6 4868.99 2616.96 4887.64 2606.42 4942.08 2571.26 4955.25 2563.97
 4962.42 2562.36 4964.97    2560 4998.91 2557.92 5028.32 2559.99 5035.48 2562.75
 5048.15 2568.35 5062.56 2577.91 5080.02 2585.93 5143.97 2625.34 5154.67 2633.46
 5228.45 2674.96 5268.11 2703.77 5344.47 2753.86 5376.78 2779.01 5390.85 2788.38
#Mann= 3 , 0 , 0
 4533.15     .11       0 4962.42    .042       0 5035.48     .11       0
Bank Sta=4962.42,5035.48
Exp/Cntr=0.3,0.1

Type RM Length L Ch R = 1 ,122701.1,1024.61,1029.82,1035.03
XS GIS Cut Line= 2
     1015282.847      799221.933     1015604.182      799963.195
#Sta/Elev= 30
 4591.74 2741.88 4614.77  2729.9 4673.66 2706.25 4732.23 2679.67 4754.49 2667.19
 4766.56 2659.11 4804.21 2639.29 4821.03 2626.36 4840.43 2618.79 4871.46 2598.93
 4906.92 2580.56 4933.68 2568.86 4960.41  2563.5 4964.33 2559.02 4970.32 2555.22
 5005.01 2552.93 5031.91 2553.63 5046.23  2555.3 5048.65 2556.01 5058.13 2563.35
 5068.79 2569.95 5083.74  2575.1 5162.14 2628.72 5188.41  2644.8 5244.31 2669.12
 5253.09 2671.36 5308.49 2678.82 5350.61  2678.5 5357.72 2680.05 5399.65 2683.47
#Mann= 3 , 0 , 0
 4591.74     .11       0 4960.41     .05       0 5058.13     .11       0
Bank Sta=4960.41,5058.13
Exp/Cntr=0.3,0.1

Type RM Length L Ch R = 1 ,121671.3,1124.91,1120.16,1115.41
XS GIS Cut Line= 2
     1014366.311      799481.192     1014567.145      800317.394
#Sta/Elev= 30
 4591.81 2706.92 4592.87 2706.64 4646.45 2686.05 4674.58 2670.96 4708.56 2655.97
 4717.43  2653.7 4748.57 2638.58 4782.37 2628.14 4831.59    2615  4865.1 2603.55
 4875.94 2598.49 4899.16 2591.35 4916.86 2583.08 4943.85 2567.04 4950.83 2560.78
 4958.53 2559.12 4983.35 2551.27 4998.99 2549.51  5011.3 2550.02 5045.72 2559.92
    5093 2564.41 5141.41 2564.83 5276.11  2560.9 5288.58 2558.78 5300.76 2561.11
 5328.37 2562.26  5351.4 2565.74 5421.89 2581.94 5437.58 2588.79 5451.79 2591.65
#Mann= 4 ,-1 , 0
 4591.81     .11       0 4592.87     .11       0 4958.53     .05       0
 5045.72     .11       0
#XS Ineff= 2 , 0
                         5100.08         2570.55
Permanent Ineff=
       F       F
Bank Sta=4958.53,5045.72
Exp/Cntr=0.3,0.1

Type RM Length L Ch R = 1 ,120551.2,1018.29,1012,1005.71
XS GIS Cut Line= 2
     1013536.007      799947.555     1013826.505      800614.916
#Sta/Elev= 30
 4673.21 2720.82 4742.04 2681.92 4759.92 2673.27 4775.52 2663.14 4794.01    2644
 4801.48  2638.6 4820.41 2638.59 4853.97  2616.3 4873.24 2614.27 4881.68 2604.95
 4902.79 2586.28 4924.61 2575.31 4957.22    2564 4966.98  2556.2 4977.12 2548.14
 4999.05 2544.81 5026.51 2548.14 5034.26 2555.42 5065.45 2555.38 5080.46 2558.19
 5091.27 2561.25 5111.56 2572.52 5128.83 2574.01  5154.5 2585.76 5163.67 2586.91
  5206.5 2609.84 5288.23 2660.96 5331.79 2680.48 5387.63 2698.94 5401.06  2703.9
#Mann= 4 ,-1 , 0
 4673.21     .11       0 4966.98     .05       0 5034.26     .11       0
 5387.63     .05       0
Bank Sta=4966.98,5034.26
Exp/Cntr=0.3,0.1

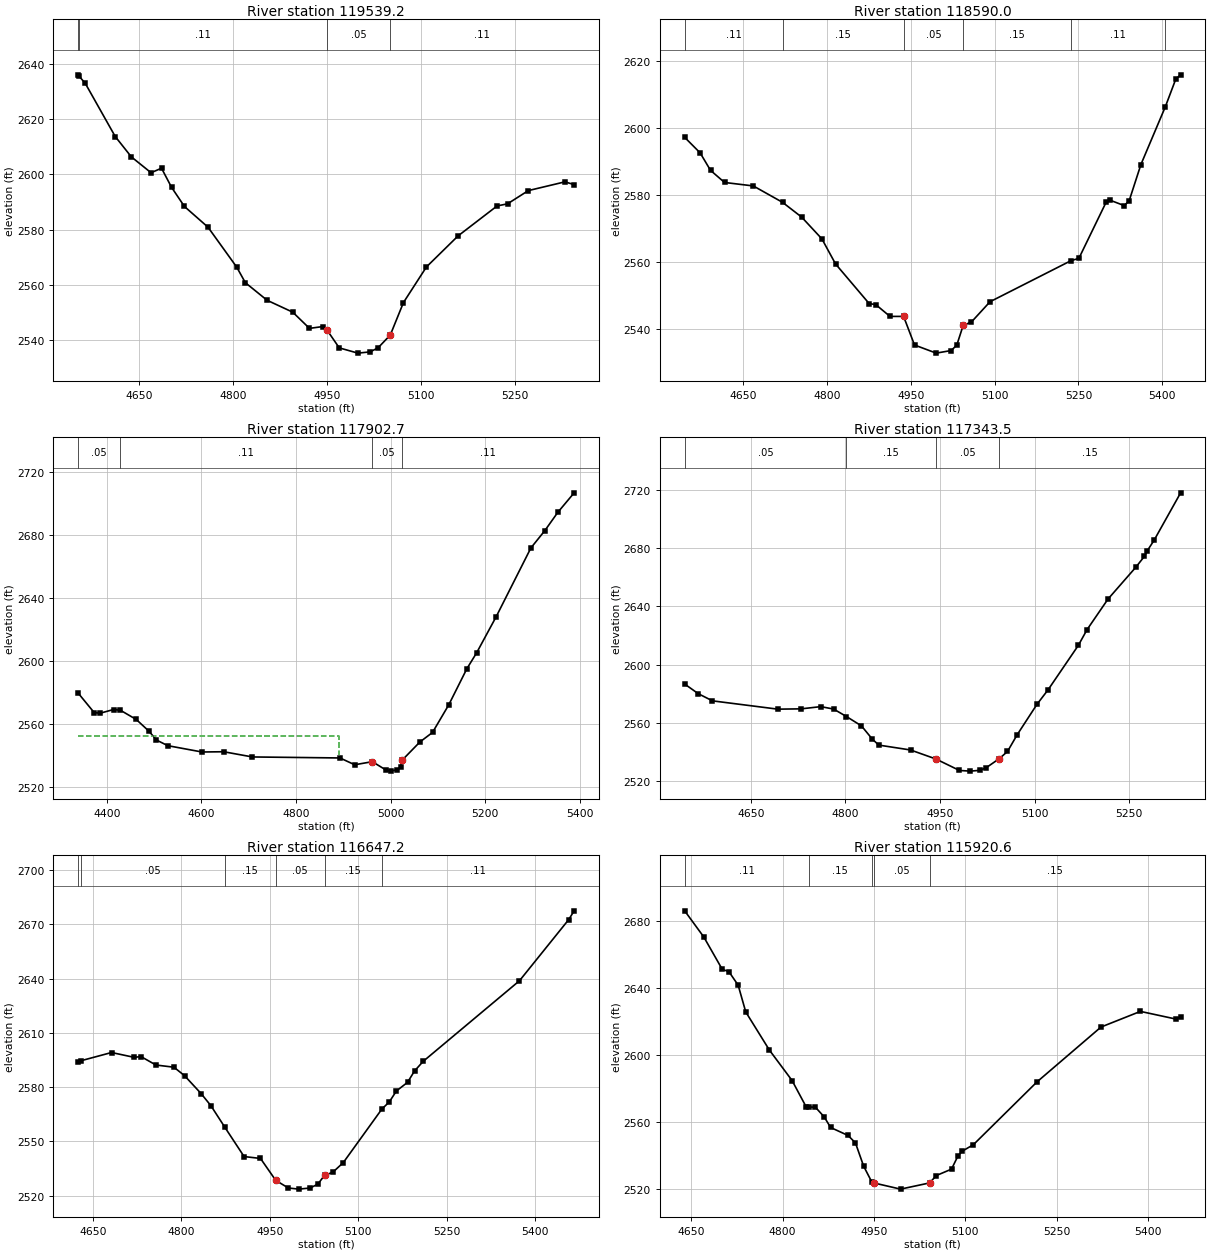
Type RM Length L Ch R = 1 ,119539.2,949.72,949.2,948.67
XS GIS Cut Line= 2
     1012699.387      800560.949     1013155.829      801207.272
#Sta/Elev= 30
    4553 2635.99 4554.22 2635.55 4564.27  2632.9 4612.04 2613.67 4637.78  2606.3
 4669.23 2600.56  4685.9  2602.2 4701.98 2595.26 4722.48 2588.35 4760.05 2580.86
 4805.93 2566.39  4819.6 2560.79 4854.33 2554.41 4895.29  2550.1 4921.96 2544.24
 4942.86 2544.88 4949.44  2543.8  4969.5 2537.18 4999.21 2535.28 5018.77 2535.73
 5031.32 2537.19 5050.85  2541.8  5071.9 2553.58 5108.58 2566.47 5159.15 2577.72
 5221.34 2588.55 5237.92  2589.3 5271.18  2594.1 5329.54 2597.26 5344.25 2596.26
#Mann= 4 ,-1 , 0
    4553     .11       0 4554.22     .11       0 4949.44     .05       0
 5050.85     .11       0
Bank Sta=4949.44,5050.85
Exp/Cntr=0.3,0.1

Type RM Length L Ch R = 1 ,118590.0,675.84,687.22,698.59
XS GIS Cut Line= 2
     1011850.401      800974.671     1012376.222      801690.372
#Sta/Elev= 30
 4544.94 2597.23 4572.55  2592.6 4591.19 2587.37 4616.26 2583.74 4667.85  2582.7
 4720.19  2577.8 4754.48 2573.37 4790.65 2566.87 4815.11 2559.37 4875.17 2547.54
 4887.29 2547.19 4912.61 2543.68 4936.98 2543.68 4956.49 2535.13 4995.37  2532.7
 5022.29 2533.48 5032.25 2535.11 5043.61 2540.97 5058.56 2542.03 5091.74 2548.07
 5236.37 2560.32  5250.9 2561.06 5299.59 2577.82 5306.78 2578.43 5332.18 2576.81
 5340.99 2578.32 5361.92  2589.1 5405.67 2606.38 5424.45 2614.69 5433.04 2615.93
#Mann= 6 ,-1 , 0
 4544.94     .11       0 4720.19     .15       0 4936.98     .05       0
 5043.61     .15       0 5236.37     .11       0 5405.67     .15       0
Bank Sta=4936.98,5043.61
Exp/Cntr=0.3,0.1

Type RM Length L Ch R = 1 ,117902.7,541.22,559.24,577.27
XS GIS Cut Line= 2
     1011472.665      801176.842     1011739.669      802191.458
#Sta/Elev= 30
 4339.27 2579.54 4372.89 2567.26 4385.42  2566.8 4414.22 2569.17  4428.3 2568.73
 4461.99 2562.86 4488.98 2555.39 4504.87 2549.77 4528.77  2546.2 4601.05 2542.19
 4646.95 2542.35 4707.73 2539.04 4893.08  2538.4 4924.15 2534.08  4961.5 2536.04
 4989.94 2530.81 5000.11 2530.04 5013.37 2530.89 5021.07 2532.67 5024.44 2536.96
 5062.02 2548.52 5088.79  2554.6 5123.09 2572.09 5161.39 2595.03 5182.08 2605.14
 5223.62 2628.18 5296.94 2671.77 5326.45 2682.77 5353.98 2694.41 5388.43 2706.75
#Mann= 4 ,-1 , 0
 4339.27     .05       0  4428.3     .11       0  4961.5     .05       0
 5024.44     .11       0
#XS Ineff= 2 , 0
         4890.16 2552.57
Permanent Ineff=
       F       F
Bank Sta=4961.5,5024.44
Exp/Cntr=0.3,0.1

Type RM Length L Ch R = 1 ,117343.5,689.47,696.28,703.09
XS GIS Cut Line= 2
      1011260.78      801233.846     1010995.617      801974.295
#Sta/Elev= 30
 4545.02 2586.65 4566.69    2580 4589.12 2575.11 4692.69 2569.41 4729.67 2569.62
 4760.95 2571.14 4781.29 2569.47 4801.59 2564.34 4825.35 2557.94 4842.61 2548.84
 4852.85 2544.74 4903.27 2541.38 4943.44  2535.2 4980.81 2527.32 4998.01 2526.87
 5013.22 2527.42 5022.98 2529.15 5043.95 2535.43 5056.95 2540.35 5072.27 2551.81
 5103.75 2572.74 5121.46 2582.78 5169.26 2613.16  5183.1 2623.98 5216.34 2644.97
 5260.27 2666.73    5274 2674.25 5278.78 2678.24 5289.52  2685.4 5331.52 2717.91
#Mann= 4 ,-1 , 0
 4545.02     .05       0 4801.59     .15       0 4943.44     .05       0
 5043.95     .15       0
Bank Sta=4943.44,5043.95
Exp/Cntr=0.3,0.1

Type RM Length L Ch R = 1 ,116647.2,751.6,726.68,701.81
XS GIS Cut Line= 2
     1010751.288      800930.852     1010298.497      801639.251
#Sta/Elev= 30
 4625.38 2593.82 4630.06 2594.57 4681.88 2599.12 4720.21 2596.45 4731.76 2596.88
 4757.13  2592.2 4787.65 2590.99 4805.62 2586.31 4833.64 2576.43 4850.35 2569.68
 4874.11 2557.69 4906.58 2541.55 4934.39 2540.51 4960.23 2528.38 4981.55 2524.16
 4999.41 2523.53 5018.56 2524.16 5031.63 2526.28 5043.24 2531.31 5056.63 2532.76
 5074.76 2538.21 5140.36 2567.92 5152.56 2571.71 5164.85 2577.85 5183.64 2582.61
 5195.59 2588.94 5210.33 2594.27 5373.46 2638.84 5456.89 2672.67 5466.12 2677.52
#Mann= 6 ,-1 , 0
 4625.38     .05       0 4630.06     .05       0 4874.11     .15       0
 4960.23     .05       0 5043.24     .15       0 5140.36     .11       0
Bank Sta=4960.23,5043.24
Exp/Cntr=0.3,0.1

Type RM Length L Ch R = 1 ,115920.6,0,0,0
XS GIS Cut Line= 2
     1009795.407      800717.993     1010003.201      801505.421
#Sta/Elev= 30
 4639.28 2685.79 4670.76 2670.16 4701.09 2650.86 4711.77 2649.63 4727.11 2641.48
 4739.55 2625.56 4778.42 2602.82 4815.63  2584.7 4838.79 2568.99 4843.08 2568.94
 4854.03 2568.77 4868.41 2563.01 4878.92 2556.72 4907.57 2551.96 4919.67 2547.57
 4933.14 2533.69 4946.47  2524.3 4949.72  2523.7 4993.75    2520 5041.49  2523.7
 5052.61 2528.11 5077.43 2531.91 5088.12 2539.82 5095.05 2542.61 5113.44  2546.5
 5217.82 2583.88  5322.9 2616.55 5387.64 2625.88 5446.46 2621.27 5453.66 2622.71
#Mann= 5 ,-1 , 0
 4639.28     .11       0 4843.08     .15       0 4946.47    .045       0
 4949.72     .05       0 5041.49     .15       0
Bank Sta=4949.72,5041.49
Exp/Cntr=0.3,0.1
Stream Node=Cane River      ,Midstream       , 0 , 0 ,Upstream end
Stream Node=Cane River      ,Midstream       , 0 , 1 ,Downstream end

Chan Stop Cuts=-1
Use User Specified Reach Order=0
User Specified Reach Order=Cane River      ,Midstream