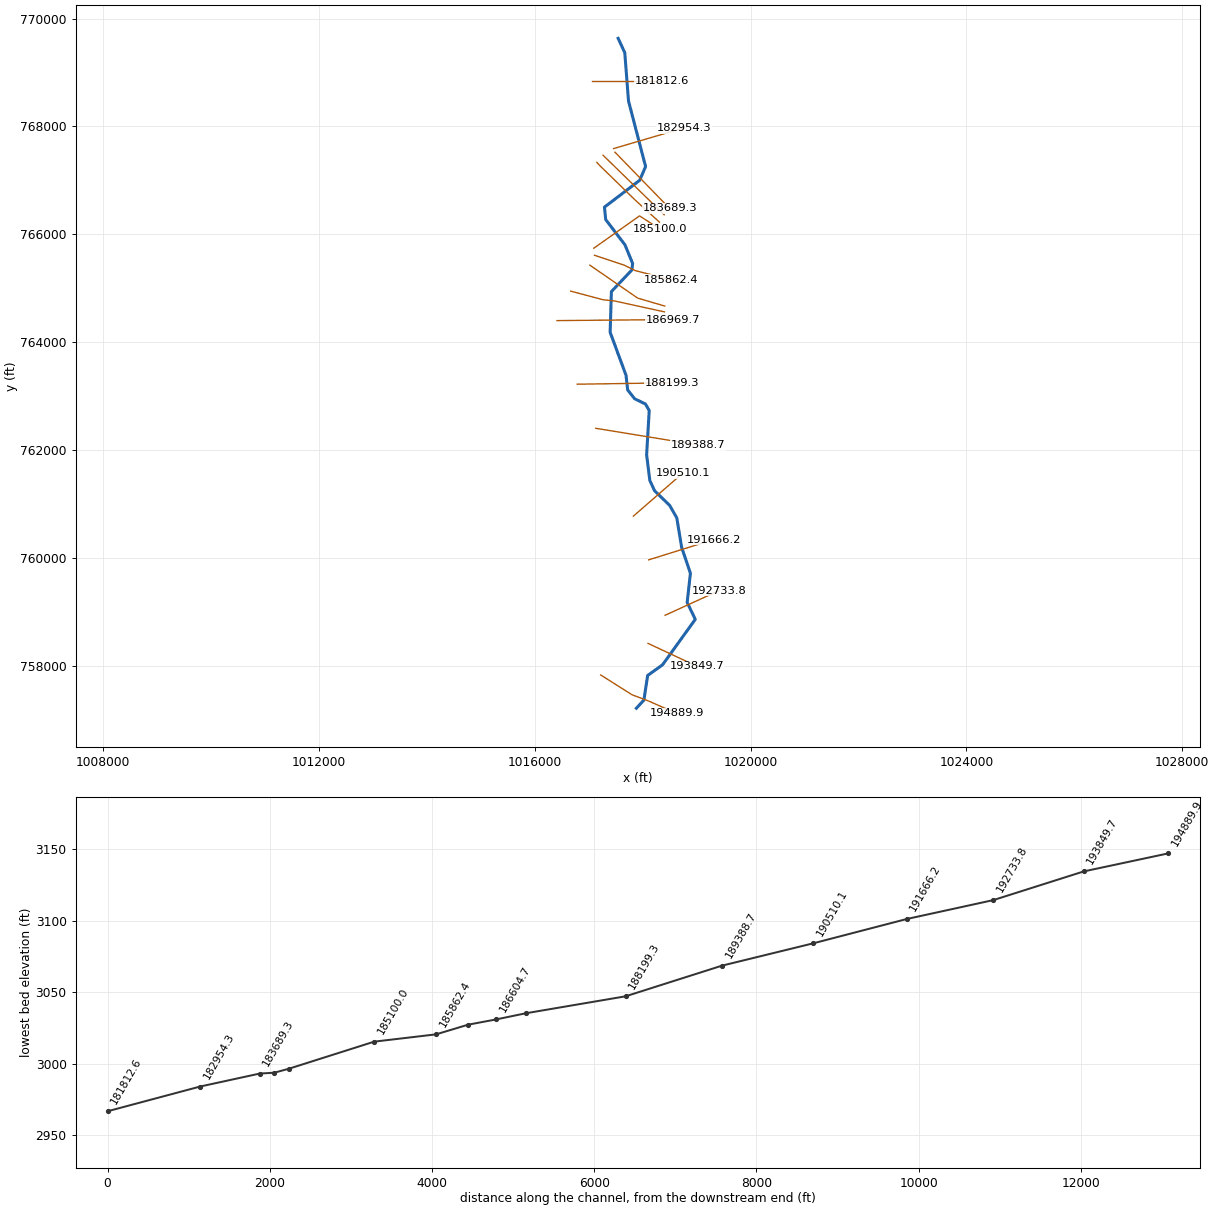
--- lds_cane_rvr_ustpream.prj (project) ---

Proj Title=Cane River - Upstream
Current Plan=p01
Default Exp/Contr=0.3,0.1
English Units
Geom File=g01
Flow File=f02
Flow File=f01
Plan File=p01
Plan File=p02
Y Axis Title=Elevation
X Axis Title(PF)=Main Channel Distance
X Axis Title(XS)=Station
BEGIN DESCRIPTION:
END DESCRIPTION:
DSS Export Rating Curves= 0
DSS Export Rating Curve Sorted= 0
DSS Export Volume Flow Curves= 0
DXF OffsetX= 0
DXF OffsetY= 0
DXF ScaleX= 1
DXF ScaleY= 10

--- lds_cane_rvr_ustpream.p01 (plan) ---

Plan Title=Floodway
Program Version=3.13
Short Identifier=FW
Geom File=g01
Flow File=f02
Subcritical Flow
K Sum by GR= 0
Std Step Tol= 0.01
Critical Tol= 0.01
Num of Std Step Trials= 20
Max Error Tol= 0.3
Flow Tol Ratio= 0.001
Split Flow NTrial= 30
Split Flow Tol= 0.02
Split Flow Ratio= 0.02
Log Output Level= 0
Friction Slope Method= 0
Unsteady Friction Slope Method= 2
Unsteady Bridges Friction Slope Method= 1
Parabolic Critical Depth
Global Vel Dist= 0 , 0 , 0
Global Log Level= 0
CheckData=True
Encroach Param=-1 ,10,10, 2
Encroach River=Cane River
Encroach Reach=Upstream
Encroach Node=194889.9
       1 4940.98 5047.59
Encroach Node=193849.7
       1 4918.85    5100
Encroach Node=192733.8
       1    4900 5017.45
Encroach Node=191666.2
       1    4935 5019.27
Encroach Node=190510.1
       1 4960.21    5116
Encroach Node=189388.7
       1 4945.88 5024.91
Encroach Node=188199.3
       1    4966    5034
Encroach Node=186969.7
       1 4970.64  5033.6
Encroach Node=186604.7
       1 4962.69 5033.88
Encroach Node=186258.9
       1 4973.49 5035.13
Encroach Node=185862.4
       1 4966.02 5025.86
Encroach Node=185100.0
       1 4961.07    5064
Encroach Node=184048.8
       1 4949.62 5056.65
Encroach Node=183866.4
       1  4959.3 5058.19
Encroach Node=183689.3
       1    4946    5034
Encroach Node=182954.3
       1 4936.55 5028.61
Encroach Node=181812.6
       1  272.22  392.22
Computation Interval=1HOUR
Output Interval=1HOUR
Run HTab= 0
Run UNet= 0
Run PostProcess= 0
UNET Theta= 1
UNET Theta Warmup= 1
UNET ZTol= 0.02
UNET ZSATol= 0.05
UNET MxIter= 20
UNET MaxInSteps= 0
UNET DtIC= 0
UNET DtMin= 0
UNET MaxCRTS= 20
UNET WFStab= 2
UNET SFStab= 1
UNET WFX= 1
UNET SFX= 1
UNET DSS MLevel= 4
UNET DZMax Abort= 100
UNET Convert EG Bridges=-1
UNET Use Existing IB Tables=-1
UNET Froude Reduction=False
UNET Froude Limit= 1
UNET Froude Power= 10
Instantaneous Interval=1HOUR
Write IC File= 0
Echo Input=False
Echo Output=False
Write Detailed= 0
Detailed Automatic Start=False, 10

--- lds_cane_rvr_ustpream.p02 (plan) ---

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Plan Title=100-yr
Short Identifier=100yr
Geom File=g01
Flow File=f01
Friction Slope Method= 1
Encroach Node=16479.98
       1 4935.02    5060
Encroach Node=15439.78
Encroach Node=14323.86
Encroach Node=13256.27
Encroach Node=12100.19
Encroach Node=10978.82
Encroach Node=9789.424
Encroach Node=8559.811
Encroach Node=8194.833
Encroach Node=7848.987
Encroach Node=7452.55
Encroach Node=6690.082
Encroach Node=5638.882
Encroach Node=5456.503
Encroach Node=5279.402
Encroach Node=4544.389
Encroach Node=3402.654
       1    4968    5072

--- lds_cane_rvr_ustpream.f02 (steady flow) ---

Flow Title=Floodway Flows
Program Version=3.13
Number of Profiles= 2
Profile Names=1%,FW
River Rch & RM=Cane River,Upstream        ,194889.9
    5960    5960
River Rch & RM=Cane River,Upstream        ,193849.7
    6180    6180
River Rch & RM=Cane River,Upstream        ,189388.7
    6420    6420
River Rch & RM=Cane River,Upstream        ,186969.7
    6640    6640
River Rch & RM=Cane River,Upstream        ,185100.0
    6840    6840
Boundary for River Rch & Prof#=Cane River,Upstream        , 1
Up Type= 0
Dn Type= 1
Dn Known WS=2977.34
Boundary for River Rch & Prof#=Cane River,Upstream        , 2
Up Type= 0
Dn Type= 1
Dn Known WS=2977.64
DSS Import GetInterval= 0
DSS Import GetPeak= 0
DSS Import FillOption= 0

--- lds_cane_rvr_ustpream.f01 (steady flow) ---

Flow Title=100-yr Flow
Program Version=3.13
Number of Profiles= 1
Profile Names=1%
River Rch & RM=Cane River,Upstream        ,194889.9
    5960
River Rch & RM=Cane River,Upstream        ,193849.7
    6180
River Rch & RM=Cane River,Upstream        ,189388.7
    6420
River Rch & RM=Cane River,Upstream        ,186969.7
    6640
River Rch & RM=Cane River,Upstream        ,185100.0
    6840
Boundary for River Rch & Prof#=Cane River,Upstream        , 1
Up Type= 0
Dn Type= 1
Dn Known WS=2977.64
DSS Import GetInterval= 0
DSS Import GetPeak= 0
DSS Import FillOption= 0

--- lds_cane_rvr_ustpream.g01 (geometry) ---

Geom Title=Cane_River_Upstream_Geom
Program Version=3.13

River Reach=Cane River      ,Upstream
Reach XY= 30
      1017885.21      757217.001     1018023.514      757367.328
     1018093.031      757823.823     1018368.781      758020.791
     1018975.904      758864.268      1018825.28      759177.096
      1018885.53      759719.333     1018723.274      760196.719
     1018632.991      760746.093     1018500.452      760976.604
     1018221.923      761247.444     1018133.561      761437.611
     1018074.014      761915.915     1018122.034      762734.214
     1018052.887      762855.225      1017851.19       762953.19
     1017722.491      763116.467     1017691.759      763389.234
     1017397.862      764184.481     1017420.913      764939.385
     1017801.245       765340.85     1017814.696      765459.941
     1017672.549      765805.706     1017315.266      766274.407
     1017292.214       766504.91     1017945.312      767002.416
     1018054.803      767257.896     1017737.857      768473.825
     1017668.706      769368.948     1017545.909      769634.049

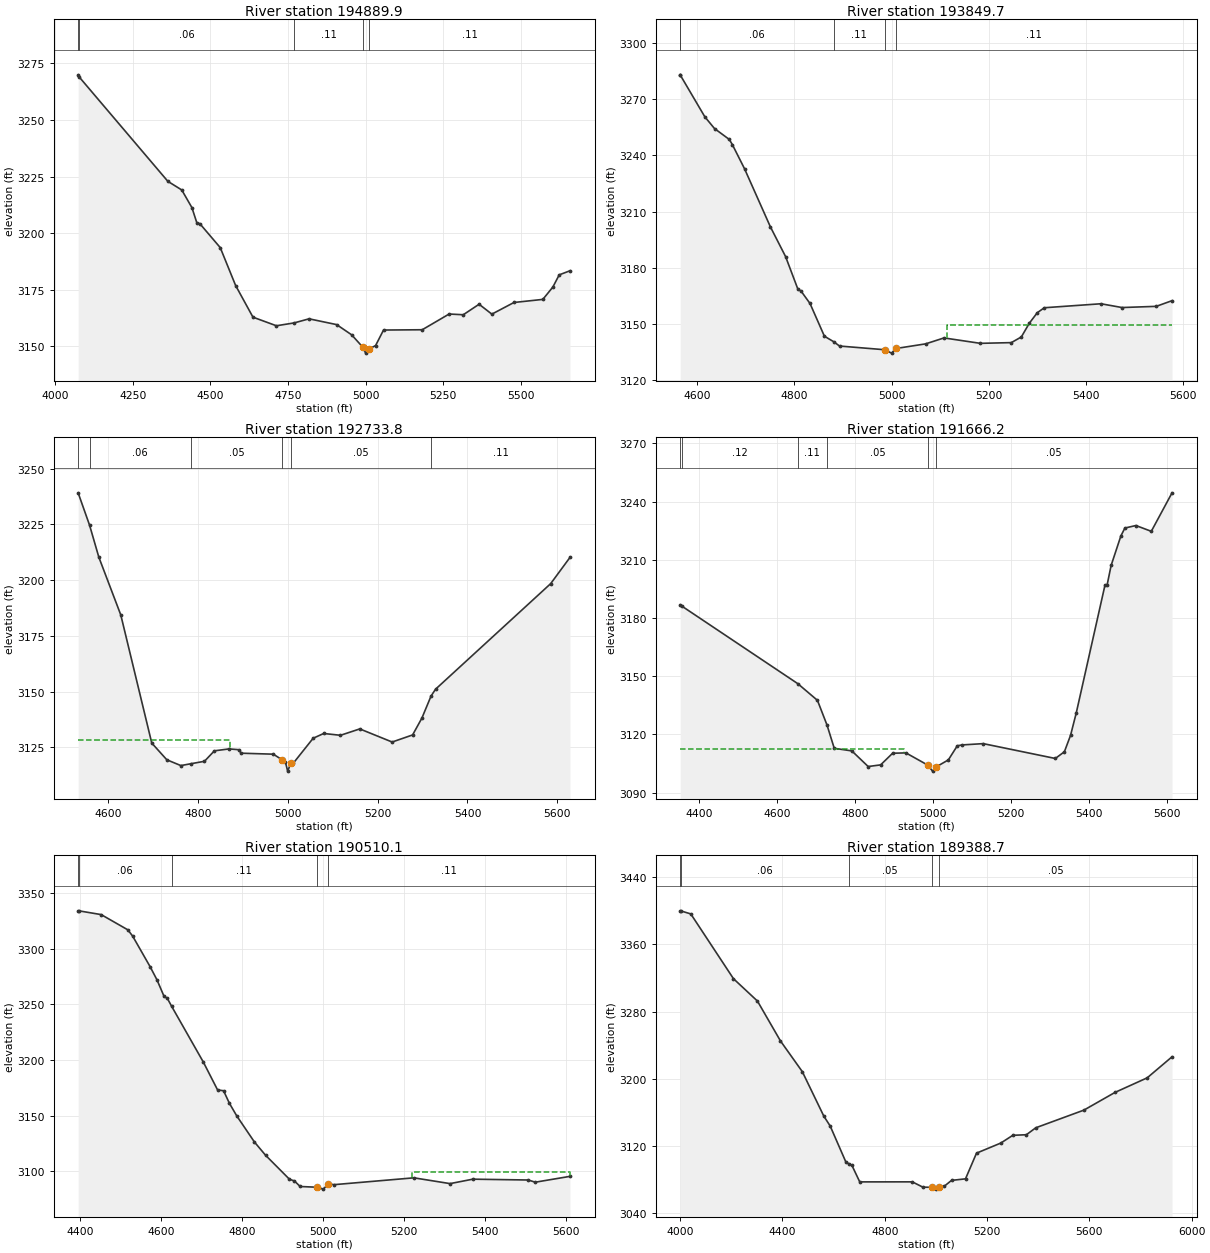
Type RM Length L Ch R = 1 ,194889.9,1042.46,1040.19,1037.93
XS GIS Cut Line= 4
     1017222.156      757833.291     1017802.225      757466.482
     1018117.851      757347.056     1018629.678      757120.999
#Sta/Elev= 30
  4074.5 3269.93 4078.81 3268.84 4363.33 3222.87 4408.13 3219.05  4440.8 3211.25
  4456.8 3204.48 4466.22 3204.17 4532.01 3193.58 4581.51 3176.83 4637.32 3162.85
 4712.76 3159.05 4769.86 3160.31 4817.96 3162.12 4906.71 3159.56 4955.11 3155.04
 4991.62 3149.47    5000 3146.96 5010.65  3148.7 5032.13 3150.32 5057.63 3157.16
 5182.25 3157.29 5268.78 3164.24 5314.35 3163.92 5365.29 3168.56 5406.34 3164.19
  5477.6 3169.34  5570.4  3170.7 5602.74 3176.16 5623.22 3181.55 5657.81 3183.35
#Mann= 5 ,-1 , 0
  4074.5     .06       0 4078.81     .06       0 4769.86     .11       0
 4991.62     .04       0 5010.65     .11       0
Bank Sta=4991.62,5010.65
Exp/Cntr=0.3,0.1

Type RM Length L Ch R = 1 ,193849.7,1088.01,1115.93,1143.84
XS GIS Cut Line= 2
     1018099.337      758418.552     1019015.336      757990.208
#Sta/Elev= 30
 4565.53 3283.04  4566.1 3282.72 4616.21 3260.59 4636.04 3254.35 4666.51 3248.51
  4672.8 3245.74 4697.85 3232.83 4750.95 3201.83  4782.2 3185.94 4807.29 3168.67
 4814.01  3167.5 4832.38 3160.91    4862 3143.41 4880.94  3140.5 4893.04 3138.17
 4986.14 3136.19    5000 3134.38 5009.52 3136.87 5070.13 3139.33 5107.87  3142.5
 5182.51 3139.61 5246.26 3139.99 5266.88 3143.02 5283.27 3150.35 5299.63 3155.96
 5314.13 3158.62 5430.67 3160.75 5473.94 3158.73 5544.22 3159.37 5576.73  3162.4
#Mann= 5 ,-1 , 0
 4565.53     .06       0  4566.1     .06       0 4880.94     .11       0
 4986.14     .04       0 5009.52     .11       0
#XS Ineff= 2 , 0
                         5113.11         3149.18
Permanent Ineff=
       F       F
Bank Sta=4986.14,5009.52
Exp/Cntr=0.3,0.1

Type RM Length L Ch R = 1 ,192733.8,1071.41,1067.59,1063.77
XS GIS Cut Line= 2
     1018415.653      758939.156     1019410.731       759393.86
#Sta/Elev= 30
 4533.94 3239.11 4559.37  3224.6 4579.99 3210.25 4628.82 3184.35 4697.72  3126.9
 4731.27 3119.39 4762.45  3116.8 4784.61 3117.62 4814.94 3118.72 4837.01 3123.41
 4869.41 3124.27 4891.06 3123.93 4896.61 3122.35 4968.13 3121.91 4987.23 3119.45
 4994.97 3118.44    5000 3114.31 5007.45 3118.01 5012.18 3117.77 5056.76 3129.06
 5080.18 3131.19 5117.53 3130.38 5160.45 3133.24 5232.45 3127.36 5277.95 3130.54
 5298.63  3138.1 5319.01 3147.99 5328.98 3151.04 5585.14  3198.4 5627.99 3210.14
#Mann= 6 ,-1 , 0
 4533.94     .06       0 4559.37     .06       0 4784.61     .05       0
 4987.23     .04       0 5007.45     .05       0 5319.01     .11       0
#XS Ineff= 2 , 0
          4872.4 3128.09
Permanent Ineff=
       F       F
Bank Sta=4987.23,5007.45
Exp/Cntr=0.3,0.1

Type RM Length L Ch R = 1 ,191666.2,1143.63,1156.07,1168.52
XS GIS Cut Line= 2
     1018112.517      759967.183     1019318.472      760342.808
#Sta/Elev= 30
 4350.76 3186.79  4355.6 3186.05 4652.78 3146.16  4703.2 3137.57 4727.86 3124.79
 4746.35 3112.85 4791.52 3111.51 4833.48 3103.46 4865.51 3104.31 4896.26 3110.31
 4930.41 3110.49 4987.29 3104.11 4998.72 3101.09 5008.05 3103.25 5039.39 3106.88
  5062.4 3114.16 5075.26  3114.6 5129.01 3115.26 5314.12 3107.61 5337.38 3111.07
 5353.23 3119.54 5367.85 3131.07 5441.64 3196.95 5447.34 3197.24 5457.42 3207.11
 5482.49 3222.32 5492.74 3226.37    5521 3227.67 5560.56 3224.68 5613.86 3244.52
#Mann= 6 ,-1 , 0
 4350.76     .12       0  4355.6     .12       0 4652.78     .11       0
 4727.86     .05       0 4987.29     .04       0 5008.05     .05       0
#XS Ineff= 2 , 0
         4925.68 3112.33
Permanent Ineff=
       F       F
#Block Obstruct= 2 , 0
                         5126.78         3115.41
Bank Sta=4987.29,5008.05
Exp/Cntr=0.3,0.1

Type RM Length L Ch R = 1 ,190510.1,1147.76,1121.37,1094.98
XS GIS Cut Line= 2
     1017829.151      760777.743     1018745.149      761575.123
#Sta/Elev= 30
 4394.49  3333.7 4396.26 3333.96 4451.42 3330.57 4517.13 3316.91 4528.93 3311.37
 4572.17 3283.83 4589.23 3271.94 4606.67 3257.13 4614.57 3255.48 4625.54 3248.11
 4703.76 3198.06 4738.84 3173.11 4753.58 3172.41 4768.04 3161.11 4786.08 3149.85
 4829.78 3126.38 4857.21 3114.51  4916.2 3092.95 4928.67 3091.37 4942.65 3086.41
 4984.33 3085.75    5000 3084.05  5012.4 3088.93 5025.59 3088.03 5223.55  3094.2
 5312.81    3089 5369.03 3092.99 5506.04 3092.24 5523.29 3090.27 5608.93 3095.52
#Mann= 5 ,-1 , 0
 4394.49     .06       0 4396.26     .06       0 4625.54     .11       0
 4984.33     .04       0  5012.4     .11       0
#XS Ineff= 2 , 0
                         5218.58         3099.12
Permanent Ineff=
       F       F
Bank Sta=4984.33,5012.4
Exp/Cntr=0.3,0.1

Type RM Length L Ch R = 1 ,189388.7,1183.95,1189.41,1194.86
XS GIS Cut Line= 2
      1017130.62      762405.452     1019028.516      762095.726
#Sta/Elev= 30
 4000.31 3399.44 4001.68 3399.88 4041.64  3396.2 4208.63 3319.03 4302.22 3292.45
 4392.33 3244.94 4477.67 3208.39 4561.78 3155.43 4586.85 3143.54 4647.91 3100.85
 4658.71 3098.77 4671.59 3096.81 4702.28 3077.11 4907.81 3077.15 4949.48 3070.78
 4983.64 3070.71    5000 3068.49 5013.05 3071.03 5032.08 3071.77  5061.1 3078.89
 5115.78 3080.74 5158.79 3111.33 5253.89 3123.37 5300.72 3132.58 5353.75 3133.25
 5390.55 3141.54 5578.72 3162.58 5700.69 3183.72  5826.2 3201.02 5923.31 3226.08
#Mann= 5 ,-1 , 0
 4000.31     .06       0 4001.68     .06       0 4658.71     .05       0
 4983.64     .04       0 5013.05     .05       0
#Block Obstruct= 2 , 0
         4904.19 3077.32
Bank Sta=4983.64,5013.05
Exp/Cntr=0.3,0.1

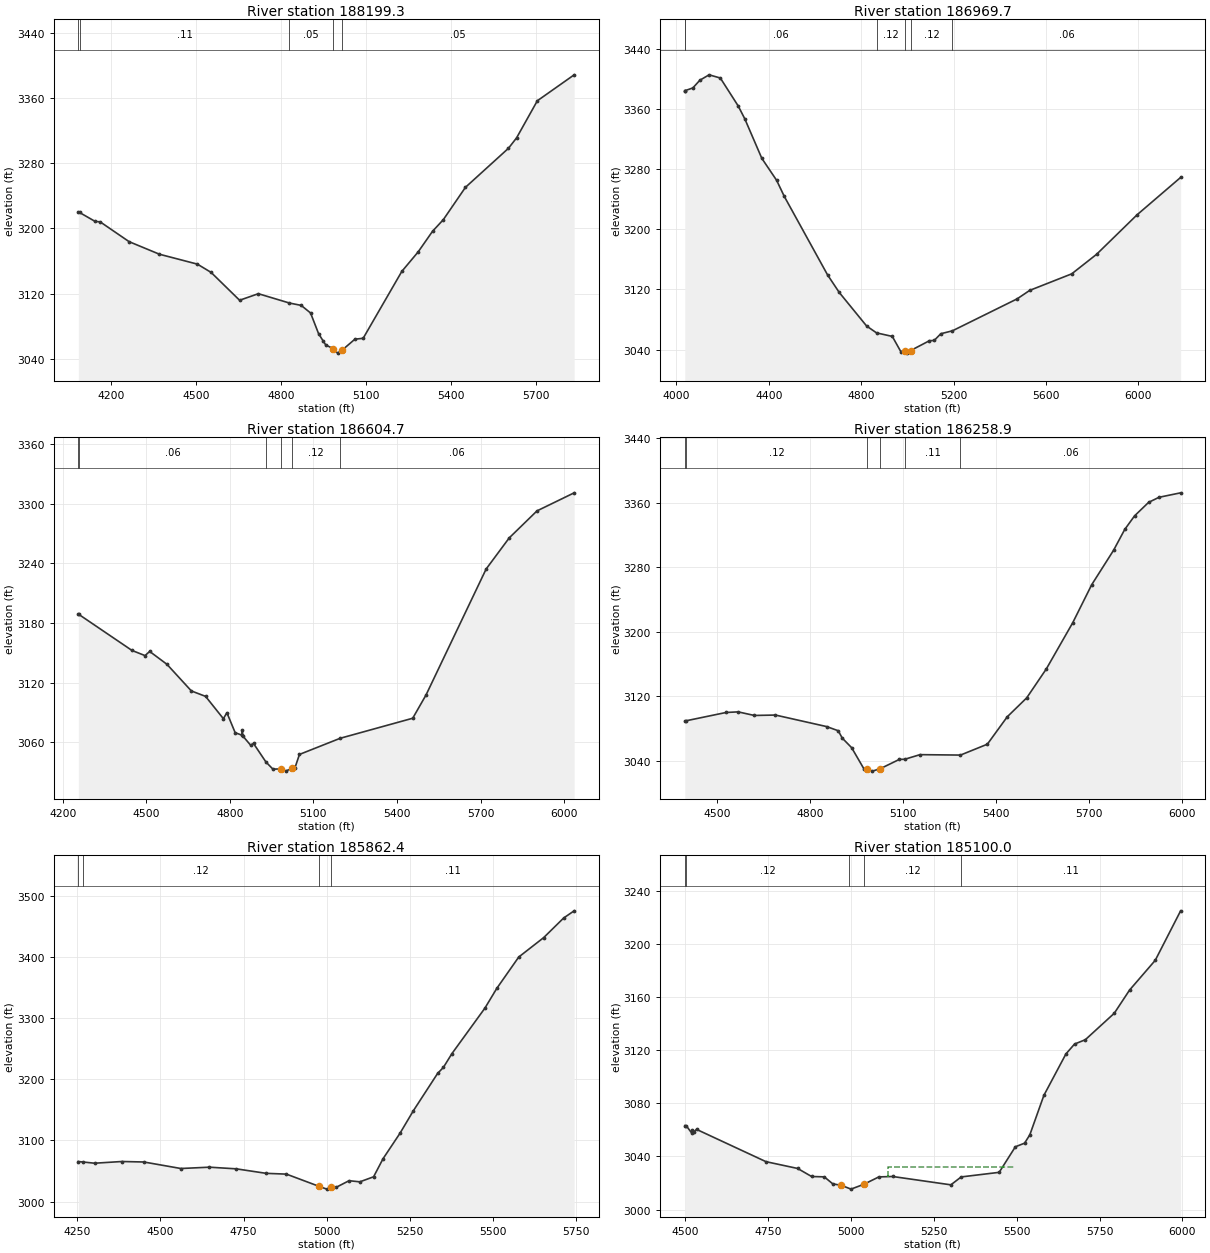
Type RM Length L Ch R = 1 ,188199.3,1229.8,1229.61,1229.43
XS GIS Cut Line= 2
     1016787.944      763222.602     1018540.862      763248.962
#Sta/Elev= 30
 4083.05 3220.21  4087.3 3219.59  4142.5 3208.61 4160.17  3208.1 4262.68 3183.76
 4369.93 3168.36 4503.99 3156.22 4552.47 3146.08 4653.23 3111.91 4719.54 3119.95
 4829.67 3108.48 4871.02 3105.61 4904.14 3096.31 4932.42    3071 4949.02 3061.78
 4958.09 3056.96 4983.75  3052.7    5000 3047.05 5015.72 3050.71 5060.96 3064.15
 5090.12 3065.25 5226.87 3147.33 5284.59 3171.23 5335.54 3196.56 5373.68 3210.83
 5451.87 3250.46 5603.83 3298.32 5632.58 3311.11 5705.98 3356.62 5836.17 3388.45
#Mann= 5 ,-1 , 0
 4083.05     .11       0  4087.3     .11       0 4829.67     .05       0
 4983.75     .04       0 5015.72     .05       0
Bank Sta=4983.75,5015.72
Exp/Cntr=0.3,0.1

Type RM Length L Ch R = 1 ,186969.7,368.64,364.98,361.32
XS GIS Cut Line= 2
     1016413.046       764401.73     1018560.261      764421.429
#Sta/Elev= 30
 4036.06  3384.3 4037.86 3384.38 4070.82 3387.87  4101.2 3398.14 4141.31 3405.33
 4189.94 3401.09 4266.94 3364.11 4295.59 3347.01 4369.61 3294.27 4433.85 3264.98
 4466.88 3243.65 4654.26 3139.28 4704.71 3115.98 4823.51 3071.25 4866.47 3062.13
 4934.68 3057.44 4971.47 3037.27 4989.34 3037.79 5000.01  3035.2 5014.14 3038.63
 5095.64 3051.72 5116.14 3052.03 5144.76 3060.99 5195.15 3064.89 5475.31 3107.36
 5530.02 3118.67  5711.8 3140.65 5819.14 3166.56 5995.12 3219.27 6183.37 3268.86
#Mann= 6 ,-1 , 0
 4036.06     .06       0 4037.86     .06       0 4866.47     .12       0
 4989.34     .04       0 5014.14     .12       0 5195.15     .06       0
Bank Sta=4989.34,5014.14
Exp/Cntr=0.3,0.1

Type RM Length L Ch R = 1 ,186604.7,360.63,345.84,331.07
XS GIS Cut Line= 4
     1016667.677      764947.675     1017260.543      764789.862
     1017486.599       764764.27     1018403.621      764563.805
#Sta/Elev= 30
 4256.15 3188.96 4258.16 3188.54  4448.6 3152.34 4495.65 3147.13 4512.17 3151.34
 4574.22 3138.38 4661.88 3111.57 4712.89 3106.11 4776.77 3083.66  4789.4 3089.67
 4819.09 3069.58  4844.2 3066.99 4845.06 3072.03 4845.54 3066.58  4874.5 3057.01
 4884.97 3058.72 4929.69 3040.03 4954.64  3032.9 4982.86 3033.13    5000  3030.9
 5023.88 3033.74 5033.13  3033.8 5049.87  3047.7 5196.16 3063.96 5456.37 3084.11
  5504.2 3107.55 5719.86 3234.24 5802.81 3265.58 5902.45 3292.74 6035.84 3310.91
#Mann= 6 ,-1 , 0
 4256.15     .06       0 4258.16     .06       0 4929.69     .12       0
 4982.86     .04       0 5023.88     .12       0 5196.16     .06       0
Bank Sta=4982.86,5023.88
Exp/Cntr=0.3,0.1

Type RM Length L Ch R = 1 ,186258.9,391.88,396.44,400.99
XS GIS Cut Line= 3
     1017021.788      765429.431     1017908.252      764818.755
     1018410.582      764671.011
#Sta/Elev= 30
 4394.55 3089.56 4397.57 3089.52  4527.7  3099.9 4566.68 3100.66 4618.88 3096.21
  4687.2 3096.71 4852.38 3082.42 4889.71 3077.26 4902.66 3068.16 4933.02 3056.24
 4972.64 3030.01 4983.49 3029.46 5000.01 3027.23 5025.13  3030.2 5087.09  3041.8
 5103.95 3041.89 5153.74 3047.65 5284.24 3047.12 5370.88 3060.59 5435.05 3094.51
 5498.02 3118.07 5561.33 3153.95 5646.27 3210.98 5707.81 3258.31 5778.34 3300.94
 5814.25 3326.68  5846.1 3343.58 5891.38 3360.27 5924.84 3366.53 5994.61 3372.06
#Mann= 6 ,-1 , 0
 4394.55     .12       0 4397.57     .12       0 4983.49     .04       0
 5025.13     .12       0 5103.95     .11       0 5284.24     .06       0
Bank Sta=4983.49,5025.13
Exp/Cntr=0.3,0.1

Type RM Length L Ch R = 1 ,185862.4,730.26,762.47,794.68
XS GIS Cut Line= 4
     1017106.995      765613.049     1017657.208      765429.644
     1017866.204      765327.279     1018523.047      765160.936
#Sta/Elev= 30
  4253.2 3065.49 4266.09 3064.83 4302.14 3062.79 4384.29 3065.58 4450.21 3064.78
 4561.36 3054.14 4647.15  3056.3 4727.89  3053.6 4817.71 3046.25  4878.7 3044.96
 4975.93 3025.15 4976.02 3025.14    5000 3020.45 5012.74 3023.55 5028.12  3023.4
 5066.92 3034.21 5099.39 3032.38 5140.63  3040.6 5169.28 3070.35 5219.91 3111.64
 5260.28  3148.6 5333.01 3209.45 5350.46 3219.35 5376.09 3241.86 5474.92 3315.92
 5510.99 3348.49 5576.95 3399.67 5651.94 3431.41 5712.07 3463.48 5743.47 3475.14
#Mann= 4 ,-1 , 0
  4253.2     .12       0 4266.09     .12       0 4975.93     .04       0
 5012.74     .11       0
#Block Obstruct= 2 , 0
                         5078.83         3034.56
Bank Sta=4976.02,5012.74
Exp/Cntr=0.3,0.1

Type RM Length L Ch R = 1 ,185100.0,1092.94,1051.2,1009.46
XS GIS Cut Line= 3
     1017095.415      765744.112      1017942.78      766342.849
     1018328.407      766094.221
#Sta/Elev= 30
 4498.33 3063.16 4503.28  3062.9 4520.07  3057.3 4521.19    3060 4525.01 3058.35
 4533.72 3060.35 4743.36 3036.03 4838.87 3030.91 4880.97 3024.86 4919.32 3024.59
 4945.04  3019.3 4971.07 3018.19    5000 3015.35 5039.09 3019.03    5084 3024.56
 5125.63 3024.86 5301.36 3018.58 5332.49 3024.54 5447.08 3027.99 5495.97 3047.24
 5523.81 3049.97 5539.66 3056.27 5582.05 3085.98 5648.61 3117.18 5674.63 3124.61
 5707.07 3127.86 5794.39 3147.77 5840.61 3165.25 5918.14 3187.67 5994.71 3224.93
#Mann= 5 ,-1 , 0
 4498.33     .12       0 4503.28     .12       0 4994.98     .04       0
 5039.09     .12       0 5332.49     .11       0
#XS Ineff= 1 ,-1
 5112.57 5495.08  3031.7
Permanent Ineff=
       F
Bank Sta=4971.07,5039.09
Exp/Cntr=0.3,0.1

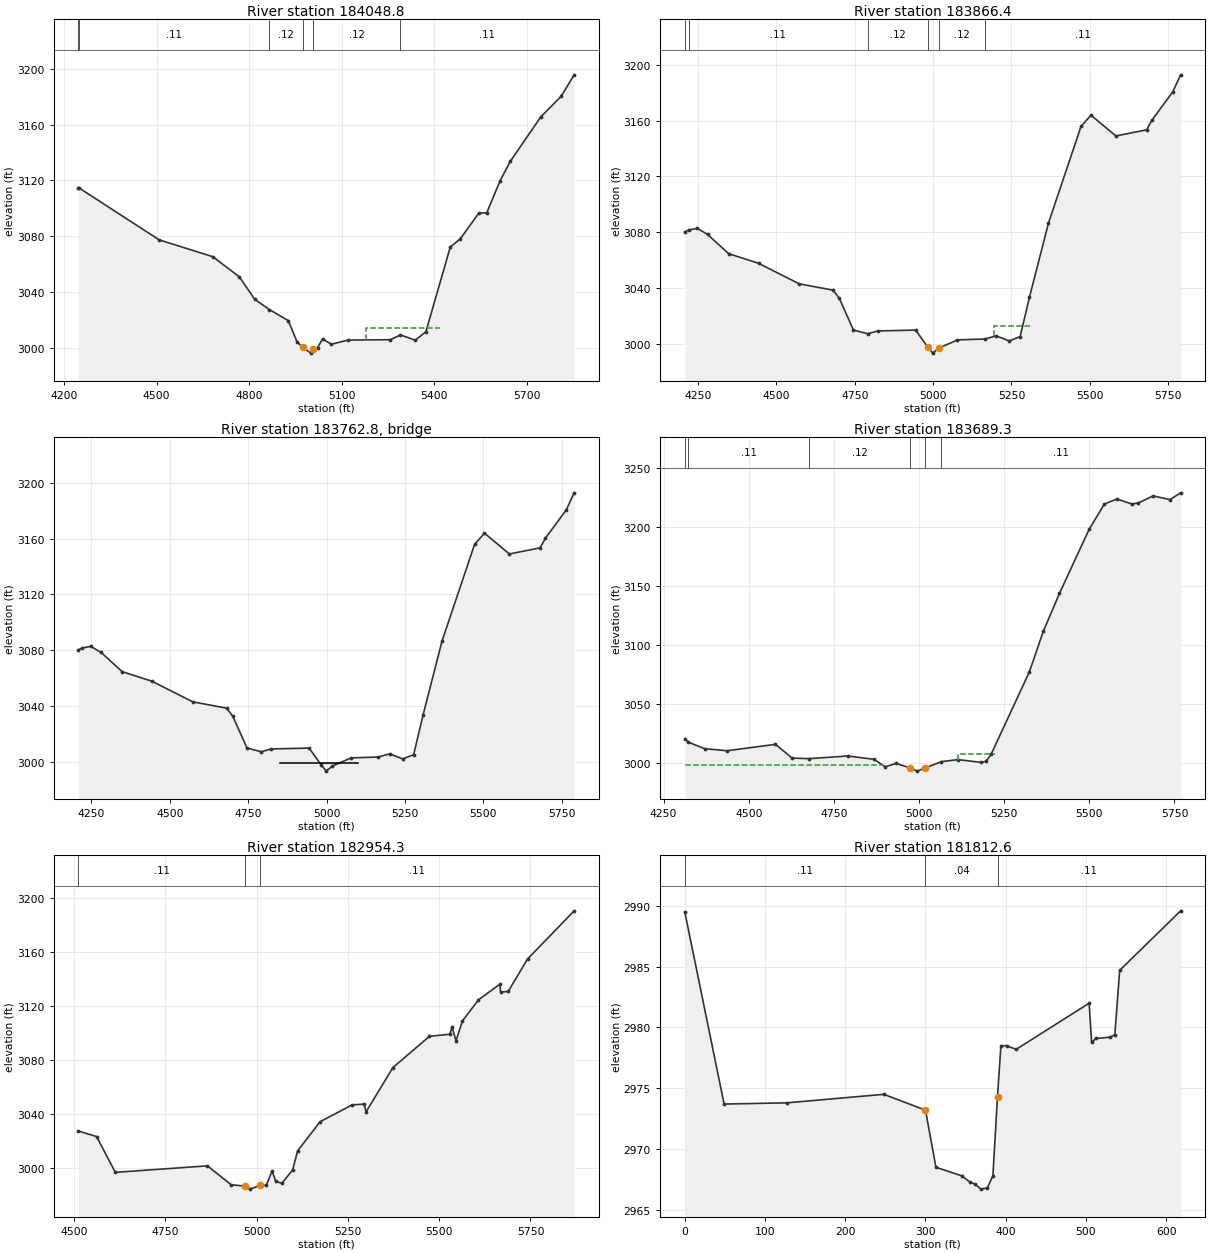
Type RM Length L Ch R = 1 ,184048.8,182.43,182.38,182.32
XS GIS Cut Line= 4
     1017149.647      767336.197     1017206.374      767274.778
     1017864.924      766633.289     1018311.919       766227.24
#Sta/Elev= 30
 4246.35 3114.89  4247.7 3114.81  4508.1 3077.53 4682.16 3065.45 4768.05 3051.06
 4818.35 3034.89 4865.74  3027.6 4926.63 3019.73 4955.31 3004.47 4972.99 3000.62
 5000.01 2996.44 5007.47 2999.32 5007.52 2999.35 5021.91 3000.43 5037.76 3006.55
 5066.75  3002.8 5120.41 3005.82 5257.47 3006.04 5290.15 3009.47 5338.14 3005.71
 5372.62 3011.71 5451.91 3072.48 5483.87 3078.13 5544.65 3096.79 5569.84 3096.81
 5612.67 3119.55 5645.88 3133.59 5745.24 3165.56 5811.15 3180.26 5853.19 3195.62
#Mann= 6 ,-1 , 0
 4246.35     .11       0  4247.7     .11       0 4865.74     .12       0
 4972.99     .04       0 5007.47     .12       0 5290.15     .11       0
#XS Ineff= 1 ,-1
 5178.32 5417.24 3014.22
Permanent Ineff=
       F
Bank Sta=4972.99,5007.52
Exp/Cntr=0.5,0.3

Type RM Length L Ch R = 1 ,183866.4,177.95,177.1,176.25
XS GIS Cut Line= 2
      1017266.62      767466.893     1018399.325      766363.736
#Sta/Elev= 30
 4208.23 3080.32 4220.38 3081.67 4247.73  3082.9  4280.9 3078.53  4348.3 3064.76
  4443.4  3057.9 4573.06 3043.19 4681.31 3038.67 4701.04  3032.8 4746.12 3010.13
 4791.73  3007.5 4823.54 3009.49 4944.16 3010.11 4982.62 2998.11 4998.76 2993.62
 5017.87 2997.15 5077.83  3003.1 5164.64  3003.7 5201.09 3005.99 5242.26 3002.37
 5277.44 3005.36 5307.18 3033.43 5367.81 3086.57 5471.82 3155.84 5503.41 3163.86
 5582.78 3148.99 5680.95 3153.36 5697.77  3160.3 5763.93 3180.39 5789.36 3192.72
#Mann= 6 ,-1 , 0
 4208.23     .11       0 4220.38     .11       0 4791.73     .12       0
 4982.62     .04       0 5017.87     .12       0 5164.64     .11       0
#XS Ineff= 4 ,-1
 5194.81 5314.46 3013.17  5106.5 5194.81  2998.5 4208.23  4893.5  2998.5
 5314.46 5789.36  2998.5
Permanent Ineff=
       F       F       F       F
Bank Sta=4982.62,5017.87
Exp/Cntr=0.5,0.3

Type RM Length L Ch R = 3 ,183762.8,,,
BEGIN DESCRIPTION:
Bear Trail Lane
END DESCRIPTION:
Bridge Culvert--1,0,-1,-1, 0
Deck Dist Width WeirC Skew NumUp NumDn MinLoCord MaxHiCord MaxSubmerge Is_Ogee
82.5,12,2.6,0, 6, 6, , , 0.95, 0, 0,0,,
    4850    4976    4976    5024    5024    5100
  2999.5  2999.5  2999.5  2999.5  2999.5  2999.5
                  2998.5  2998.5
    4850    4976    4976    5024    5024    5100
  2999.5  2999.5  2999.5  2999.5  2999.5  2999.5
                  2998.5  2998.5
BR Coef=-1 , 0 , 0 ,, 0 ,,,0.8,0,,0,
WSPro=,,,, 1 ,,,, 0 ,,,, 0 ,,,,-1 ,-1 ,-1 , 0 , 0 , 0 , 0 , 0
BC Design=,, 0 ,, 0 ,,,,,,

Type RM Length L Ch R = 1 ,183689.3,702.27,735.01,767.76
XS GIS Cut Line= 2
     1017486.654      767524.056     1018501.163      766479.997
#Sta/Elev= 30
 4312.23 3020.57 4322.48 3017.61  4370.2 3012.11 4436.26 3010.33  4578.4 3015.77
 4627.34  3004.1 4678.13 3003.63 4790.77 3005.89 4868.16 3003.03 4900.22 2996.75
 4933.33 2999.54 4973.06 2995.87 4994.19 2993.05 5016.28  2995.5  5065.1 3001.06
 5114.55 3002.81 5180.95  3000.5 5196.83 3001.37 5211.72 3007.39 5324.17 3077.36
 5364.79 3111.55 5412.32 3143.76 5499.24 3197.92 5544.14 3219.44 5580.53 3223.74
 5624.53 3219.55 5643.49 3220.37 5687.24 3226.36 5736.78 3223.21 5768.01 3228.96
#Mann= 6 ,-1 , 0
 4312.23     .11       0 4322.48     .11       0 4678.13     .12       0
 4973.06     .04       0 5016.28     .12       0  5065.1     .11       0
#XS Ineff= 4 ,-1
 4312.23  4893.5  2998.5  5106.5 5114.43  2998.5 5114.43 5222.67 3007.27
 5222.67 5768.01  2998.5
Permanent Ineff=
       F       F       F       F
Bank Sta=4973.06,5016.28
Exp/Cntr=0.5,0.3

Type RM Length L Ch R = 1 ,182954.3,1150.31,1141.73,1133.16
XS GIS Cut Line= 2
     1017462.692      767590.722     1018765.428      767973.047
#Sta/Elev= 30
 4512.01 3027.16 4561.95 3023.02 4613.33 2996.44  4865.4 3001.26 4930.24  2987.3
 4967.73 2986.17 4983.09 2983.98 5008.61 2986.78 5026.42 2986.84 5042.66 2997.43
 5052.36 2989.85 5069.14  2988.3 5098.53  2998.1 5112.65 3012.45 5173.98 3034.03
 5261.75 3046.56 5294.17 3047.12 5299.88 3041.34 5373.16 3074.21 5473.47 3097.47
 5528.92 3099.03 5535.32 3104.31 5546.27 3094.18 5563.75 3108.88 5607.59 3124.57
 5666.22 3136.17  5668.2 3130.35 5689.06 3130.81    5742 3154.87 5869.69 3190.68
#Mann= 3 , 0 , 0
 4512.01     .11       0 4967.73     .04       0 5008.61     .11       0
#Block Obstruct= 2 , 0
                          5041.7         2996.95
Bank Sta=4967.73,5008.61
Exp/Cntr=0.3,0.1

Type RM Length L Ch R = 1 ,181812.6,3382.22,3402.65,3423.09
BEGIN DESCRIPTION:
Known water surface used and HEC-2 Topo
END DESCRIPTION:
XS GIS Cut Line= 2
     1017059.974      768840.626     1018362.711      768840.626
#Sta/Elev= 23
       0  2989.5      49  2973.7     127  2973.8     248  2974.5     300  2973.2
     313  2968.5     345  2967.8     355  2967.3     362  2967.1     369  2966.7
     377  2966.8     384  2967.8  389.76 2974.31     394  2978.5     401  2978.5
     413  2978.2     504    2982     507  2978.8     513  2979.1     530  2979.2
     536  2979.4     542  2984.7     618  2989.6
#Mann= 3 ,-1 , 0
       0     .11       0     300     .04       0  389.76     .11       0
Bank Sta=300,389.76
Exp/Cntr=0.3,0.1
Stream Node=Cane River      ,Upstream        , 0 , 0 ,Upstream end
Stream Node=Cane River      ,Upstream        , 0 , 1 ,Downstream end

Chan Stop Cuts=-1
Use User Specified Reach Order=0
User Specified Reach Order=Cane River      ,Upstream